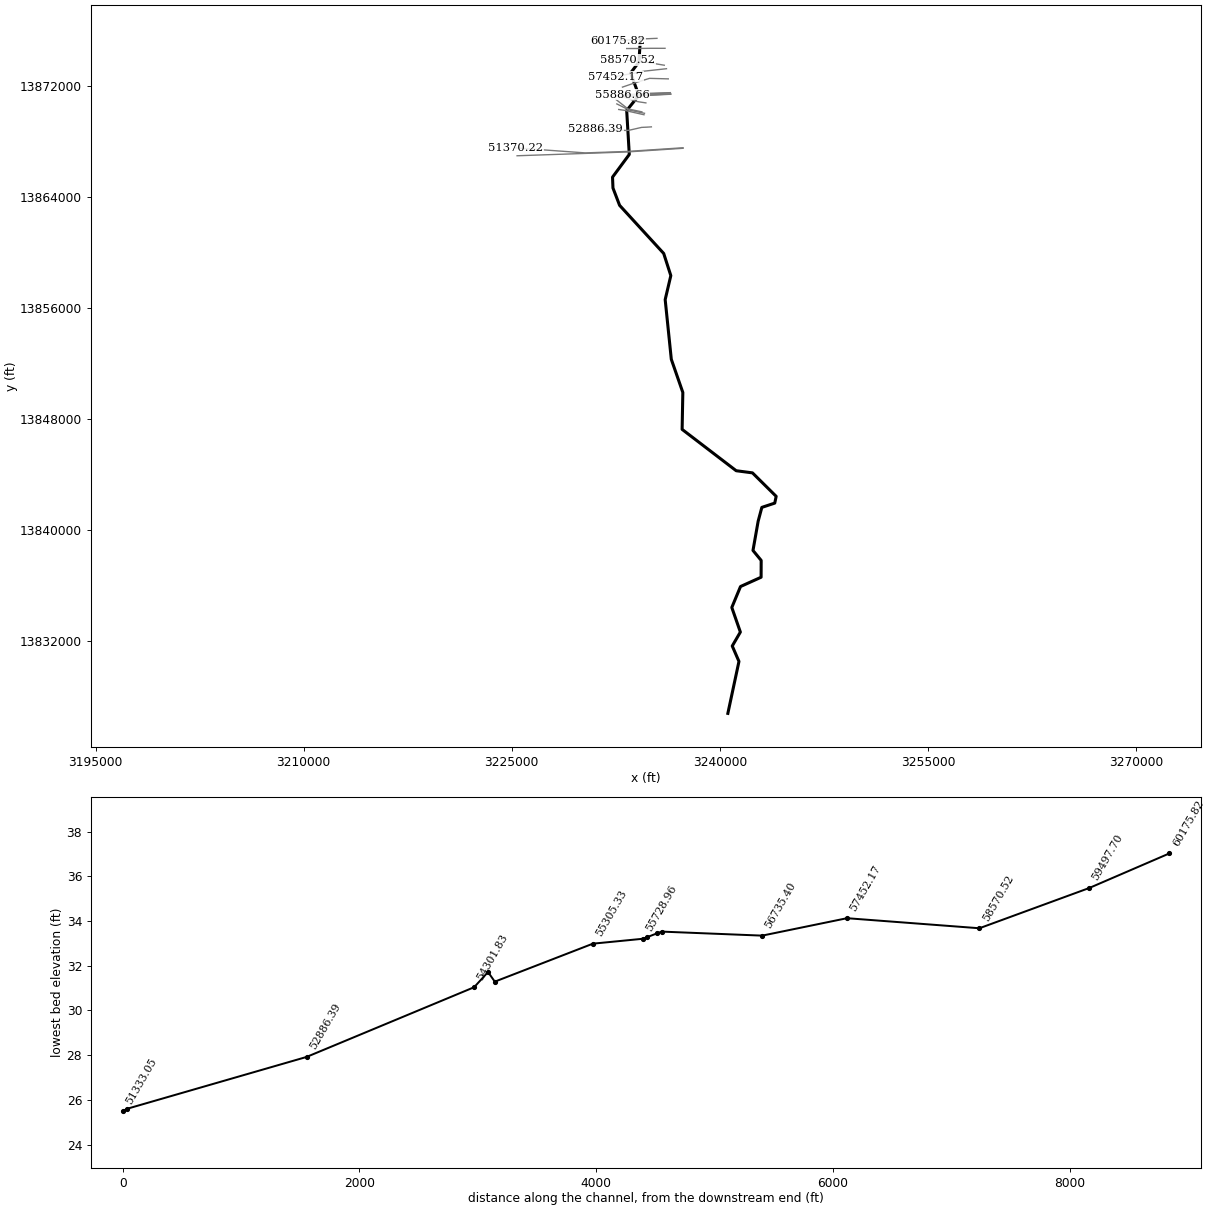
--- O100-00-00.prj (project) ---

Proj Title=O100-00-00
Current Plan=p02
Default Exp/Contr=.3,.1
English Units
Geom File=g01
Flow File=f01
Flow File=f02
Plan File=p01
Plan File=p02
Y Axis Title=Elevation
X Axis Title(PF)=Main Channel Distance
X Axis Title(XS)=Station
BEGIN DESCRIPTION:
HCFCD Watershed Unit ID: O
M3 Study Identifier: 2007_Effective_O
Engineer: HCFCD
Project Name: EffectiveFEMA Study for watershed Spring Gully & Goose Creek (O)
Study Completion Date: 6/18/2007
FEMA Case Number: [No Data]
FEMA Approval Date: [No Date in Database]
Vertical Datum: NAVD 1988
Datum Note: 2001 ADJ
HYDRAULICS
HCFCD Unit No.:  O100-00-00
Hydraulic Program Name: HEC-RAS
Hydraulic Program Version: 3.0.1
Steady Hydraulic Model: Yes
Unsteady Hydraulic Model: No
Update1:
The effective FEMA hydraulic model for unit number O100-00-00 has been updated by FEMA LOMR 11-06-4571P with an effective date of 1/22/2013.
Update 2:
The effective FEMA Hydraulic model for unit number O100-00-00 has been updated by FEMA LOMR 18-06-1537P with an effective date of 12/30/2019.
END DESCRIPTION:
DSS Export Rating Curves= 0
DSS Export Rating Curve Sorted= 0
DSS Export Volume Flow Curves= 0
DXF OffsetX= 0
DXF OffsetY= 0
DXF ScaleX= 1
DXF ScaleY= 10

--- O100-00-00.p02 (plan) ---

Plan Title=Effective FW 2019
Version=Version 3.0.1  May 2012
Short Identifier=Effective FW
Geom File=g01
Flow File=f02
Subcritical Flow
K Sum by GR= 0
Std Step Tol= 0.01
Critical Tol= 0.01
Num of Std Step Trials= 20
Max Error Tol= 0.3
Flow Tol Ratio= 0.001
Split Flow NTrial= 30
Split Flow Tol= 0.02
Split Flow Ratio= 0.02
Log Output Level= 0
Friction Slope Method= 1
Unsteady Friction Slope Method= 2
Parabolic Critical Depth
Global Vel Dist= 0 , 0 , 0
Global Log Level= 0
CheckData=True
Encroach Param=-1 ,0,0, 2
Encroach River=O100-00-00
Encroach Reach=O100-00-00_0004
Encroach Node=60175.82
       1    1500    2050
Encroach Node=59497.70
       1    1075    1575
Encroach Node=58570.52
       1    1650    2100
Encroach Node=57452.17
       1 2546.75    2785
Encroach Node=56735.40
       1 2357.74    2600
Encroach Node=55886.66
       1 2247.06 2291.32
Encroach Node=55846.11
       1 2239.12 2338.67
Encroach Node=55804
       1  2268.6 2338.09
Encroach Node=55762.56
       1  2268.6 2338.09
Encroach Node=55728.96
       1 2303.61 2347.87
Encroach Node=55305.33
       1  753.06  799.06
Encroach Node=54476.51
       1 1236.77 1275.46
Encroach Node=54419.67
       1 1266.71 1308.52
Encroach Node=54301.83
       11052.4631187.061
Encroach Node=52886.39
       1 1721.39    1965
Encroach Node=51370.22
       1    2018    2130
Encroach Node=51333.05
       1 2035.77  2085.6
Encroach Node=51294
       1 2032.77  2085.6
Encroach Node=51254.37
       1 2032.77  2082.6
Encroach Node=51230.58
       1  2016.5  2114.7
Encroach Node=49710.77
       1    2369    2800
Encroach Node=48332.01
       1    2480    2880
Encroach Node=48203.76
       1    2490    2900
Encroach Node=48123.90
       1    2565    2900
Encroach Node=48091.12
       1    2603    2855
Encroach Node=47881.40
       1 3093.33  3207.8
Encroach Node=47228.84
       1    3300    3939
Encroach Node=46202.00
       1    3250 4543.59
Encroach Node=44391.56
       1    6325    7575
Encroach Node=43569.15
       1    6550    7570
Encroach Node=43268.28
       1    6830    7580
Encroach Node=43158.13
       1    7840    8315
Encroach Node=42974
       1    7840    8315
Encroach Node=42789.76
       1    7610    8315
Encroach Node=42720.59
       1    7595    8325
Encroach Node=41478.09
       1    7500    8600
Encroach Node=40023.83
       1    7350    8650
Encroach Node=38699.08
       1    7780    8885
Encroach Node=37299.98
       1  4061.7 4239.92
Encroach Node=36174.64
       1    4212    4650
Encroach Node=35773.9*
       1    4212    4650
Encroach Node=35673.94
       1    3850    4849
Encroach Node=35638.41
       1    4180    4850
Encroach Node=35576
       1    4230    4850
Encroach Node=35513.81
       1    4230    5300
Encroach Node=35464.89
       1    4190    5300
Encroach Node=35064.8*
       1    4160    5300
Encroach Node=34680.08
       1    4130    5300
Encroach Node=34079.9*
       1    4050    4500
Encroach Node=33566.98
       1    3850    4200
Encroach Node=32632.43
       1 3436.89    3685
Encroach Node=31416.88
       1    3017    3157
Encroach Node=31375.70
       1 3049.09 3222.31
Encroach Node=31262
       1    3050    3220
Encroach Node=31147.49
       1 3068.74 3167.29
Encroach Node=31078.56
       1 3099.65 3241.55
Encroach Node=30102.79
       1    2814    2950
Encroach Node=30047.93
       1    2875    3135
Encroach Node=30031
       1    2875    3135
Encroach Node=30013.63
       1    2867    3150
Encroach Node=29957.42
       1    2840    3120
Encroach Node=29439.56
       1    1900    2280
Encroach Node=29384.92
       1    2980    3300
Encroach Node=29368
       1    2980    3300
Encroach Node=29349.69
       1    2980    3380
Encroach Node=29298.65
       1    3010    3400
Encroach Node=29134.90
       1 3513.89    3780
Encroach Node=29087.26
       1    4142    4400
Encroach Node=29070
       1    4142    4400
Encroach Node=29054.16
       1    4142    4400
Encroach Node=29000.79
       1    4170    4410
Encroach Node=28456.03
       1    2490    2692
Encroach Node=28413.12
       1    2485    2575
Encroach Node=28379.43
       1    2475    2590
Encroach Node=28335.01
       1 2364.84    2441
Encroach Node=28228.23
       1    2893 3051.65
Encroach Node=28049.41
       1    2804    2907
Encroach Node=26298.21
       1    2060 2236.04
Encroach Node=25528.51
       1     985    1205
Encroach Node=25211.57
       1 1938.34 2270.97
Encroach Node=25124
       1 1938.34    2299
Encroach Node=25036.23
       1    1939 2271.36
Encroach Node=24642.89
       1    2080    2290
Encroach Node=22909.39
       1     925    1165
Encroach Node=22518.42
       1     908    1229
Encroach Node=21577.73
       1  994.67 1304.52
Encroach Node=20650.97
       1  773.71    1274
Encroach Node=19592.46
       1     750    1550
Encroach Node=18737.16
       1     980    1361
Encroach Node=18678
       1     980    1361
Encroach Node=18619.03
       1     980    1361
Encroach Node=18457.98
       1     930 1321.75
Encroach Node=18315
       1     930    1315
Encroach Node=18171.62
       1     930 1321.75
Encroach Node=17584.26
       1     960    1439
Encroach Node=16742.72
       1  811.16    1178
Encroach Node=16286.76
       1     900    1410
Encroach Node=16079.39
       1 1112.75 1380.93
Encroach Node=16025
       1 1098.54 1380.93
Encroach Node=15970.78
       1 1098.54 1380.93
Encroach Node=15793.70
       1    1000    1500
Encroach Node=15478.79
       1  1065.9    1800
Encroach Node=15349.17
       1 1083.09    1800
Encroach Node=15160.44
       1    1173    1410
Encroach Node=15062
       1    1173    1410
Encroach Node=14964.32
       1    1173    1410
Encroach Node=14765.57
       1    1148    1542
Encroach Node=14430.99
       1 1251.18 1970.84
Encroach Node=13640.76
       1    1061    2018
Encroach Node=12835.88
       1  1316.7  1862.1
Encroach Node=12636.71
       1 1574.72  1785.8
Encroach Node=12560
       1 1574.72  1785.8
Encroach Node=12482.76
       1 1574.72  1785.8
Encroach Node=12319.55
       1 1432.53 1855.03
Encroach Node=11599.48
       1    1355  1992.5
Encroach Node=10358.25
       1  1029.6  1652.3
Encroach Node=9902.286
       1    1200    1700
Encroach Node=9686.740
       1    1150    1650
Encroach Node=9635.941
       1    1363    1640
Encroach Node=9483
       1    1363    1640
Encroach Node=9328.595
       1 1409.73    1640
Encroach Node=9120.931
       1 1789.24 2130.08
Encroach Node=8998
       1 1789.24 2130.08
Encroach Node=8873.815
       1 1789.24 2130.08
Encroach Node=8421.117
       1 1823.26 2447.32
Encroach Node=7867.529
       1 1857.92 2756.97
Encroach Node=7792
       1 1857.92 2756.97
Encroach Node=7715.169
       1 1857.92 2756.97
Encroach Node=6926.568
       1 1899.75 2641.78
Encroach Node=6337.928
       1  1910.4    2743
Encroach Node=5911.484
       1  3580.8 4347.67
Encroach Node=5829
       1  3580.8 4347.67
Encroach Node=5746.572
       1  3580.8 4347.67
Encroach Node=5251.147
       1    3960    4750
Encroach Node=4194.025
       1 3386.46 4102.16
Encroach Node=3006.149
       1 3681.19 4674.64
Encroach Node=2218.506
       1 3841.12 4973.95
Encroach Node=2091
       1 3841.12 4973.95
Encroach Node=1963.883
       1  4293.9 4839.11
Encroach Node=1587.638
       1 5768.49 7534.33
Encroach Node=411.220
       1 6166.77 7423.41
Computation Interval=1HOUR
Output Interval=1HOUR
Run HTab= 0
Run UNet= 0
Run PostProcess= 0
UNET Theta= 1
UNET ZTol= 0.02
UNET ZSATol= 0.05
UNET MxIter= 20
UNET MaxInSteps= 0
UNET DtIC= 0
UNET DtMin= 0
UNET MaxCRTS= 20
UNET WFStab= 2
UNET SFStab= 1
UNET WFX= 1
UNET SFX= 1
UNET Convert EG Bridges= 0
UNET Use Existing IB Tables=-1
Instantaneous Interval=1HOUR
Write IC File= 0
IC Time=0
Write Velocity= 0
Write Detailed= 0

--- O100-00-00.p01 (plan) ---

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Plan Title=Effective MP 2019
Short Identifier=Effective MP
Geom File=g01
Flow File=f01
Encroach Param=-1 ,0,0, 0

--- O100-00-00.f02 (steady flow) ---

Flow Title=Effective FW 2013
Program Version=4.10
Number of Profiles= 2
Profile Names=1PCT_100yr,1PCT_100yrFW
River Rch & RM=O100-00-00,O100-00-00_0004 ,60175.82
      92      92
River Rch & RM=O100-00-00,O100-00-00_0004 ,59497.70
     209     209
River Rch & RM=O100-00-00,O100-00-00_0004 ,58570.52
     290     290
River Rch & RM=O100-00-00,O100-00-00_0004 ,57452.17
     357     357
River Rch & RM=O100-00-00,O100-00-00_0004 ,56735.40
     458     458
River Rch & RM=O100-00-00,O100-00-00_0004 ,55886.66
     475     475
River Rch & RM=O100-00-00,O100-00-00_0004 ,55728.96
     525     525
River Rch & RM=O100-00-00,O100-00-00_0004 ,55305.33
     637     637
River Rch & RM=O100-00-00,O100-00-00_0004 ,54476.51
     645     645
River Rch & RM=O100-00-00,O100-00-00_0004 ,54419.67
     659     659
River Rch & RM=O100-00-00,O100-00-00_0004 ,54301.83
     852     852
River Rch & RM=O100-00-00,O100-00-00_0004 ,52886.39
     872     872
River Rch & RM=O100-00-00,O100-00-00_0004 ,51370.22
     874     874
River Rch & RM=O100-00-00,O100-00-00_0004 ,51230.58
     894     894
River Rch & RM=O100-00-00,O100-00-00_0004 ,49710.77
     913     913
River Rch & RM=O100-00-00,O100-00-00_0004 ,48332.01
    1956    1956
River Rch & RM=O100-00-00,O100-00-00_0004 ,48123.90
    1970    1970
River Rch & RM=O100-00-00,O100-00-00_0004 ,47881.40
    1970    1970
River Rch & RM=O100-00-00,O100-00-00_0004 ,47228.84
    1970    1970
River Rch & RM=O100-00-00,O100-00-00_0004 ,46202.00
    2314    2314
River Rch & RM=O100-00-00,O100-00-00_0004 ,44391.56
    2919    2919
River Rch & RM=O100-00-00,O100-00-00_0004 ,43569.15
    3194    3194
River Rch & RM=O100-00-00,O100-00-00_0004 ,43268.28
    3295    3295
River Rch & RM=O100-00-00,O100-00-00_0004 ,42720.59
    3480    3480
River Rch & RM=O100-00-00,O100-00-00_0004 ,41478.09
    3480    3480
River Rch & RM=O100-00-00,O100-00-00_0004 ,40023.83
    3929    3929
River Rch & RM=O100-00-00,O100-00-00_0004 ,38699.08
    4339    4339
River Rch & RM=O100-00-00,O100-00-00_0004 ,37299.98
    4442    4442
River Rch & RM=O100-00-00,O100-00-00_0004 ,36174.64
    4526    4526
River Rch & RM=O100-00-00,O100-00-00_0004 ,35673.94
    4563    4563
River Rch & RM=O100-00-00,O100-00-00_0004 ,34680.08
    4637    4637
River Rch & RM=O100-00-00,O100-00-00_0004 ,33566.98
    4720    4720
River Rch & RM=O100-00-00,O100-00-00_0004 ,32632.43
    4850    4850
River Rch & RM=O100-00-00,O100-00-00_0004 ,31416.88
    5020    5020
River Rch & RM=O100-00-00,O100-00-00_0004 ,31375.70
    5026    5026
River Rch & RM=O100-00-00,O100-00-00_0004 ,31078.56
    5083    5083
River Rch & RM=O100-00-00,O100-00-00_0004 ,30047.93
    5454    5454
River Rch & RM=O100-00-00,O100-00-00_0004 ,29957.42
    5487    5487
River Rch & RM=O100-00-00,O100-00-00_0004 ,29298.65
    5724    5724
River Rch & RM=O100-00-00,O100-00-00_0004 ,29000.79
    5831    5831
River Rch & RM=O100-00-00,O100-00-00_0004 ,28049.41
    6174    6174
River Rch & RM=O100-00-00,O100-00-00_0004 ,26298.21
    6804    6804
River Rch & RM=O100-00-00,O100-00-00_0004 ,24642.89
    7915    7915
River Rch & RM=O100-00-00,O100-00-00_0004 ,22909.39
    9079    9079
River Rch & RM=O100-00-00,O100-00-00_0004 ,21577.73
    9972    9972
River Rch & RM=O100-00-00,O100-00-00_0004 ,20650.97
   10595   10595
River Rch & RM=O100-00-00,O100-00-00_0004 ,19592.46
   11305   11305
River Rch & RM=O100-00-00,O100-00-00_0004 ,17584.26
   11967   11967
River Rch & RM=O100-00-00,O100-00-00_0004 ,14430.99
   12578   12578
River Rch & RM=O100-00-00,O100-00-00_0004 ,12835.88
   12887   12887
River Rch & RM=O100-00-00,O100-00-00_0004 ,10358.25
   13368   13368
River Rch & RM=O100-00-00,O100-00-00_0004 ,8421.117
   13743   13743
River Rch & RM=O100-00-00,O100-00-00_0004 ,5251.147
   14358   14358
River Rch & RM=O100-00-00,O100-00-00_0004 ,3006.149
   14793   14793
River Rch & RM=O100-00-00,O100-00-00_0004 ,1963.883
   14995   14995
Boundary for River Rch & Prof#=O100-00-00,O100-00-00_0004 , 1
Up Type= 0
Dn Type= 1
Dn Known WS=1.5
Boundary for River Rch & Prof#=O100-00-00,O100-00-00_0004 , 2
Up Type= 0
Dn Type= 1
Dn Known WS=1.5
DSS Import GetInterval= 0
DSS Import GetPeak= 0
DSS Import FillOption= 0

--- O100-00-00.f01 (steady flow) ---

Flow Title=Effective MP 2013
Version=Version 3.0.1  Mar 2001
Number of Profiles= 4
Profile Names=10PCT_10yr, 2PCT_50yr, 1PCT_100yr, 0.2PCT_500yr
River Rch & RM=O100-00-00,O100-00-00_0004 ,60175.82
      51      78      92     132
River Rch & RM=O100-00-00,O100-00-00_0004 ,59497.70
     117     178     209     302
River Rch & RM=O100-00-00,O100-00-00_0004 ,58570.52
     163     246     290     418
River Rch & RM=O100-00-00,O100-00-00_0004 ,57452.17
     201     304     357     516
River Rch & RM=O100-00-00,O100-00-00_0004 ,56735.40
     257     389     458     661
River Rch & RM=O100-00-00,O100-00-00_0004 ,55886.66
     267     404     475     686
River Rch & RM=O100-00-00,O100-00-00_0004 ,55728.96
     295     446     525     757
River Rch & RM=O100-00-00,O100-00-00_0004 ,55305.33
     358     541     637     919
River Rch & RM=O100-00-00,O100-00-00_0004 ,54476.51
     362     549     645     931
River Rch & RM=O100-00-00,O100-00-00_0004 ,54419.67
     370     560     659     951
River Rch & RM=O100-00-00,O100-00-00_0004 ,54301.83
     478     724     852    1229
River Rch & RM=O100-00-00,O100-00-00_0004 ,52886.39
     490     741     872    1258
River Rch & RM=O100-00-00,O100-00-00_0004 ,51370.22
     491     743     874    1261
River Rch & RM=O100-00-00,O100-00-00_0004 ,51230.58
     502     760     894    1290
River Rch & RM=O100-00-00,O100-00-00_0004 ,49710.77
     513     776     913    1318
River Rch & RM=O100-00-00,O100-00-00_0004 ,48332.01
    1018    1549    1956    2992
River Rch & RM=O100-00-00,O100-00-00_0004 ,48123.90
    1127    1667    1970    2693
River Rch & RM=O100-00-00,O100-00-00_0004 ,47881.40
    1127    1667    1970    2693
River Rch & RM=O100-00-00,O100-00-00_0004 ,47228.84
    1127    1667    1970    2693
River Rch & RM=O100-00-00,O100-00-00_0004 ,46202.00
    1318    1954    2314    3193
River Rch & RM=O100-00-00,O100-00-00_0004 ,44391.56
    1654    2461    2919    4074
River Rch & RM=O100-00-00,O100-00-00_0004 ,43569.15
    1807    2690    3194    4475
River Rch & RM=O100-00-00,O100-00-00_0004 ,43268.28
    1863    2775    3295    4621
River Rch & RM=O100-00-00,O100-00-00_0004 ,42720.59
    2173    3007    3480    4703
River Rch & RM=O100-00-00,O100-00-00_0004 ,41478.09
    2173    3007    3480    4703
River Rch & RM=O100-00-00,O100-00-00_0004 ,40023.83
    2463    3400    3929    5318
River Rch & RM=O100-00-00,O100-00-00_0004 ,38699.08
    2728    3758    4339    5878
River Rch & RM=O100-00-00,O100-00-00_0004 ,37299.98
    2841    3878    4442    5927
River Rch & RM=O100-00-00,O100-00-00_0004 ,36174.64
    2932    3974    4526    5966
River Rch & RM=O100-00-00,O100-00-00_0004 ,35673.94
    2973    4017    4563    5984
River Rch & RM=O100-00-00,O100-00-00_0004 ,34680.08
    3053    4102    4637    6018
River Rch & RM=O100-00-00,O100-00-00_0004 ,33566.98
    3144    4197    4720    6057
River Rch & RM=O100-00-00,O100-00-00_0004 ,32632.43
    3340    4305    4850    6149
River Rch & RM=O100-00-00,O100-00-00_0004 ,31416.88
    3595    4445    5020    6270
River Rch & RM=O100-00-00,O100-00-00_0004 ,31375.70
    3603    4450    5026    6274
River Rch & RM=O100-00-00,O100-00-00_0004 ,31078.56
    3666    4500    5083    6331
River Rch & RM=O100-00-00,O100-00-00_0004 ,30047.93
    3889    4858    5454    6847
River Rch & RM=O100-00-00,O100-00-00_0004 ,29957.42
    3909    4890    5487    6892
River Rch & RM=O100-00-00,O100-00-00_0004 ,29298.65
    4052    5118    5724    7222
River Rch & RM=O100-00-00,O100-00-00_0004 ,29000.79
    4116    5221    5831    7372
River Rch & RM=O100-00-00,O100-00-00_0004 ,28049.41
    4323    5552    6174    7848
River Rch & RM=O100-00-00,O100-00-00_0004 ,26298.21
    4702    6159    6804    8725
River Rch & RM=O100-00-00,O100-00-00_0004 ,24642.89
    5288    7097    7915   10273
River Rch & RM=O100-00-00,O100-00-00_0004 ,22909.39
    5902    8079    9079   11895
River Rch & RM=O100-00-00,O100-00-00_0004 ,21577.73
    6374    8834    9972   13140
River Rch & RM=O100-00-00,O100-00-00_0004 ,20650.97
    6702    9359   10595   14007
River Rch & RM=O100-00-00,O100-00-00_0004 ,19592.46
    7077    9958   11305   14997
River Rch & RM=O100-00-00,O100-00-00_0004 ,17584.26
    7420   10516   11967   15959
River Rch & RM=O100-00-00,O100-00-00_0004 ,14430.99
    7726   11028   12578   16921
River Rch & RM=O100-00-00,O100-00-00_0004 ,12835.88
    7881   11287   12887   17408
River Rch & RM=O100-00-00,O100-00-00_0004 ,10358.25
    8122   11690   13368   18164
River Rch & RM=O100-00-00,O100-00-00_0004 ,8421.117
    8310   12005   13743   18755
River Rch & RM=O100-00-00,O100-00-00_0004 ,5251.147
    8618   12520   14358   19722
River Rch & RM=O100-00-00,O100-00-00_0004 ,3006.149
    8836   12885   14793   20407
River Rch & RM=O100-00-00,O100-00-00_0004 ,1963.883
    8937   13054   14995   20725
Boundary for River Rch & Prof#=O100-00-00,O100-00-00_0004 , 1
Up Type= 0
Dn Type= 1
Dn Known WS=1.5
Boundary for River Rch & Prof#=O100-00-00,O100-00-00_0004 , 2
Up Type= 0
Dn Type= 1
Dn Known WS=1.5
Boundary for River Rch & Prof#=O100-00-00,O100-00-00_0004 , 3
Up Type= 0
Dn Type= 1
Dn Known WS=1.5
Boundary for River Rch & Prof#=O100-00-00,O100-00-00_0004 , 4
Up Type= 0
Dn Type= 1
Dn Known WS=1.5
DSS Import GetInterval= 0
DSS Import GetPeak= 0
DSS Import FillOption= 0

--- O100-00-00.g01 (geometry) ---

Geom Title=O100-00-00 2019
Version=Version 3.0.1  May 2012

River Reach=O100-00-00      ,O100-00-00_0004
Reach XY= 30
     3234268.943    13875399.247     3234165.521    13873733.982
     3233567.779     13872943.42     3234158.509    13871327.237
     3233282.281     13870236.41     3233469.616    13867067.665
      3232261.86    13865433.953     3232293.413    13864648.649
     3232771.957    13863400.577     3235949.699    13859932.569
     3236463.586    13858334.667     3236056.911    13856604.545
     3236498.644    13852302.903     3237329.524    13849911.934
     3237278.497    13847251.019     3241175.012    13844270.939
     3242348.803    13844116.419     3244057.478    13842423.907
     3243954.904    13841936.395     3243025.132    13841628.408
     3242758.384     13840630.36     3242386.068    13838524.112
     3242976.455    13837806.073     3242971.136    13836593.385
     3241487.189    13835923.215      3240859.57    13834412.674
     3241476.551    13832641.511     3240891.483    13831636.256
     3241375.494    13830524.625     3240574.524    13826779.924

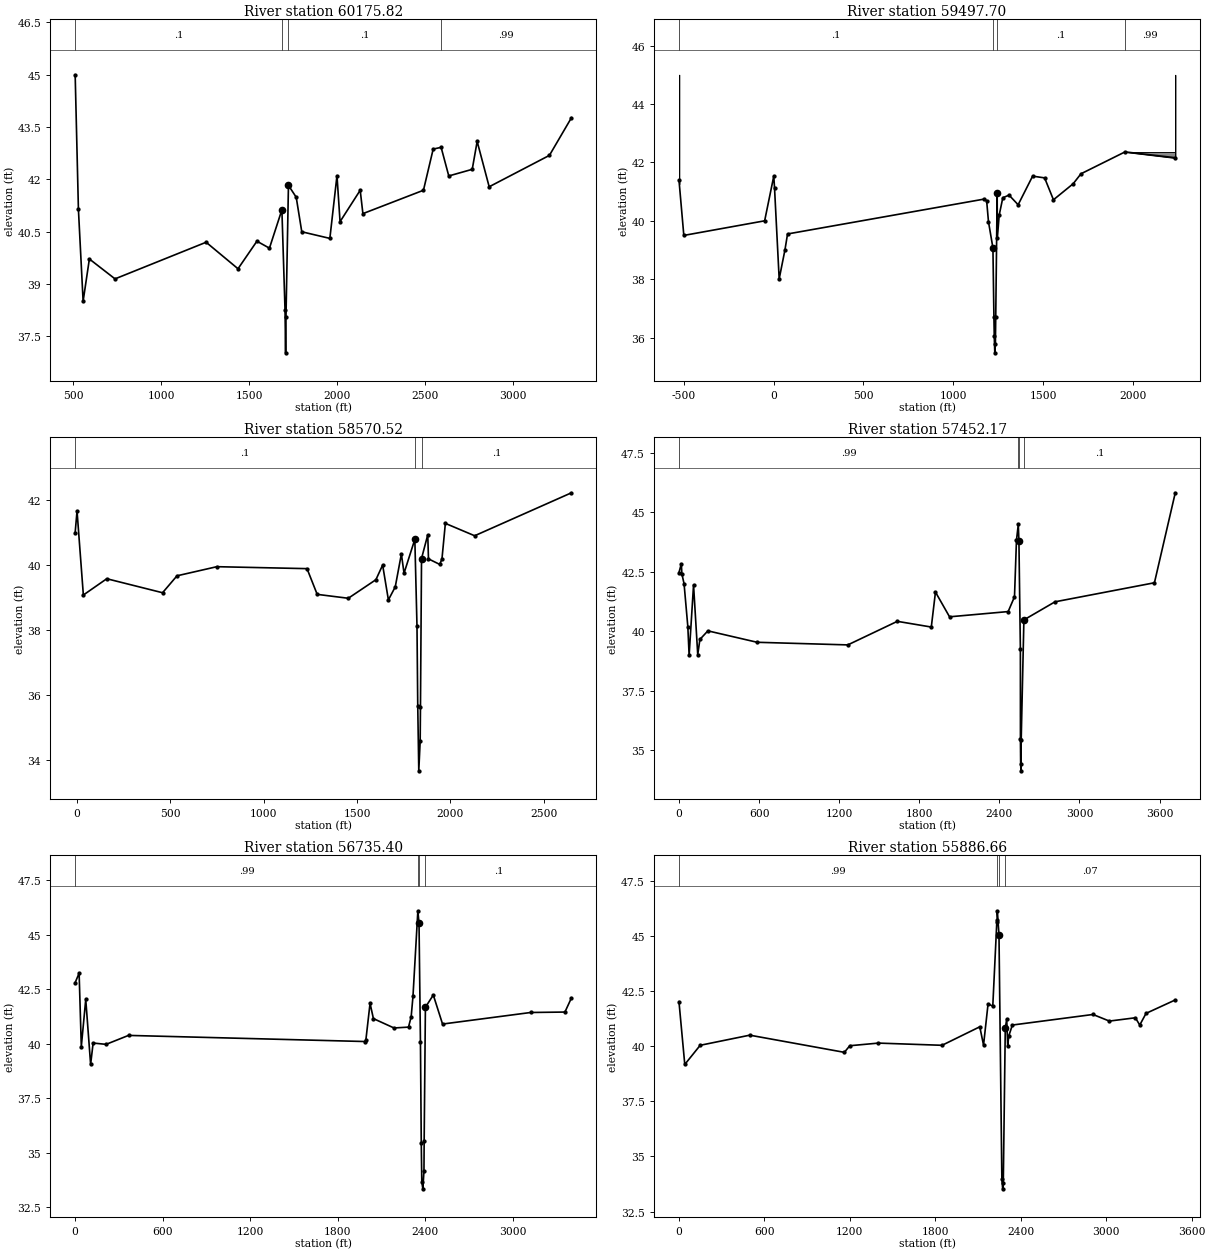
Type RM Length L Ch R = 1 ,60175.82,932.19,678.12,678.12
BEGIN DESCRIPTION:
451v51
Bank Station offset =      3293
LOB cannot be extended to required elevation due to lack of high points.
Roadway exists at station 511, which will serve as the block for the left overbank
END DESCRIPTION:
XS GIS Cut Line= 5
 3235464.667973813875438.5095559 3235446.203253713875437.7586957
     3234317.071    13875391.843     3234236.043    13875381.203
      3232648.99    13875266.446
#Sta/Elev= 30
     511      45  529.48   41.14   556.2   38.51  591.75   39.72  737.57   39.15
 1255.42    40.2 1436.74   39.44 1544.25   40.23 1615.45   40.03 1686.23   41.13
 1704.08   38.25 1707.37   37.03 1709.46   38.06 1723.52   41.83 1767.66   41.49
 1799.27    40.5 1958.89   40.31 1999.39   42.11 2016.84   40.79 2131.41   41.69
 2146.76   41.02 2490.97   41.69 2546.31   42.87 2591.45   42.92 2634.94    42.1
  2768.3   42.29 2796.28   43.09 2864.62   41.79 3207.14   42.69 3332.47   43.77
#Mann= 4 ,-1 , 0
     511      .1       0 1686.23     .06       0 1723.52      .1       0
 2591.45     .99       0
Bank Sta=1686.23,1723.52
XS Rating Curve= 0
Exp/Cntr=.3,.1

Type RM Length L Ch R = 1 ,59497.70,935.2,927.18,921.74
BEGIN DESCRIPTION:
451v50
Bank Station offset =      3769
extension on left overbank is 527' to road at elev 41.4
Cross section blocked at edge of watershed on LOB
END DESCRIPTION:
XS GIS Cut Line= 6
 3236046.843950713874719.9009446     3235519.844    13874720.129
     3234992.972    13874720.357     3234320.679    13874709.973
     3234279.097    13874707.148     3233283.828    13874702.854
#Sta/Elev= 30
    -527    41.4    -500    39.5     -50      40     .86   41.53    4.99   41.13
   30.86   38.01    62.9      39   77.48   39.55 1168.53   40.74 1185.94   40.69
 1196.17   39.97 1220.97   39.07 1226.49   36.71 1228.32   36.07 1231.32   35.48
 1234.68   35.79 1236.56   36.69 1244.55   40.95 1245.56   39.41 1255.96    40.2
 1276.04   40.79 1310.72   40.88  1361.3   40.55 1441.96   41.53 1508.71   41.47
 1557.97   40.72 1667.89   41.27 1711.11   41.61 1956.55   42.36  2236.2   42.16
#Mann= 4 ,-1 , 0
    -527      .1       0 1220.97     .06       0 1244.55      .1       0
 1956.55     .99       0
#Block Obstruct= 3 ,-1
    -527    -525      45 1956.55  2236.2   42.36    2236  2236.2      45
Bank Sta=1220.97,1244.55
XS Rating Curve= 0
Exp/Cntr=.3,.1

Type RM Length L Ch R = 1 ,58570.52,1113.59,1118.35,1123.56
BEGIN DESCRIPTION:
451v49
Cross section blocked at edge of watershed on LOB
Cross section extended on ROB
Bank Station offset =      3170
END DESCRIPTION:
XS GIS Cut Line= 6
 3235992.846777213873500.1462301     3234687.958    13873720.999
      3234248.43     13873780.36     3234130.405    13873793.169
     3233406.897    13873867.745 3233362.154078813873872.3569021
#Sta/Elev= 30
     -10      41       0   41.66   33.84   39.08  159.27   39.58  457.99   39.15
  535.41   39.67  748.91   39.95 1231.69   39.89 1286.18    39.1 1452.66   38.98
 1600.55   39.55 1636.71      40 1667.51   38.93 1704.26   39.33 1737.06   40.34
 1751.27   39.75  1809.1   40.79 1820.63   38.13 1824.73   35.67 1830.25   33.68
 1837.69   34.59 1839.29   35.64 1844.96    40.2 1878.34   40.93 1882.14   40.19
 1942.46   40.02 1954.43   40.19 1972.61   41.28 2129.45    40.9    2648   42.22
#Mann= 3 ,-1 , 0
     -10      .1       0  1809.1     .06       0 1844.96      .1       0
#Block Obstruct= 2 , 0
       0       0      43    2647       0      45
Bank Sta=1809.1,1844.96
XS Rating Curve= 0
Exp/Cntr=.3,.1

Type RM Length L Ch R = 1 ,57452.17,711.94,716.77,720.34
BEGIN DESCRIPTION:
451v48
Assigned n = 0.99 to flow on LOB.  Flow is not effective from the u/s reach through the Fig Orchard rd culvert outside high ground on near bank.   Based on ground elevations, flow cannot enter the channel between the u/s most section of the studied channel and this section.
Cross section extended on ROB
Bank Station offset =      2438
END DESCRIPTION:
XS GIS Cut Line= 6
     3236149.592    13873248.785     3234541.597    13873072.826
     3233635.132    13872885.732      3233529.43    13872881.966
     3232633.323    13872707.384 3232480.093786113872677.5314683
#Sta/Elev= 30
       0   42.46   17.65   42.83   21.88    42.4   38.15   41.99   66.31   40.19
   76.06   38.98   109.2   41.94  140.62   39.01  156.76   39.65   216.5   40.01
   585.7   39.53 1264.91   39.42 1635.76   40.41 1890.28   40.17 1921.48   41.64
 2026.92    40.6 2466.12   40.82 2513.54   41.44 2528.23   43.81 2541.96   44.48
 2546.75   43.77 2557.65   39.23    2558   35.46 2559.63   34.42  2561.8   34.13
 2563.77   35.44 2583.99   40.47 2817.09   41.23 3561.89   42.03    3718   45.81
#Mann= 4 ,-1 , 0
       0     .99       0 2541.96      .1       0 2546.75     .06       0
 2583.99      .1       0
Bank Sta=2546.75,2583.99
XS Rating Curve= 0
Exp/Cntr=.3,.1

Type RM Length L Ch R = 1 ,56735.40,850.62,848.73,844.57
BEGIN DESCRIPTION:
451v47
Assigned n = 0.99 to flow on LOB and ROB.  Flow is not effective from the u/s reach through the Fig Orchard rd culvert outside high ground on near bank.   Based on ground elevations, flow cannot enter the channel between the u/s most section of the studied channel and this section.
Cross section extended by 35' on ROB
Bank Station offset =      2616
END DESCRIPTION:
XS GIS Cut Line= 6
     3236281.108    13872516.505      3234931.03    13872553.597
     3233969.691    13872259.845     3233913.416    13872243.849
     3233011.319     13871933.81 3232978.408422713871922.4990628
#Sta/Elev= 30
       0    42.8   27.08   43.23   42.14   39.87   72.52   42.03  105.99   39.05
  123.11   40.03  212.14   39.97  365.76   40.38  1984.2    40.1 1992.95   40.15
 2021.94   41.85 2044.88   41.15 2186.27   40.72 2285.58   40.76  2303.8   41.23
 2316.26   42.17 2349.77   46.09 2357.74   45.51 2367.46   40.06 2373.08   35.47
 2376.69   33.68 2384.04   33.35 2391.55   34.17 2392.91   35.53 2401.49   41.67
 2455.59   42.23 2519.06    40.9 3123.48   41.43 3358.13   41.45    3403    42.1
#Mann= 4 ,-1 , 0
       0     .99       0 2349.77      .1       0 2357.74     .06       0
 2401.49      .1       0
#Block Obstruct= 2 , 0
       0                    3402       0      44
Bank Sta=2357.74,2401.49
XS Rating Curve= 0
Exp/Cntr=.3,.1

Type RM Length L Ch R = 1 ,55886.66,39.94,40.56,42.64
BEGIN DESCRIPTION:
451s25u - xs 4/4 Fig Orchard rd
Assigned n = 0.99 to flow on LOB and ROB.  Flow is not effective from the u/s reach through the Fig Orchard rd culvert outside high ground on near bank.   Based on ground elevations, flow cannot enter the channel between the u/s most section of the studied channel and this section.
Cross section extended on ROB by 185'
Bank Station offset =      2727
END DESCRIPTION:
XS GIS Cut Line= 6
     3236429.729     13871523.02      3234872.18    13871475.143
     3234190.776     13871438.78     3234134.886    13871428.292
     3233134.388     13871371.21 3232949.338835513871360.6522813
#Sta/Elev= 30
       0   42.03   40.76   39.18  148.97   40.05  497.08   40.51 1161.36   39.73
  1199.4   40.03 1400.18   40.15 1847.35   40.05 2112.27   40.89 2138.64   40.06
 2170.41   41.93 2203.58   41.83 2231.75   45.64 2234.36   45.73 2235.07   46.16
 2247.06   45.08 2267.38   33.96 2273.36   33.53 2277.29   33.79 2291.32   40.82
 2301.39   41.24 2308.44      40 2315.15   40.46 2341.09   40.97 2907.08   41.45
 3022.17   41.15 3204.83    41.3 3235.61   40.97 3279.73    41.5    3485   42.11
#Mann= 4 ,-1 , 0
       0     .99       0 2235.07     .07       0 2247.06     .06       0
 2291.32     .07       0
Bank Sta=2247.06,2291.32
XS Rating Curve= 0
Exp/Cntr=.5,.3

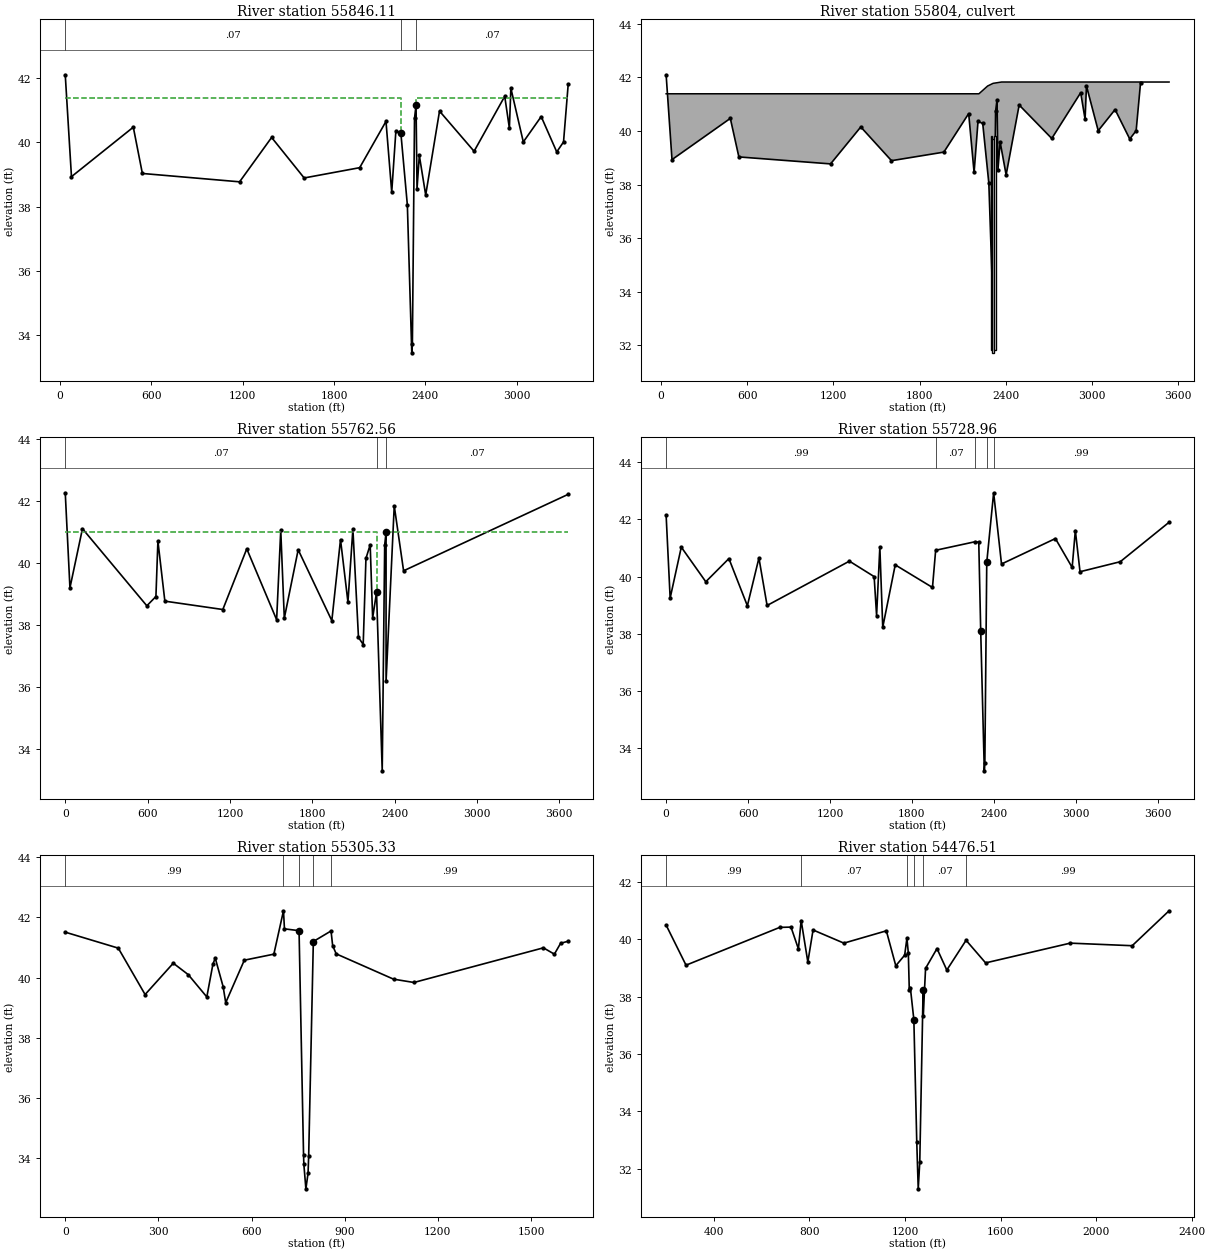
Type RM Length L Ch R = 1 ,55846.11,82.43,83.55,83.16
BEGIN DESCRIPTION:
Copy of 451s25u - xs 3/4 Fig Orchard rd
Bank Station offset =      2725
high point deleted from copied section, only exists at location of survey section
END DESCRIPTION:
XS GIS Cut Line= 5
     3236429.729    13871501.782     3234872.465    13871434.419
     3234189.616    13871397.978     3234133.726     13871387.49
     3233133.228    13871330.409
#Sta/Elev= 30
      36    42.1   76.78   38.93  482.72   40.47  542.22   39.03 1180.38   38.77
  1390.6   40.15 1604.22   38.89 1968.73   39.21 2141.34   40.65 2179.03   38.45
 2206.38   40.36 2239.12   40.28 2281.62   38.05 2310.64   33.45 2314.57   33.71
  2328.6   40.74 2338.67   41.16 2345.16   38.56 2360.19   39.59 2402.01   38.36
 2492.74   40.97 2719.64   39.72 2920.83   41.43 2951.35   40.44 2961.16   41.68
 3042.77   40.01 3160.19    40.8 3262.28    39.7 3306.76   40.01 3337.53   41.81
#Mann= 3 , 0 , 0
      36     .07       0 2239.12     .06       0 2338.67     .07       0
#XS Ineff= 2 , 0
      36 2239.12   41.39 2338.67      36   41.39
Permanent Ineff=
       F       F
#Block Obstruct= 2 , 0
       0                    3337       0      43
Bank Sta=2239.12,2338.67
XS Rating Curve= 0
Exp/Cntr=.5,.3

Type RM Length L Ch R = 2 ,55804   ,,,
BEGIN DESCRIPTION:
451s25: Fig Orchard Rd "3 - 10' x 8' conc. box culverts"
END DESCRIPTION:
Bridge Culvert--1,0,-1,-1, 0
Deck Dist Width WeirC Skew NumUp NumDn MinLoCord MaxHiCord MaxSubmerge Is_Ogee
31.75,20,2.6,0, 6, 6, , , .95, 0, 0,0,,
      36 2212.61 2272.95    2311 2370.55    3536
   41.39   41.39   41.68   41.78   41.83   41.83
                                                
       0 2211.61 2271.95    2310 2369.55 3665.57
   41.39   41.39   41.68   41.78   41.83   41.83
                                                
BR Coef=-1 , 0 , 0 ,, 0 ,,,.8,0,,0,
WSPro=,,,, 1 ,,,, 0 ,,,, 0 ,,,,-1 ,-1 ,-1 , 0 , 0 , 0 , 0 , 0
Culvert=2,8,10,37,.012,.5,1,10,1,31.82,2298.3,31.8,2297.3,Culvert #1  , 0 ,23
Culvert Bottom n=.012
Culvert=2,8,10,37,.012,.5,1,10,1,31.71,2311,31.55,2310,Culvert #2  , 0 ,23
Culvert Bottom n=.012
Culvert=2,8,10,37,.012,.5,1,10,1,31.8,2323.7,31.9,2322.7,Culvert #3  , 0 ,23
Culvert Bottom n=.012
BC Design=,, 0 ,, 0 ,,,,,,
BC HTab HWMax=42.1

Type RM Length L Ch R = 1 ,55762.56,32.71,33.6,27.74
BEGIN DESCRIPTION:
Copy of 451s25u - xs 2/4 Fig Orchard rd
Bank Station offset =      2690
high point deleted from copied section, only exists at location of survey section
END DESCRIPTION:
XS GIS Cut Line= 6
     3236458.047    13871423.909     3234865.142    13871354.032
     3234175.834    13871317.247     3234119.943    13871306.758
     3233119.445    13871249.677 3232798.1174377 13871231.344431
#Sta/Elev= 30
       0   42.26   34.17   39.19   125.4    41.1  594.63   38.61  660.82   38.91
  675.29    40.7  725.98   38.76 1148.36   38.49 1322.86   40.45 1540.54   38.16
 1570.57   41.05 1596.46   38.21 1697.57   40.42 1942.82   38.13 2006.08   40.75
 2060.22   38.73 2096.31   41.09 2136.98   37.59 2171.41   37.36 2191.46   40.14
  2222.3   40.58 2240.22   38.22  2268.6   39.04 2310.06   33.28 2328.02   40.57
 2338.09   40.99  2338.1   36.17 2397.64   41.84 2465.75   39.74 3665.57   42.21
#Mann= 3 ,-1 , 0
       0     .07       0  2268.6     .06       0 2338.09     .07       0
#XS Ineff= 2 , 0
       0  2268.6      41 2338.09       0      41
Permanent Ineff=
       F       F
Bank Sta=2268.6,2338.09
XS Rating Curve= 0
Exp/Cntr=.5,.3

Type RM Length L Ch R = 1 ,55728.96,442.21,423.64,394.08
BEGIN DESCRIPTION:
Copy of 451s25u - xs 1/4 Fig Orchard rd
Bank Station offset =      2670
high point deleted from copied section, only exists at location of survey section.  Manning's n set at 0.99 on overbank for this section due to high ground - flow is not anticipated to be effective on ROB.
END DESCRIPTION:
XS GIS Cut Line= 6
     3236458.047     13871409.75     3234836.834    13871325.528
     3234162.156    13871289.523     3234106.265    13871279.035
     3233105.767    13871221.953 3232781.3246484   13871203.4424
#Sta/Elev= 30
       0   42.14   29.44   39.25  111.01   41.03  290.46   39.82  459.68   40.63
  594.86   38.98  679.52   40.65  739.26   38.99 1342.01   40.54 1523.17      40
 1541.14   38.64 1564.96   41.03  1586.2   38.23 1677.64   40.41 1950.35   39.62
 1973.66   40.92 2263.67   41.22 2289.35    41.2 2303.61   38.09 2329.91   33.21
 2333.84   33.47 2347.87    40.5 2398.25   42.93 2455.81   40.44 2850.51   41.33
 2973.19   40.32 2996.48   41.61 3030.78   40.17 3325.36   40.52    3683    41.9
#Mann= 5 ,-1 , 0
       0     .99       0 1973.66     .07       0 2263.67     .06       0
 2347.87     .07       0 2398.25     .99       0
#Block Obstruct= 2 , 0
       0                    3672       0      43
Bank Sta=2303.61,2347.87
XS Rating Curve= 0
Exp/Cntr=.3,.1

Type RM Length L Ch R = 1 ,55305.33,828.41,828.82,818.96
BEGIN DESCRIPTION:
451v46
Bank Station offset =      4225
ROB extended by 45' to required elevation to contain 500 yr profile.  Added n = 0.99 at ineffective areas due to constriction of flow to channel further in downstream sections.
END DESCRIPTION:
XS GIS Cut Line= 6
     3234666.548    13870785.276      3234155.44    13870862.062
     3233965.465      13870903.6     3233833.816    13870950.427
     3233143.178    13871169.026  3233100.69519113871182.4725518
#Sta/Elev= 30
       0   41.51  170.84   40.98  257.16   39.44  347.96   40.48  396.22    40.1
  455.98   39.36  475.66   40.45  483.08   40.65  508.55    39.7  516.84   39.17
  576.75   40.58  671.88   40.78  702.89   42.22  706.06   41.62  753.06   41.56
  767.56    34.1  768.56    33.8  775.06   32.99  782.06   33.51  784.06   34.09
  799.06    41.2  856.06   41.55  861.35   41.06  872.75   40.79 1057.42   39.95
 1123.07   39.84 1540.09   40.99 1575.44   40.78 1595.44   41.14    1620   41.21
#Mann= 5 ,-1 , 0
       0     .99       0  702.89     .07       0  753.06     .06       0
  799.06     .07       0  856.06     .99       0
#Block Obstruct= 2 , 0
       0       0      43    1619       0      43
Bank Sta=753.06,799.06
XS Rating Curve= 0
Exp/Cntr=.3,.1

Type RM Length L Ch R = 1 ,54476.51,78.44,56.84,53.38
BEGIN DESCRIPTION:
451v45
Bank Station offset =      3745
LOB extension to elevation 41 assumed to occur at bank of elevation channel; ROB extension measured from TIN
END DESCRIPTION:
XS GIS Cut Line= 6
 3234380.4309889 13870138.207447 3234357.602370613870143.0664196
     3233377.622    13870351.651      3233339.72    13870379.266
     3232624.532     13870940.47 3232527.184762413871016.8578297
#Sta/Elev= 30
     200    40.5  283.27    39.1   675.5   40.42  722.61   40.43  753.58   39.67
  765.16   40.66  793.12   39.21  814.92   40.33  943.93   39.87 1121.64    40.3
 1161.21   39.08 1198.32   39.45 1207.73   40.04 1213.66   39.53 1217.68   38.23
 1222.07   38.32 1236.77    37.2 1248.99   32.91  1255.1   31.29 1261.53   32.23
 1275.46   38.23 1276.04   37.32 1285.81   38.99 1333.61   39.68  1374.7   38.93
 1455.32   39.97  1537.1   39.18  1891.3   39.87 2150.51   39.78    2305      41
#Mann= 6 ,-1 , 0
     200     .99       0  765.16     .07       0 1207.73     .07       0
 1236.77     .06       0 1275.46     .07       0 1455.32     .99       0
Bank Sta=1236.77,1275.46
XS Rating Curve= 0
Exp/Cntr=.3,.1

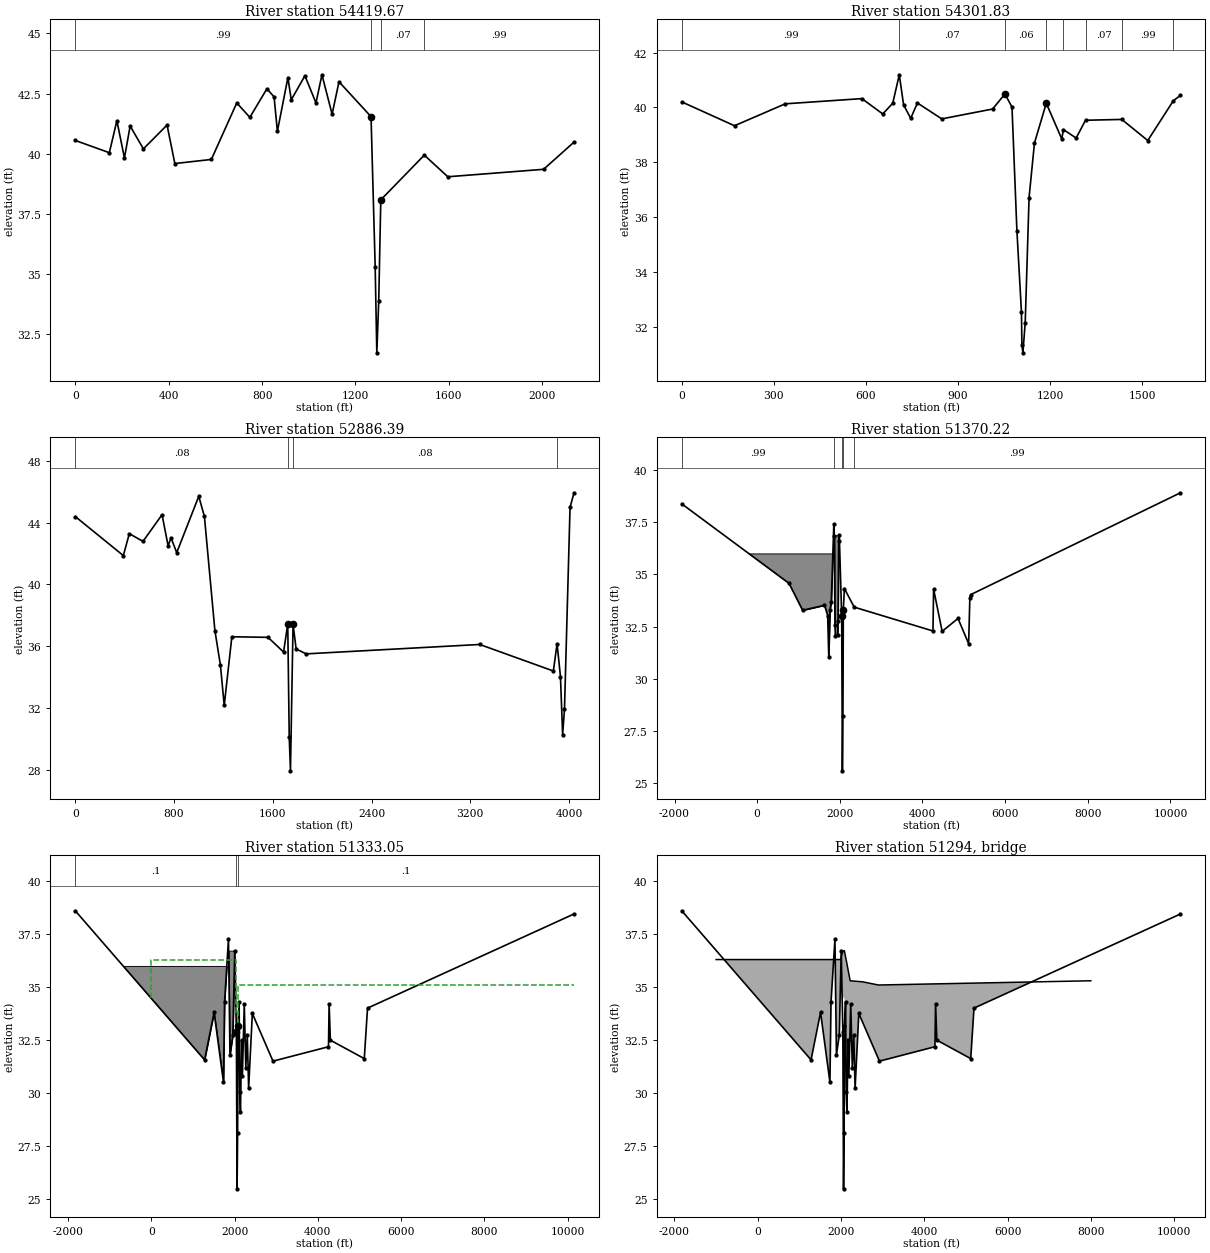
Type RM Length L Ch R = 1 ,54419.67,111.15,117.84,121.9
BEGIN DESCRIPTION:
451v44
Bank Station offset =      3709
END DESCRIPTION:
XS GIS Cut Line= 5
     3234567.258    13870035.036     3233341.744     13870292.43
     3233322.617    13870318.866     3233302.579    13870346.562
     3232571.788    13870711.914
#Sta/Elev= 30
       0   40.55  145.78   40.04  178.16   41.37  210.54   39.82  234.92   41.15
  291.71    40.2  393.04   41.19  426.41   39.59  582.82   39.76  691.63   42.11
  747.71   41.51   820.8    42.7  851.45   42.36  865.62   40.93  910.56   43.16
  925.05   42.24  983.54   43.24 1030.84   42.11 1056.52   43.28 1099.97   41.64
  1129.5   42.99 1266.71   41.54 1284.48   35.29 1291.46   31.72 1299.72   33.89
 1308.52   38.08 1494.91   39.94 1595.59   39.04 2005.72   39.35  2136.1   40.48
#Mann= 4 ,-1 , 0
       0     .99       0 1266.71     .06       0 1308.52     .07       0
 1494.91     .99       0
Bank Sta=1266.71,1308.52
XS Rating Curve= 0
Exp/Cntr=.3,.1

Type RM Length L Ch R = 1 ,54301.83,1394.35,1415.44,1440.24
BEGIN DESCRIPTION:
451v43
Bank Station offset =      3717
END DESCRIPTION:
XS GIS Cut Line= 4
     3234530.869    13869930.857 3233307.388683713870206.0749125
  3233260.08459613870230.2096511      3232708.46    13870309.531
#Sta/Elev= 30
       0    40.2 171.785   39.33 337.005   40.13 586.637   40.32 654.507   39.76
 687.018   40.15 708.365   41.19 722.447   40.09 745.587    39.6 767.489   40.16
 846.791   39.581012.254   39.941052.463   40.49 1075.43   40.01  1091.4    35.5
 1106.27   32.521107.638   31.341110.903   31.041118.472   32.141131.038   36.71
1148.618    38.71187.061   40.151237.464   38.851242.946   39.191284.246   38.88
 1314.86   39.53 1432.96   39.561517.562   38.791600.692   40.241624.101   40.44
#Mann= 8 ,-1 , 0
       0     .99       0 708.365     .07       01052.463     .06       0
1187.061     .07       01242.946     .99       0 1314.86     .07       0
 1432.96     .99       01600.692     .07       0
Bank Sta=1052.463,1187.061
XS Rating Curve= 0
Skew Angle= 30
Exp/Cntr=.3,.1

Type RM Length L Ch R = 1 ,52886.39,1514.58,1516.18,1516.9
BEGIN DESCRIPTION:
451v42
Applied n = 0.99 due to ineffective area caused by expansion from u/s flow constriction in channel.
Bank Station offset =      3257
END DESCRIPTION:
XS GIS Cut Line= 6
     3235061.723     13869056.97     3234731.912    13869036.336
     3234359.817    13869019.423     3233467.792    13868815.292
     3233276.926    13868798.594     3231046.805     13868867.93
#Sta/Elev= 30
       0    44.4  389.18   41.87  437.76   43.29  548.61   42.79  702.93   44.52
  751.84   42.51   775.6   43.02  821.76   42.06 1000.39   45.71 1046.04   44.41
 1131.16   37.01 1175.68   34.78 1206.68   32.16 1268.55   36.61 1561.72   36.57
 1687.39   35.62 1721.39   37.42 1733.39   30.12 1743.39   27.92 1764.39   37.42
 1789.39   35.82 1870.05    35.5 3276.67   36.11 3873.55   34.39 3903.57   36.16
 3931.02   34.03 3948.59   30.26  3963.6   31.92 4008.62   44.99 4040.81   45.94
#Mann= 4 ,-1 , 0
       0     .08       0 1721.39     .04       0 1764.39     .08       0
 3903.57     .99       0
Bank Sta=1721.39,1764.39
XS Rating Curve= 0
Exp/Cntr=.3,.1

Type RM Length L Ch R = 1 ,51370.22,37.15,37.16,43.96
BEGIN DESCRIPTION:
451s24u - xs 4/4 E.Wallisville rd
Bank Station offset =      2938
Cross section extended on LOB and ROB to contain 500 yr profile.  Elevated canal blocked on LOB.  Manning's "n" set to 0.99 on ROB due to bridge constriction for all but 0.2 % chance flow.  Even 0.2% chance flow overtops bridge on ROB only slightly and not anticipated to be effective at Overbanks.
END DESCRIPTION:
XS GIS Cut Line= 6
 3237342.756254213867550.7147775     3235521.699    13867430.817
     3233488.198    13867296.932     3233420.967    13867288.865
     3230294.395    13867180.645 3225298.476711813867541.6444372
#Sta/Elev= 30
   -1825   38.37  769.38   34.57 1098.65   33.28 1628.97   33.52 1705.35   33.03
 1732.42   31.05 1760.93   33.28 1792.84   33.67 1854.97   37.41 1866.75   36.85
 1881.78   32.57 1892.15   32.06 1947.59   32.09 1956.94   32.78 1971.98    36.6
 1987.01   36.87 2045.02      33 2061.85    25.6 2075.26   28.22 2084.71    33.3
 2110.17   34.32 2347.74   33.43 4253.89   32.29 4268.89   34.29 4475.98   32.27
 4859.67   32.89  5116.9   31.68 5146.58   33.88 5169.01   34.03   10243    38.9
#Mann= 5 ,-1 , 0
   -1825     .99       0 1854.97      .1       0 2045.02    .045       0
 2084.71      .1       0 2347.74     .99       0
#Block Obstruct= 2 ,-1
   -1825 1866.75      36 1866.75 1987.01   36.87
Bank Sta=2045.02,2084.71
XS Rating Curve= 0
Exp/Cntr=.5,.3

Type RM Length L Ch R = 1 ,51333.05,78.58,78.69,106.01
BEGIN DESCRIPTION:
Copy of 451s24u - xs 3/4 E.Wallisville rd
Bank Station offset =      2939
Cross section extended on LOB and ROB to contain 500 yr profile  Elevated canal and low ground beyond blocked on LOB. Channel n lowered due to concreted embankments beneath bridge.
END DESCRIPTION:
XS GIS Cut Line= 6
 3237345.479254213867513.6907775     3235524.422    13867393.793
     3233490.921    13867259.908      3233423.69    13867251.841
     3230276.476    13867143.071 3225380.109305613866973.8490134
#Sta/Elev= 30
   -1825    38.6 1280.66   31.57  1508.7   33.81 1734.18   30.52  1760.2    34.3
 1854.44   37.26 1890.32    31.8 1959.14   32.74 2004.86   36.72 2044.08   32.89
 2060.91   25.49 2074.32   28.11 2083.77   33.19 2110.07   34.29 2125.33   30.06
 2141.96   29.09 2170.36   32.51  2188.6   30.82  2233.8   34.21 2270.96   31.21
 2305.44   32.76 2338.76   30.23  2427.5   33.76 2923.52   31.51 4256.61   32.19
 4271.62   34.22 4301.63    32.5 5116.27   31.63 5194.39   34.01   10154   38.45
#Mann= 3 , 0 , 0
   -1825      .1       0 2044.08    .045       0 2083.77      .1       0
#XS Ineff= 2 , 0
       0 2035.77    36.3  2085.6       0    35.1
Permanent Ineff=
       F       F
#Block Obstruct= 2 ,-1
   -1825 1854.44      36 1854.44 2004.86   36.72
Bank Sta=2044.08,2083.77
XS Rating Curve= 0
Exp/Cntr=.5,.3

Type RM Length L Ch R = 3 ,51294   ,,,
BEGIN DESCRIPTION:
451s24: East Wallisville Rd. "Conc. Bridge"
END DESCRIPTION:
Bridge Culvert--1,0,-1,-1, 0
Deck Dist Width WeirC Skew NumUp NumDn MinLoCord MaxHiCord MaxSubmerge Is_Ogee
18.5,42,2.6,0, 12, 11, , , .95, 0, 0,0,,
   -1000       0 1989.24 2040.77 2040.77  2080.6  2080.6 2123.87    2220    2520
    2900    8000
    36.3    36.3    36.3   36.68   36.68   36.72   36.72   36.29    35.3   35.25
    35.1    35.3
                                   34.48   34.52
                
       0 1986.24 2037.77 2037.77  2077.6  2077.6 2120.87    2220    2520    2900
 4660.23
    36.3    36.3   36.68   36.68   36.72   36.72   36.29    35.3   35.25    35.1
    35.3
                           34.48   34.52
        
BR Coef=-1 , 0 , 0 ,, 0 ,,,.8,0,,0,
WSPro=,,,, 1 ,,,, 0 ,,,, 0 ,,,,-1 ,-1 ,-1 , 0 , 0 , 0 , 0 , 0
BC Design=,, 0 ,, 0 ,,,,,,
BC HTab HWMax=38.6