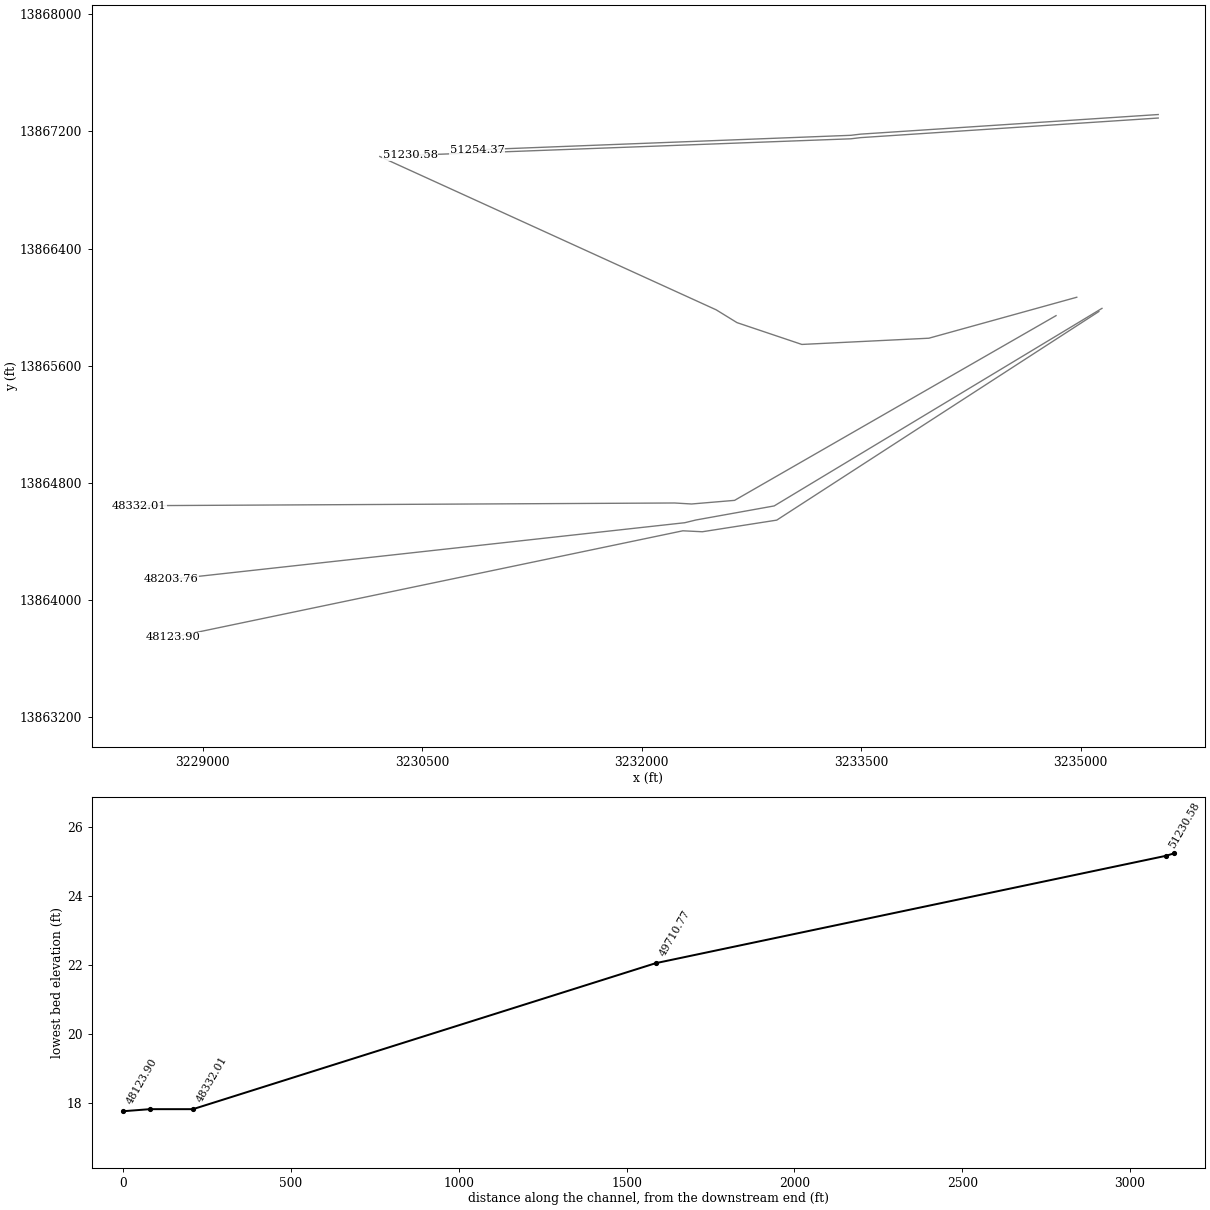
HEC-RAS study O100-00-00.prj: O100-00-00

--- O100-00-00.g01 (geometry) --- (continued)

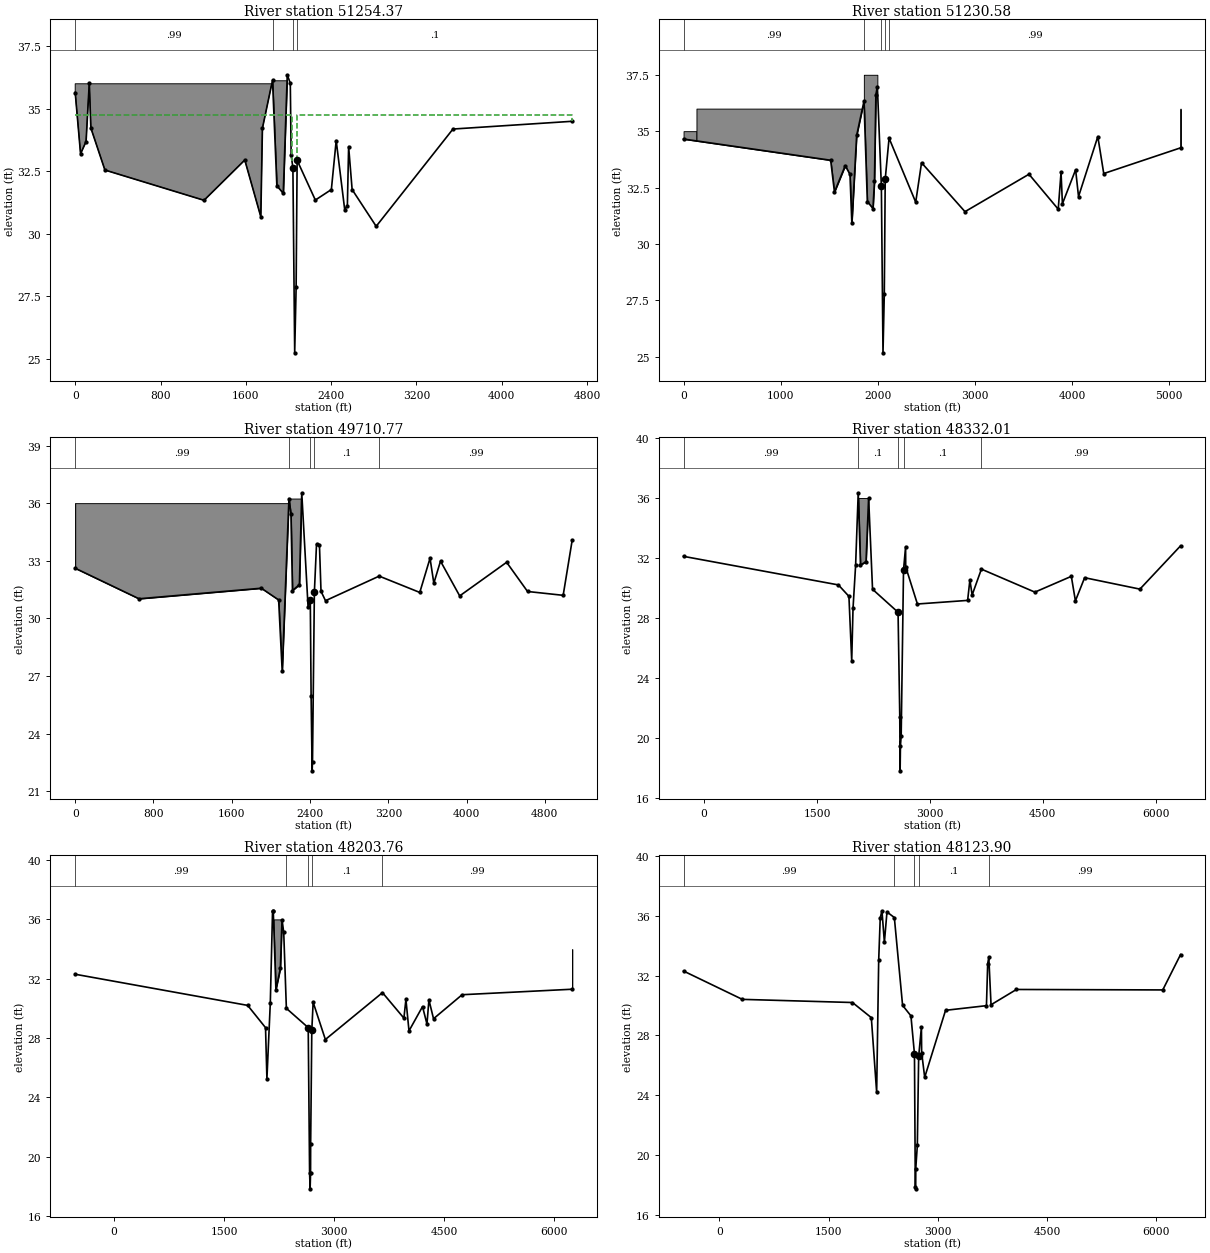
Type RM Length L Ch R = 1 ,51254.37,23.78,23.78,32
BEGIN DESCRIPTION:
Copy of 451s24u - xs 2/4 E.Wallisville rd
Bank Station offset =      2942
Elevated canal and low ground beyond blocked on LOB.  Reduced n of channel due to concreted embankments beneath bridge.
higher c/e coefficients used to avoid negative WSELs.
END DESCRIPTION:
XS GIS Cut Line= 4
     3235530.673    13867315.502     3233497.172    13867181.617
     3233429.941     13867173.55     3230877.253      13867074.4
#Sta/Elev= 30
       0   35.65   50.29    33.2  101.91   33.69  131.97   36.03  147.01   34.23
  278.61   32.55 1207.96   31.34 1590.12   32.95 1740.45   30.68 1755.48   34.22
  1850.1   36.14 1890.77   31.92  1950.9   31.62 1988.43   36.36 2016.85   36.02
 2024.84   33.15 2041.18   32.64 2058.01   25.24 2071.42   27.86 2080.87   32.94
 2251.68   31.35 2401.86   31.77 2447.15   33.73 2526.89   30.97 2551.91   31.12
 2563.71   33.49 2596.54   31.77 2822.11    30.3 3542.06   34.19 4660.23    34.5
#Mann= 4 ,-1 , 0
       0     .99       0  1850.1      .1       0 2041.18    .045       0
 2080.87      .1       0
#XS Ineff= 2 , 0
       0 2032.77   34.75  2082.6       0   34.75
Permanent Ineff=
       F       F
#Block Obstruct= 2 ,-1
       0  1850.1      36  1850.1 1988.43   36.14
Bank Sta=2041.18,2080.87
XS Rating Curve= 0
Exp/Cntr=.7,.5

Type RM Length L Ch R = 1 ,51230.58,1538.9,1519.82,1451.68
BEGIN DESCRIPTION:
Copy of 451s24u - xs 1/4 E.Wallisville rd
Bank Station offset =      2946
Elevated canal and low ground beyond blocked on LOB.   Manning's "n" set to 0.99 on ROB due to bridge constriction for all but 0.2 % chance flow.  Even 0.2% chance flow overtops bridge on ROB only slightly and thus is not anticipated to be effective on overbanks at approach sections.
END DESCRIPTION:
XS GIS Cut Line= 4
     3235530.811    13867291.629     3233497.311    13867157.744
     3233430.079    13867149.677     3230418.772    13867036.647
#Sta/Elev= 30
       0   34.65 1515.22   33.71 1554.29    32.3  1665.4   33.47 1714.16   33.08
 1733.35   30.91 1782.97   34.81  1858.4   36.33  1892.9   31.88 1951.04   31.57
 1966.16   32.77 1981.11   36.62 1996.14   36.98 2037.38   32.57 2054.21   25.17
 2067.62   27.79 2077.07   32.87 2116.72   34.69 2391.19   31.85  2451.2    33.6
 2898.63   31.43 3557.73   33.09 3859.04   31.54 3887.97   33.17 3902.16   31.78
 4038.07   33.29 4068.09    32.1 4266.82   34.76 4327.84   33.12 5119.04   34.26
#Mann= 5 ,-1 , 0
       0     .99       0  1858.4      .1       0 2037.38    .045       0
 2077.07      .1       0 2116.72     .99       0
#Block Obstruct= 4 ,-1
    1857 1996.14    37.5    5118 5119.04      36       0     133      35
     133    1857      36
Bank Sta=2037.38,2077.07
XS Rating Curve= 0
Exp/Cntr=.3,.1

Type RM Length L Ch R = 1 ,49710.77,1236.65,1378.76,1805.29
BEGIN DESCRIPTION:
451v41
Bank Station offset =      2579
Elevated canal  blocked on LOB.
Added ineffective (n=0.99) stations based on constriction
at Port Authority Canal Crossing just downstream (River Mile 47881.4)
END DESCRIPTION:
XS GIS Cut Line= 6
     3234974.051    13866066.908     3233963.125     13865786.89
     3233095.274    13865744.349     3232652.102    13865893.378
     3232510.042    13865980.745     3230210.749    13867028.755
#Sta/Elev= 30
       0   32.61   652.4   31.02 1902.38   31.57 2079.03   30.96 2115.56   27.25
 2184.51   36.24 2204.83   35.44 2220.43   31.45 2291.58   31.76 2315.29   36.54
 2379.85    30.6 2402.58   30.94 2410.89   25.98 2421.38   22.06 2425.16   22.52
 2444.32   31.36 2466.08   33.85 2496.18   33.82 2512.11   31.41 2558.01   30.92
 3106.75    32.2  3521.5   31.35  3626.3   33.13 3665.17   31.83 3733.38   32.98
 3929.36   31.17 4409.14   32.92 4622.85    31.4 4986.97    31.2 5079.45   34.08
#Mann= 5 ,-1 , 0
       0     .99       0 2184.51      .1       0 2402.58     .06       0
 2444.32      .1       0 3106.75     .99       0
#Block Obstruct= 3 ,-1
 2184.51 2315.29   36.24       0      .1      36      .1 2184.51      36
Bank Sta=2402.58,2444.32
XS Rating Curve= 0
Exp/Cntr=.3,.1

Type RM Length L Ch R = 1 ,48332.01,127.33,128.25,223.97
BEGIN DESCRIPTION:
451v40
Bank Station offset =      2395
LOB contains blocked elevated canal
extended LOB & ROB to enclose 500yr
Added ineffective (n=0.99) stations based on constriction
at Port Authority Canal Crossing just downstream (River Mile 47881.4) and on constriction to high lob points at RS 48123
END DESCRIPTION:
XS GIS Cut Line= 6
 3234832.241608413865941.1104902     3234594.671    13865804.596
     3232635.461    13864678.781     3232341.484    13864654.014
     3232225.611    13864660.817 3228563.384281413864642.3629514
#Sta/Elev= 30
    -274    32.1  1784.4    30.2 1924.41   29.44 1961.47   25.15 1978.77   28.64
 2013.37   31.51 2047.97   36.33    2078   31.52 2151.77   31.75 2186.37   35.98
 2238.27   29.91 2577.52   28.38 2600.29   21.44 2604.97   17.83 2609.28   19.51
 2618.98   20.16 2650.09   31.19  2677.9   32.75 2679.14    31.4  2834.7   28.93
 3502.48   29.17 3532.37   30.53 3562.37   29.53 3685.36   31.25 4396.34   29.72
 4880.89   30.77 4935.18   29.14 5057.61   30.68 5792.58   29.92    6333    32.8
#Mann= 5 ,-1 , 0
    -274     .99       0 2047.97      .1       0 2577.52     .06       0
 2650.09      .1       0 3685.36     .99       0
#Block Obstruct= 1 ,-1
 2047.97 2186.37   35.98
Bank Sta=2577.52,2650.09
XS Rating Curve= 0
Exp/Cntr=.3,.1

Type RM Length L Ch R = 1 ,48203.76,145.68,79.86,115.4
BEGIN DESCRIPTION:
451v39
Bank Station offset =      2326
LOB and ROB reach lengths > channel reach length - Due to alignment of cross section cut line
Added ineffective (n=0.99) stations based on constriction
at Port Authority Canal Crossing just downstream (River Mile 47881.4)  and on constriction to high lob points at RS 48123
elevated canal blocked in LOB
extended LOB to enclose 500yr
END DESCRIPTION:
XS GIS Cut Line= 6
 3235146.210263713865990.8471484     3232906.021    13864640.764
     3232371.151    13864544.574     3232350.527    13864539.532
     3232295.345    13864526.043     3228781.783    13864138.529
#Sta/Elev= 30
    -527    32.3 1822.91    30.2 2066.17    28.7  2085.1   25.25 2131.28   30.37
 2161.76   36.55 2171.54   36.58 2207.48   31.26 2268.44   32.69 2291.08   35.98
 2314.16   35.12 2350.23      30 2647.85    28.7 2666.58    18.9 2673.78   17.83
 2679.69   18.88 2681.08   20.88 2696.64   28.51 2714.98   30.41 2881.55    27.9
 3659.77   31.06 3951.63   29.34 3979.06    30.6 4020.94   28.48 4205.43   30.12
 4265.79   28.94 4292.49   30.57 4355.22    29.3 4744.86   30.92 6244.92   31.29
#Mann= 5 ,-1 , 0
    -527     .99       0 2350.23      .1       0 2647.85     .06       0
 2696.64      .1       0 3659.77     .99       0
#Block Obstruct= 2 ,-1
    2177 2291.08      36  6244.5 6244.92      34
Bank Sta=2647.85,2696.64
XS Rating Curve= 0
Exp/Cntr=.3,.1

Type RM Length L Ch R = 1 ,48123.90,58.68,32.78,120.3
BEGIN DESCRIPTION:
451v38
Bank Station offset =      2306
LOB and ROB reach lengths > channel reach length - Due to shape of cross section cut line
extended LOB & ROB to enclose 500yr
Added ineffective (n=0.99) stations based on constriction
at Port Authority Canal Crossing just downstream (River Mile 47881.4)
END DESCRIPTION:
XS GIS Cut Line= 6
  3235124.82609313865969.2448545      3234711.86    13865701.807
     3232923.658    13864543.763     3232414.899    13864464.275
     3232281.985    13864470.763 3228800.503267213863743.8226842
#Sta/Elev= 30
    -492    32.3  315.24   30.41 1828.31    30.2 2087.32   29.19 2160.46   24.21
 2188.41   33.01 2209.71   35.85 2233.24   36.32 2266.74   34.22  2302.1   36.24
 2403.38   35.87 2516.68   30.01  2631.3   29.31 2679.82   26.77 2691.49   17.89
 2694.48   17.77 2697.36   19.11  2719.2   20.67 2737.61   26.61 2775.49   28.57
 2778.43   26.86 2820.34   25.21 3106.94   29.68 3668.55   29.99 3685.58   32.78
 3700.91   33.23 3731.56   30.05 4080.41   31.07 6090.51   31.04    6335    33.4
#Mann= 5 ,-1 , 0
    -492     .99       0 2403.38      .1       0 2679.82     .06       0
 2737.61      .1       0 3700.91     .99       0
Bank Sta=2679.82,2737.61
XS Rating Curve= 0
Exp/Cntr=.3,.1