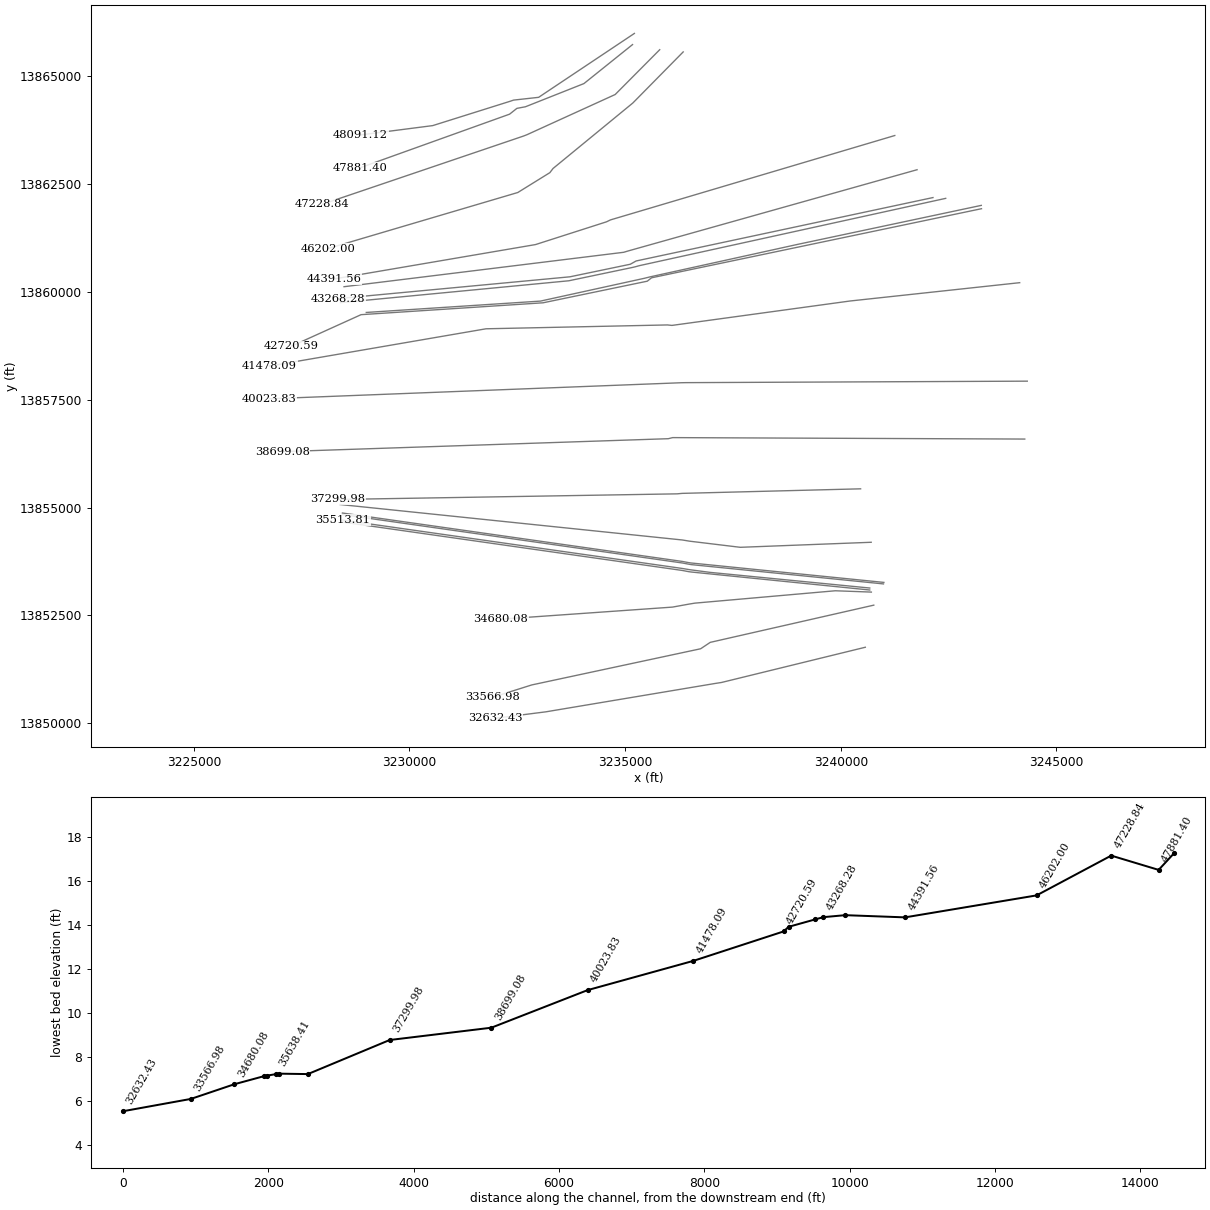
HEC-RAS study O100-00-00.prj: O100-00-00

--- O100-00-00.g01 (geometry) --- (continued)

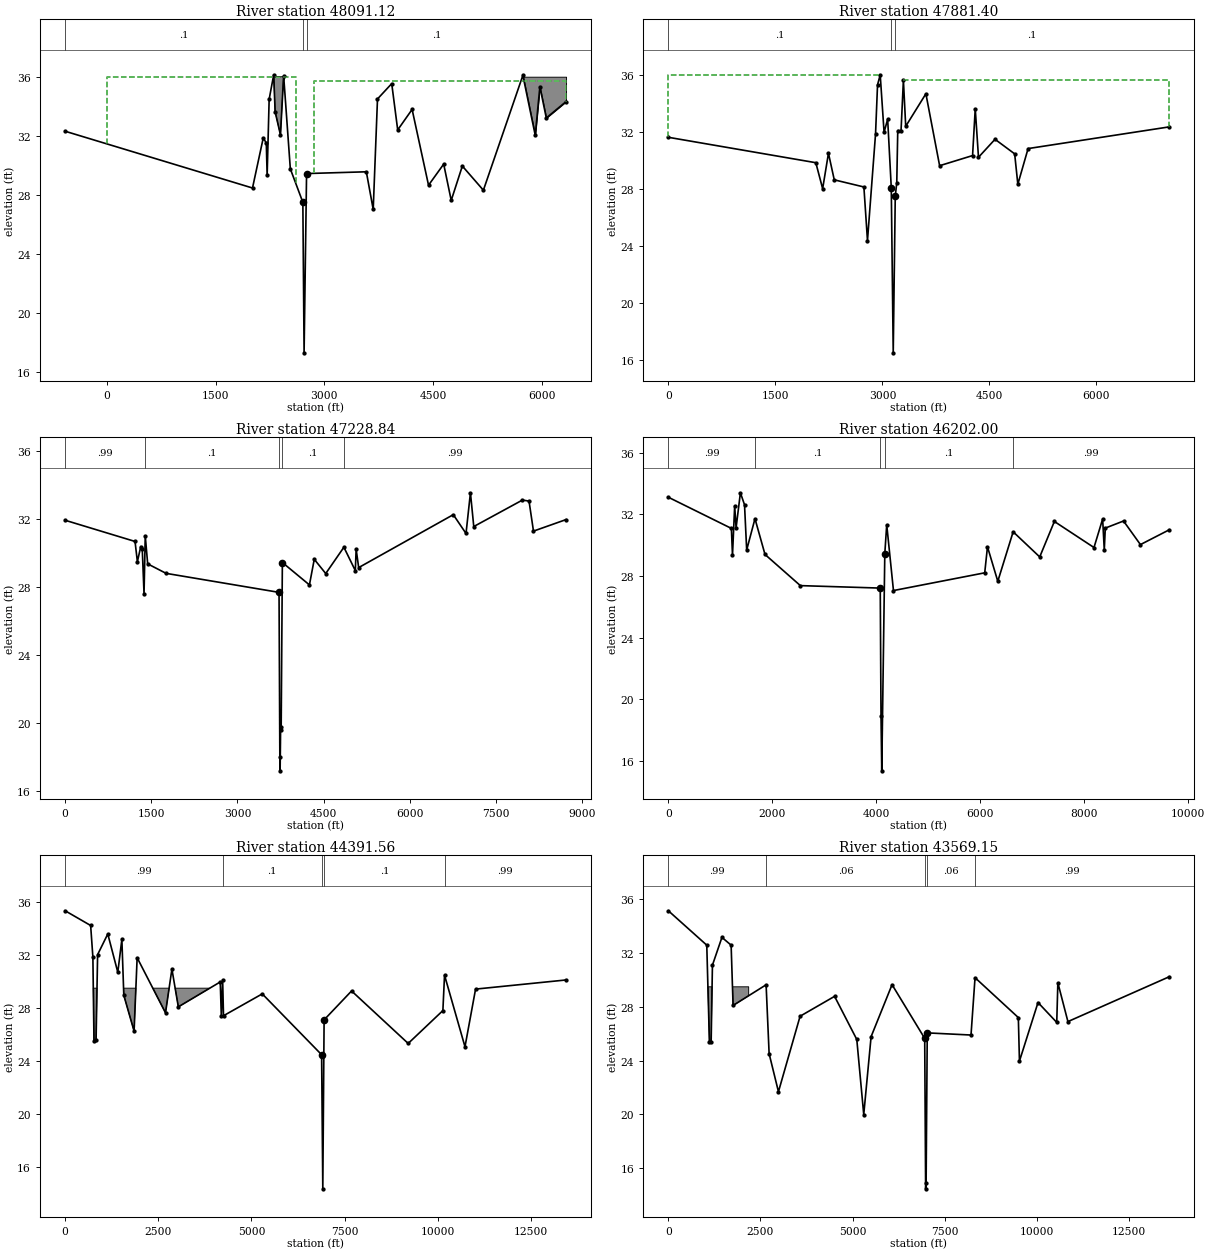
Type RM Length L Ch R = 1 ,48091.12,136.19,209.71,302.15
BEGIN DESCRIPTION:
451v37
Bank Station offset =      2279
LOB contains blocked elevated canal
extended LOB to enclose 500yr
Added normal ineffective stations due to constriction
at Port Authority Canal Crossing structure just downstream (River Mile 47881.4).  This is similar to a bridge section 3/4.
END DESCRIPTION:
XS GIS Cut Line= 6
 3235213.9904651 13865994.364113     3232994.204    13864512.899
     3232411.741    13864448.321     3232344.301    13864424.893
     3230538.497    13863857.178     3228865.953    13863641.307
#Sta/Elev= 30
    -573    32.3 2009.88   28.45 2158.13   31.85 2200.02    31.5 2211.67   29.31
  2239.4   34.47 2302.22   36.13 2321.52   33.63 2395.46   32.05 2439.12   36.07
 2531.32   29.75 2703.99   27.48 2721.04   17.27 2755.23   29.43 3579.06   29.55
 3673.95      27 3733.01   34.49 3929.17   35.53 4011.56   32.39  4210.2   33.78
  4436.6   28.64  4645.6   30.07 4749.48   27.61 4902.73   29.94 5192.81    28.3
 5737.25   36.09 5907.74   32.03 5971.68   35.32 6060.24    33.2 6332.53   34.31
#Mann= 3 ,-1 , 0
    -573      .1       0 2703.99     .06       0 2755.23      .1       0
#XS Ineff= 2 , 0
       0    2603   35.98    2855       0    35.7
Permanent Ineff=
       F       F
#Block Obstruct= 2 ,-1
 2302.22 2443.27      36 5737.25 6332.53      36
Bank Sta=2703.99,2755.23
XS Rating Curve= 0
Exp/Cntr=.3,.1

Type RM Length L Ch R = 1 ,47881.40,703.6,652.56,578.41
BEGIN DESCRIPTION:
451v36
Bank Station offset =      1848
Added ineffective settings based on constriction
at Port Authority Canal Crossing at this location.
END DESCRIPTION:
XS GIS Cut Line= 6
     3235171.311     13865735.84     3234044.396    13864831.677
     3232688.096    13864293.967     3232490.005    13864256.948
     3232320.975    13864122.644     3228843.999    13862875.719
#Sta/Elev= 30
       0   31.62 2066.67   29.84 2162.43   28.02 2243.83    30.5 2325.23   28.64
 2740.42   28.14 2790.73   24.39  2903.8   31.86 2931.75    35.3 2969.14      36
 3023.34   31.97 3073.59   32.89 3124.12    28.1 3151.67   16.52 3180.19    27.5
 3201.21   28.44 3215.07   32.09 3261.04   32.08 3294.21   35.62 3326.69   32.39
 3609.43   34.67 3801.84   29.63 4263.68   30.34 4301.09   33.62 4346.57   30.22
 4578.28   31.48 4853.61   30.46 4898.04   28.33 5041.83   30.83 7020.49   32.35
#Mann= 3 ,-1 , 0
       0      .1       0 3124.12     .06       0 3180.19      .1       0
#XS Ineff= 2 , 0
       0 2967.87   35.98 3294.21       0   35.62
Permanent Ineff=
       F       F
Bank Sta=3124.12,3180.19
XS Rating Curve= 0
Exp/Cntr=.3,.1

Type RM Length L Ch R = 1 ,47228.84,769.85,1026.84,1176.92
BEGIN DESCRIPTION:
451v35
Bank Station offset =      1256
Added ineffective (n=0.99) stations based on expansion
from Port Authority Canal Crossing just uptream (River Mile 47881.4)
END DESCRIPTION:
XS GIS Cut Line= 5
     3235800.929    13865616.723      3234768.95    13864578.179
     3232722.255    13863645.585     3232640.721    13863614.139
     3227978.437    13862032.934
#Sta/Elev= 30
       0   31.94 1217.08   30.69 1257.98    29.5 1317.18   30.39 1343.33   30.22
 1373.84    27.6 1394.98   31.03 1437.28   29.37 1758.15   28.81 3725.04   27.69
 3739.06      18 3743.91   17.17    3752   19.55  3762.4   19.74 3783.07   29.45
 4254.24   28.13 4338.61   29.64 4538.26    28.8 4854.55   30.35 5053.76   28.97
  5067.8   30.24 5111.94   29.15 6759.88   32.27 6981.51   31.16 7058.39   33.56
 7116.56   31.57 7963.62   33.13 8079.04   33.07 8156.33    31.3 8723.75   31.98
#Mann= 5 ,-1 , 0
       0     .99       0 1394.98      .1       0 3725.04     .06       0
 3783.07      .1       0 4854.55     .99       0
Bank Sta=3725.04,3783.07
XS Rating Curve= 0
Exp/Cntr=.3,.1

Type RM Length L Ch R = 1 ,46202.00,2440.12,1810.44,1310.04
BEGIN DESCRIPTION:
451v34
Bank Station offset =       895
Added ineffective (n=0.99) stations based on expansion
from Port Authority Canal Crossing just uptream (River Mile 47881.4)
END DESCRIPTION:
XS GIS Cut Line= 6
     3236345.463    13865565.673     3235178.287    13864381.586
     3233327.735    13862862.927     3233254.587    13862766.793
      3232511.25     13862306.27     3228115.104    13861007.926
#Sta/Elev= 30
       0    33.1 1212.45   31.08 1233.51   29.33 1275.64   32.54 1302.84   31.12
 1385.93   33.39  1465.2   32.61 1506.55   29.68 1666.17   31.71 1859.22   29.39
 2539.16   27.37 4075.88   27.21 4090.77   18.89    4105   15.36 4163.63   29.45
 4200.47   31.32 4330.04   27.05 6085.67    28.2 6138.56   29.89 6337.16   27.65
 6632.41   30.86 7143.58   29.23 7425.37   31.53 8187.47   29.84 8354.13   31.69
 8385.49   29.68 8404.98    31.1 8755.76   31.56 9080.95   30.03 9635.65   30.99
#Mann= 5 ,-1 , 0
       0     .99       0 1666.17      .1       0 4075.88     .06       0
 4163.63      .1       0 6632.41     .99       0
Bank Sta=4075.88,4163.63
XS Rating Curve= 0
Exp/Cntr=.3,.1

Type RM Length L Ch R = 1 ,44391.56,1000.24,822.4,497.26
BEGIN DESCRIPTION:
451v33
Bank Station offset =     -1915
Block added in LOB since water cannot get into this area.
END DESCRIPTION:
XS GIS Cut Line= 5
     3241250.955    13863627.377     3234659.799    13861671.193
     3234567.845    13861626.758     3232921.253    13861099.038
     3228251.772     13860301.81
#Sta/Elev= 30
       0   35.34  684.38   34.23  744.41   31.84  773.95   25.52  829.79   25.56
  871.16   32.03 1144.26   33.59 1413.08    30.7 1522.24   33.18 1574.45   28.96
 1850.31   26.26 1932.06    31.8 2693.53   27.64  2865.4   30.94 3037.51   28.09
 4162.49   29.97 4191.73   27.38 4226.66   30.13 4250.04   27.42 5290.19   29.07
 6883.12   24.48 6915.03   14.36 6950.03   27.11 7687.24   29.29 9206.61   25.33
10137.87   27.8110181.97   30.4810731.05   25.0811015.06   29.4313443.59   30.12
#Mann= 5 ,-1 , 0
       0     .99       0 4226.66      .1       0 6883.12     .06       0
 6950.03      .1       010181.97     .99       0
#Block Obstruct= 2 , 0
       0    4120    29.5               0
Bank Sta=6883.12,6950.03
XS Rating Curve= 0
Exp/Cntr=.3,.1

Type RM Length L Ch R = 1 ,43569.15,449.54,300.87,429
BEGIN DESCRIPTION:
451v32
Bank Station offset =     -1984
LOB and ROB reach lengths > channel reach length
due to alignment of cross section cut line. Downstream cross section bent u/s on ROB to catch high points, thereby reducing the ROB reach length.
Cross section trimmed on ROB to contain 500yr WSEL
Block added in LOB since water cannot get into this area.
END DESCRIPTION:
XS GIS Cut Line= 4
     3241767.327    13862834.376     3235067.323    13860950.576
     3234965.882    13860920.273 3228482.1838117 13860122.360338
#Sta/Elev= 30
       0   35.16 1042.83    32.6 1114.96   25.36 1161.71   25.42 1196.34   31.11
 1454.35   33.18 1703.78    32.6 1756.99   28.11 2653.57   29.65 2735.45   24.52
 2988.56   21.69 3576.07   27.31  4512.2   28.79 5115.38   25.58    5304   19.99
 5503.91   25.79 6072.56   29.66 6958.97   25.66 6984.11   14.46 6997.13   14.91
 7028.22   26.07 8216.18   25.91 8325.41   30.18 9500.79   27.21 9531.02   23.97
10034.99   28.33 10543.6   26.8510573.83    29.810846.77   26.9113598.27   30.25
#Mann= 5 ,-1 , 0
       0     .99       0 2653.57     .06       0 6958.97    .045       0
 7028.22     .06       0 8325.41     .99       0
#Block Obstruct= 2 , 0
       0    2180    29.5               0
Bank Sta=6958.97,7028.22
XS Rating Curve= 0
Exp/Cntr=.3,.1

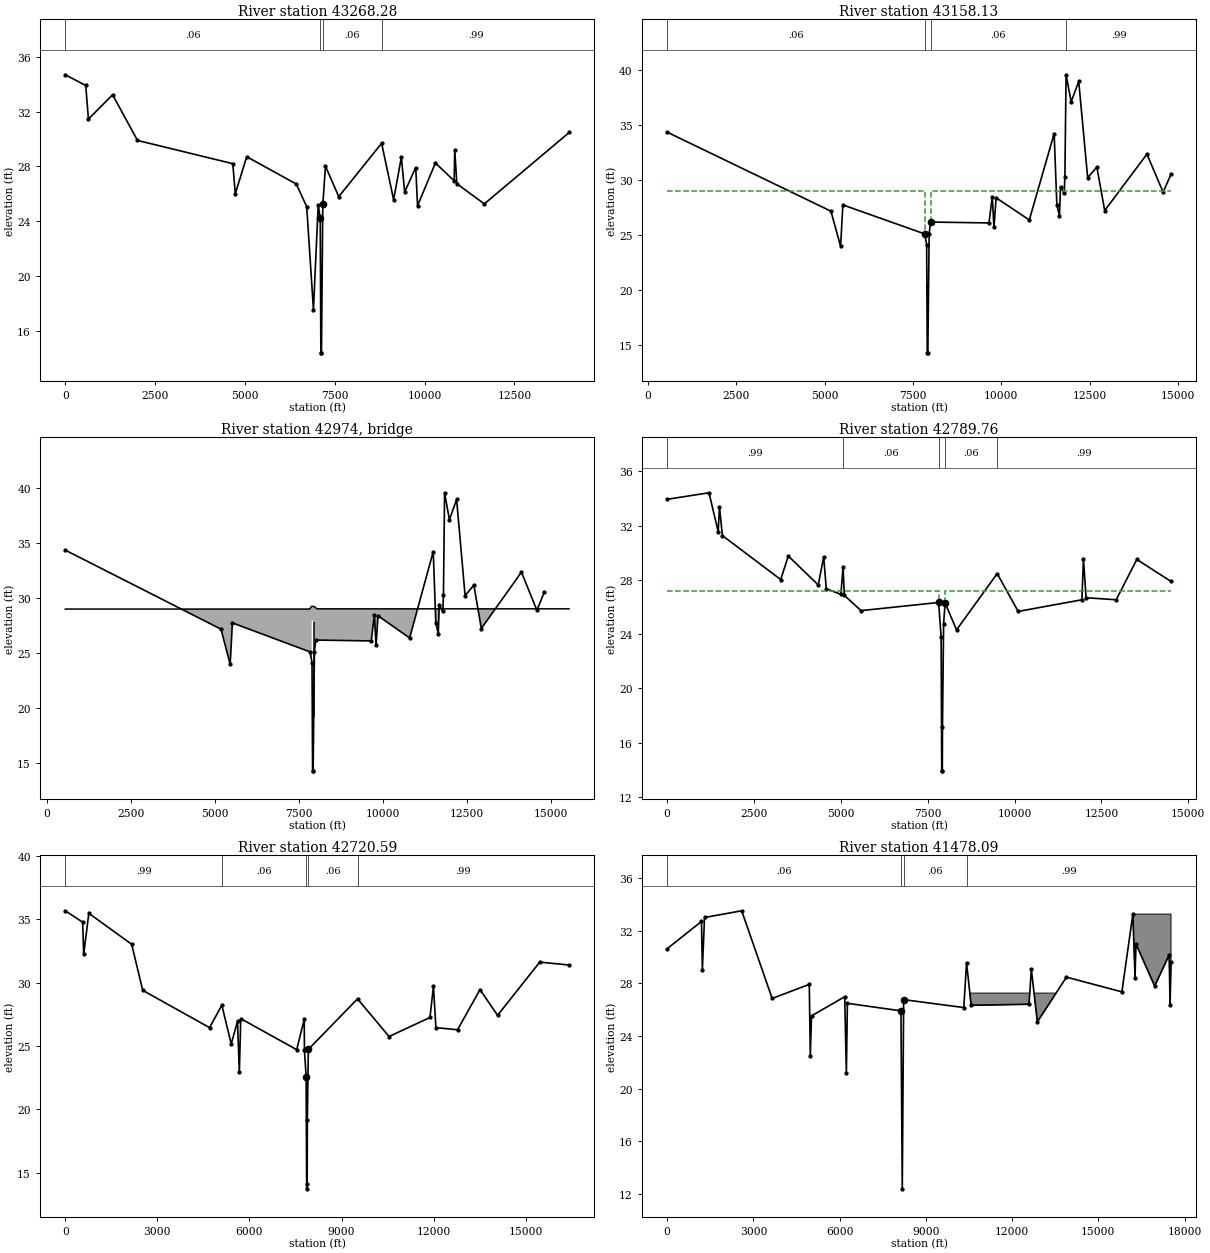
Type RM Length L Ch R = 1 ,43268.28,126.64,110.15,95.24
BEGIN DESCRIPTION:
451s23u - xs 4/4 at I-10
Bank Station offset =     -2112
END DESCRIPTION:
XS GIS Cut Line= 5
     3242136.165    13862188.911     3235254.902    13860719.135
      3235118.67     13860643.12     3233719.579    13860351.859
     3228342.884    13859846.251
#Sta/Elev= 30
       0    34.7  568.74   33.92  643.79   31.46 1316.26   33.24 2008.95    29.9
 4661.52    28.2 4730.81      26 5048.23   28.71 6429.66   26.71  6717.9   25.06
  6905.6   17.53 7038.74   25.19 7095.12    24.2    7112   14.37 7128.76   14.39
 7166.36   25.22 7240.65   28.02 7609.89   25.79 8802.96   29.69 9137.27   25.56
 9352.01   28.67 9444.47   26.13 9752.13   27.92 9802.76   25.1310300.17   28.25
10821.83   26.9510837.62   29.2110897.16   26.7311662.04   25.2614021.98   30.48
#Mann= 4 ,-1 , 0
       0     .06       0 7095.12    .045       0 7166.36     .06       0
 8802.96     .99       0
Bank Sta=7095.12,7166.36
XS Rating Curve= 0
Exp/Cntr=.5,.3

Type RM Length L Ch R = 1 ,43158.13,351.69,368.38,340.77
BEGIN DESCRIPTION:
Copy of 451s23u - xs 3/4 at I-10
Bank Station offset =     -2362
Block added in ROB since water cannot get into the area beyond the high points.
END DESCRIPTION:
XS GIS Cut Line= 6
     3242431.235    13862170.469     3235326.688    13860609.818
     3235243.934    13860586.648     3235173.674    13860569.847
      3233693.26    13860259.742     3228400.342    13859751.944
#Sta/Elev= 30
     543   34.35 5178.19   27.16 5452.12   23.96 5516.47   27.73 7831.49   25.09
 7887.87    24.1 7904.75   14.27 7921.51   14.29 7959.11   25.12 7998.33   26.17
  9652.2   26.09 9745.16   28.47 9793.34    25.7 9853.61   28.3810793.61   26.36
11496.79   34.22 11573.7   27.71 11646.8   26.7511676.94   29.3611782.42   28.78
11800.79   30.3111834.38   39.5711978.32   37.1212192.72   38.9612445.43   30.21
12705.39   31.1712927.66   27.2214122.99   32.3514582.18   28.8814804.88   30.53
#Mann= 4 ,-1 , 0
     543     .06       0 7831.49    .045       0 7998.33     .06       0
11834.38     .99       0
#XS Ineff= 2 , 0
       0 7831.49   28.99 7998.33       0   28.99
Permanent Ineff=
       F       F
#Block Obstruct= 2 , 0
     543                12129.01     543   39.55
Bank Sta=7831.49,7998.33
XS Rating Curve= 0
Exp/Cntr=.5,.3

Type RM Length L Ch R = 3 ,42974   ,,,
BEGIN DESCRIPTION:
451s20-451s23 I-10
combined structure includes adjacent service roads -- the roadway points are based on So Service Rd on d/s side and No Service Rd on u/s side.  The I-10 bridges are elevated greater than 30' and will not be overtopped.
END DESCRIPTION:
Bridge Culvert--1,0,-1,-1, 0
Deck Dist Width WeirC Skew NumUp NumDn MinLoCord MaxHiCord MaxSubmerge Is_Ogee
27.5,313,2.6,0, 6, 6, , , .95, 0, 0,0,,
     543 7814.46 7877.45 7953.75 8034.26   15543
   28.99   28.99   29.24   29.22   29.01   29.01
                   27.94   27.92
       0 7813.83 7876.48 7952.89 8026.74   15000
   29.23   29.23   29.18    29.2   28.94   28.94
                   27.88    27.9
Pier Skew, UpSta & Num, DnSta & Num=  ,7912.63, 4 ,7912.63, 4 , 3 , 3 , 0 ,,
    1.35    1.35     2.4     2.4
      13    25.5    25.5    27.9
    1.35    1.35     2.4     2.4
      13    25.5    25.5    27.9
Pier Skew, UpSta & Num, DnSta & Num=  ,7938.33, 4 ,7938.33, 4 , 3 , 3 , 0 ,,
    1.35    1.35     2.4     2.4
      13    25.5    25.5    27.9
    1.35    1.35     2.4     2.4
      13    25.5    25.5    27.9
BR Coef=-1 , 0 , 0 ,, 0 ,,,.8,0,,0,
WSPro=,,,, 1 ,,,, 0 ,,,, 0 ,,,,-1 ,-1 ,-1 , 0 , 0 , 0 , 0 , 0
BC Design=,, 0 ,, 0 ,,,,,,
BC HTab HWMax=39.57

Type RM Length L Ch R = 1 ,42789.76,47.88,69.17,59.36
BEGIN DESCRIPTION:
Copy of 451s23u - xs 2/4 at I-10
Bank Station offset =     -2904
Block added in ROB since water cannot get into this area.
higher c/e coefficients used to avoid negative WSELs.
END DESCRIPTION:
XS GIS Cut Line= 6
     3243256.375    13862007.714     3238998.773    13861103.623
     3235567.095    13860347.903     3235442.186    13860316.676
     3233036.218    13859788.803 3228998.133272813859525.4494818
#Sta/Elev= 30
       0   33.93 1204.07   34.41 1469.61   31.55 1505.43   33.38 1589.37   31.26
 3268.48   28.02 3487.59   29.75 4350.41   27.62 4505.91    29.7 4580.13   27.34
 5001.46   26.93 5063.47   28.94 5101.24   26.85 5581.07   25.73  7815.1   26.33
 7887.22   23.76  7904.1   13.93 7920.86   13.95 7926.04   17.19 7958.46   24.78
 8001.66   26.29 8331.22   24.31 9500.81   28.46 10104.6   25.6711938.82   26.53
11983.87   29.53 12060.5   26.6812926.83   26.5313519.57    29.514505.06   27.88
#Mann= 5 ,-1 , 0
       0     .99       0 5063.47     .06       0  7815.1    .045       0
 8001.66     .06       0 9500.81     .99       0
#XS Ineff= 2 , 0
       0  7815.1    27.2 8001.66       0    27.2
Permanent Ineff=
       F       F
#Block Obstruct= 2 , 0
       0                    9425       0    28.5
Bank Sta=7815.1,8001.66
XS Rating Curve= 0
Exp/Cntr=.7,.5

Type RM Length L Ch R = 1 ,42720.59,1442.3,1242.5,707.16
BEGIN DESCRIPTION:
Copy of 451s23u - xs 1/4 at I-10
Bank Station offset =     -2864
Block added in ROB since water cannot get into this area.
END DESCRIPTION:
XS GIS Cut Line= 6
     3243261.119    13861930.724     3235611.779    13860328.977
     3235512.798    13860250.241     3233096.777    13859749.259
     3228877.122    13859474.064      3227256.53    13858740.211
#Sta/Elev= 30
       0   35.66  565.34   34.76  599.49   32.23  766.47   35.46  2161.7   33.02
 2523.53   29.38 4700.86   26.44 5100.48   28.21 5406.16   25.16 5611.06   26.93
 5670.94    22.9 5716.95   27.15 7539.88    24.7 7785.43    27.1 7790.85   24.69
 7847.23   22.58 7864.11   13.72 7880.87   14.08 7886.05   19.15 7918.47   24.72
 9521.31   28.7110548.27   25.7411881.81   27.2411995.05    29.712075.71   26.44
12779.99   26.27 13511.8   29.44 14084.4   27.4115458.12   31.61 16416.8   31.38
#Mann= 5 ,-1 , 0
       0     .99       0 5100.48     .06       0 7847.23    .045       0
 7918.47     .06       0 9521.31     .99       0
#Block Obstruct= 2 , 0
       0                    9375       0    27.5
Bank Sta=7847.23,7918.47
XS Rating Curve= 0
Exp/Cntr=.3,.1

Type RM Length L Ch R = 1 ,41478.09,1855.67,1454.26,1407.59
BEGIN DESCRIPTION:
451v31
Bank Station offset =     -3179
Block added in ROB since water cannot get into this area.
END DESCRIPTION:
XS GIS Cut Line= 6
      3244146.33     13860215.63      3240218.21    13859791.467
     3236083.994    13859225.025     3235980.541    13859236.008
      3231775.07    13859146.745     3226755.661    13858282.735
#Sta/Elev= 30
       0   30.62 1194.25   32.69 1224.42   28.99 1299.28   32.99 2592.01    33.5
  3652.9   26.84 4943.46   27.91 4979.52    22.5 5021.23   25.52 6176.13   26.97
 6233.66   21.19 6269.81   26.47 8132.75    25.9 8178.65   12.38 8227.09   26.75
10318.55   26.1510414.88   29.5510574.38   26.32 12587.4    26.412668.73   29.05
12877.71   25.0613889.46   28.4615818.29   27.3416199.91   33.2516276.02   28.43
16306.46   30.99 16959.3   27.7817463.22   30.1517493.66   26.3517527.47    29.6
#Mann= 4 ,-1 , 0
       0     .06       0 8132.75    .045       0 8227.09     .06       0
10414.88     .99       0
#Block Obstruct= 2 ,-1
 16199.917527.47   33.25   10380 16199.9   27.25
Bank Sta=8132.75,8227.09
XS Rating Curve= 0
Exp/Cntr=.3,.1

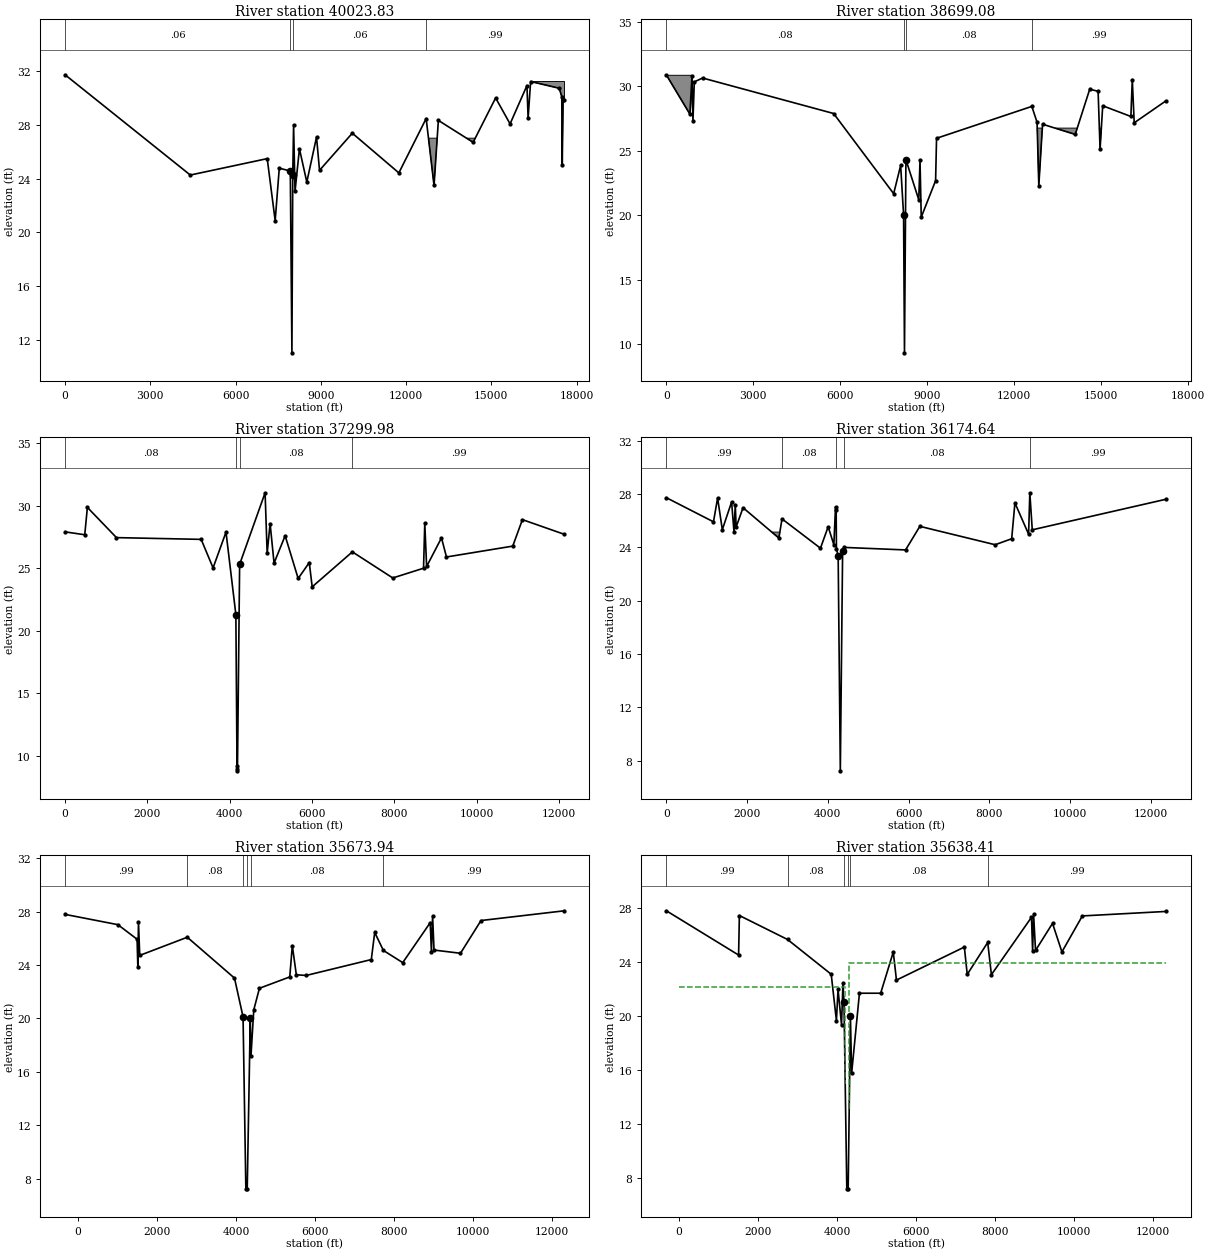
Type RM Length L Ch R = 1 ,40023.83,1973.95,1324.75,1292.15
BEGIN DESCRIPTION:
451v30
Bank Station offset =     -2983
Block added in ROB since water cannot get into this area.
END DESCRIPTION:
XS GIS Cut Line= 4
     3244322.745     13857932.56     3236408.488    13857898.172
     3236300.905    13857896.093     3226755.661    13857524.023
#Sta/Elev= 30
       0   31.71 4406.85   24.26 7114.18   25.48 7393.83   20.87 7538.16   24.77
 7926.07   24.56 7983.04   11.05 8012.81   24.28 8041.98   27.99 8092.27   23.04
  8247.8   26.21 8507.04   23.74 8849.48   27.08 8954.56   24.6110108.85   27.37
11746.69   24.4212707.41   28.4612984.49   23.4913136.96   28.3214360.29   26.69
15152.41   29.9915660.45   28.0616254.52   30.9116295.14   28.4916384.23   31.21
17389.38   30.7117481.04   30.0817496.05      2517526.07   29.8317574.43   29.86
#Mann= 4 ,-1 , 0
       0     .06       0 7926.07    .045       0 8012.81     .06       0
12707.41     .99       0
#Block Obstruct= 2 ,-1
 16384.217574.43   31.21   12800 16384.2      27
Bank Sta=7926.07,8012.81
XS Rating Curve= 0
Exp/Cntr=.3,.1

Type RM Length L Ch R = 1 ,38699.08,1378.72,1399.09,1263.83
BEGIN DESCRIPTION:
451v29
Bank Station offset =     -3213
Block added in ROB since water cannot get into this area.
END DESCRIPTION:
XS GIS Cut Line= 4
     3244264.382    13856590.225     3236100.689    13856623.834
     3236000.205    13856598.686     3227047.473    13856298.413
#Sta/Elev= 30
       0   30.86   810.4   27.83  885.41   30.81  916.77   27.31  963.74   30.33
 1248.94   30.63 5769.37   27.88 7840.16   21.67 8080.84   23.86 8181.93   20.03
 8213.07    9.34 8262.91    24.3 8705.41    21.2 8748.84   24.26    8791   19.85
 9286.71   22.68 9319.16   25.9612606.02   28.4312786.12    27.212846.15   22.29
12976.09   27.0514102.74   26.2614602.14   29.7614891.92    29.6 14959.5   25.12
15050.43   28.4816022.44   27.6516070.78   30.5116137.09   27.1617225.12   28.85
#Mann= 4 ,-1 , 0
       0     .08       0 8181.93    .045       0 8262.91     .08       0
12606.02     .99       0
#Block Obstruct= 3 ,-1
       0   850.2   30.88   1680517225.12    27.8   12665   16805   26.75
Bank Sta=8181.93,8262.91
XS Rating Curve= 0
Exp/Cntr=.3,.1

Type RM Length L Ch R = 1 ,37299.98,1311.7,1125.34,871.4
BEGIN DESCRIPTION:
451v28
Bank Station offset =       818.
Block added in ROB since water cannot get into this area.
END DESCRIPTION:
XS GIS Cut Line= 4
     3240458.599    13855436.468     3236321.426    13855331.037
     3236204.748    13855320.096     3228331.446    13855189.527
#Sta/Elev= 30
       0   27.91   477.9   27.68  541.93   29.87 1248.26   27.45 3305.51   27.31
 3594.89   25.03 3909.11   27.89 4148.49   21.29 4176.17    9.18 4181.75    8.78
 4187.57    8.91 4239.92   25.31 4858.53   31.04 4908.63    26.2  4980.2   28.58
 5076.07   25.41 5345.58    27.6 5661.66   24.18  5931.7   25.45 6002.24   23.51
 6978.22   26.31 7959.57   24.22 8707.08      25 8737.08   28.61 8782.09   25.14
 9143.17   27.43 9264.08    25.910873.93   26.7711108.99   28.8912130.09   27.71
#Mann= 4 ,-1 , 0
       0     .08       0 4148.49    .045       0 4239.92     .08       0
 6978.22     .99       0
#Block Obstruct= 2 , 0
       0                    7160       0      26
Bank Sta=4148.49,4239.92
XS Rating Curve= 0
Exp/Cntr=.3,.1

Type RM Length L Ch R = 1 ,36174.64,485.03,400.7,483.46
BEGIN DESCRIPTION:
451v27
Bank Station offset =       691
LOB and ROB reach lengths > channel reach length - Flow lines drawn parallel to the existing FIRM making the overbank reach lengths greater
Block added in LOB since water cannot get into this area.
END DESCRIPTION:
XS GIS Cut Line= 5
     3240704.276    13854197.366     3237669.431    13854080.641
     3236495.582     13854222.54     3236324.635    13854250.586
     3228389.808    13855072.802
#Sta/Elev= 30
       0   27.73 1167.09   25.92 1269.02   27.71 1385.84   25.33 1615.62   27.41
 1676.53   25.12 1706.55   27.22 1728.32   25.53 1899.12   26.98 2786.68    24.7
 2864.42   26.14 3816.67   23.94 4007.84   25.55 4148.72    24.2 4189.97   27.03
 4205.98   26.78 4212.56    23.9 4255.29   23.36 4308.85    7.23 4365.82   23.74
 4403.42      24 5925.11   23.81 6278.93   25.58 8144.67    24.2 8553.77   24.65
 8633.78   27.34 8972.76   24.99 9002.92    28.1 9063.24   25.3212370.03   27.61
#Mann= 5 ,-1 , 0
       0     .99       0 2864.42     .08       0 4212.56    .045       0
 4403.42     .08       0 9002.92     .99       0
#Block Obstruct= 2 , 0
       0    2860   25.15               0
Bank Sta=4255.29,4365.82
XS Rating Curve= 0
Exp/Cntr=.3,.1

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
Type RM Length L Ch R = 1 ,35673.94,35.53,35.53,52.47
BEGIN DESCRIPTION:
Copy of 451s19u - xs 4/4 at west cedar bayou
Bank Station offset =       735
Cross section extended on LOB to contain 500 yr profile
END DESCRIPTION:
XS GIS Cut Line= 6
 3240999.134571213853266.8559372     3240668.807    13853300.138
     3236528.743    13853717.269     3236470.193    13853725.734
     3236329.843    13853752.511     3228444.985    13854875.759
#Sta/Elev= 30
    -332   27.79 1007.24   27.02 1493.49   25.93 1512.44   23.87 1528.71   27.22
 1560.61   24.72 2766.39   26.08 3962.72   23.02 4179.81   20.12  4250.7    7.25
 4285.59    7.25 4363.09      20 4379.88   17.17 4451.47   20.64 4594.97   22.26
 5363.93   23.11 5428.46   25.45 5530.61   23.27  5780.8   23.22  7431.3   24.41
 7517.07   26.44 7737.64   25.09 8227.55   24.18 8924.52   27.17 8954.82      25
 8985.12   27.66 9020.94   25.12 9691.57   24.8810212.39   27.3312327.53   28.06
#Mann= 6 ,-1 , 0
    -332     .99       0 2766.39     .08       0 4179.81    .045       0
 4285.59    .045       0 4379.88     .08       0 7737.64     .99       0
Bank Sta=4179.81,4363.09
XS Rating Curve= 0
Exp/Cntr=.5,.3

Type RM Length L Ch R = 1 ,35638.41,124.61,124.61,185.6
BEGIN DESCRIPTION:
451s19u - xs 3/4 at west cedar bayou
Bank Station offset =       735
Cross section extended on LOB to contain 500 yr profile
END DESCRIPTION:
XS GIS Cut Line= 6
 3240988.401593413853231.9677241     3240671.992    13853263.732
     3236535.613    13853678.982     3236473.378    13853689.328
     3236333.029    13853716.105     3228448.171    13854839.353
#Sta/Elev= 30
    -318   27.77 1511.06    24.5 1530.66   27.42 2749.87   25.65 3856.16   23.08
 3988.06   19.65 4029.16   21.96  4117.2   19.35 4153.78   22.43 4179.83      21
 4250.72    7.23 4285.61    7.23 4342.62      20 4372.83   15.75 4571.04   21.68
 5108.61   21.68 5427.83   24.72 5508.42   22.65 7227.23   25.09 7300.64   23.07
 7819.01   25.43 7912.66   23.05 8927.81   27.29 8956.45   24.78 8980.92    27.5
 9030.15   24.84 9460.35   26.84 9698.11   24.7310215.68   27.39 12327.6   27.72
#Mann= 6 ,-1 , 0
    -318     .99       0 2749.87     .08       0 4179.83    .045       0
 4285.61    .045       0 4342.62     .08       0 7819.01     .99       0
#XS Ineff= 2 , 0
       0    4211   22.12    4312       0    23.9
Permanent Ineff=
       F       F
Bank Sta=4179.83,4342.62
XS Rating Curve= 0
Exp/Cntr=.5,.3

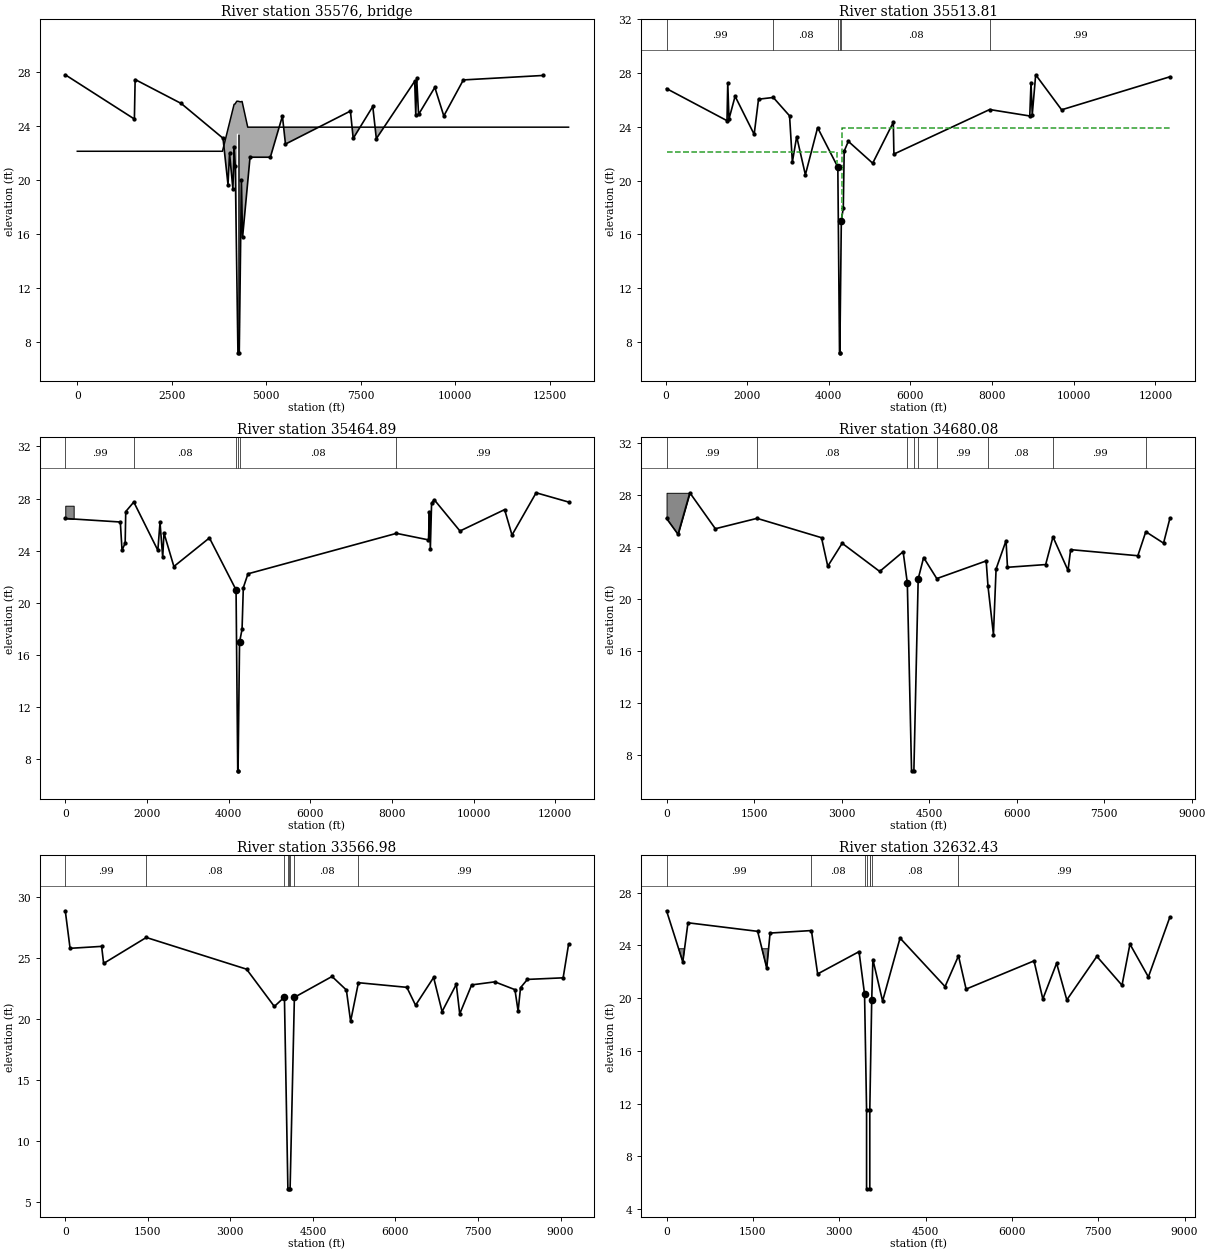
Type RM Length L Ch R = 3 ,35576   ,,,
BEGIN DESCRIPTION:
451s19: West Cedar Bayou "Conc. Bridge"
END DESCRIPTION:
Bridge Culvert--1,0,-1,-1, 0
Deck Dist Width WeirC Skew NumUp NumDn MinLoCord MaxHiCord MaxSubmerge Is_Ogee
47,31,2.6,0, 13, 13, , , .95, 0, 0,0,,
       0    3841 4149.42 4173.02 4221.72 4221.73    4265 4302.82 4302.83 4315.51
 4360.63    4510   13000
   22.12   22.12   25.59   25.61   25.82   25.82   25.81   25.78   25.78   25.77
    25.8    23.9    23.9
                                           23.42   23.41   23.38
                        
      25    3141 4149.42 4173.02 4221.72 4221.73    4265 4302.82 4302.83 4315.51
 4360.63    4510   13025
   22.12   22.12   25.59   25.61   25.82   25.82   25.81   25.78   25.78   25.77
    25.8    23.9    23.9
                                           23.42   23.41   23.38
                        
Pier Skew, UpSta & Num, DnSta & Num=  ,4248.66, 4 ,4248.66, 4 , 3 , 3 , 0 ,,
    1.35    1.35    1.85    1.85
       7   20.67   20.67   23.42
    1.35    1.35    1.85    1.85
       7   20.67   20.67   23.42
Pier Skew, UpSta & Num, DnSta & Num=  ,4275.82, 4 ,4275.82, 4 , 3 , 3 , 0 ,,
    1.35    1.35    1.85    1.85
       7   20.67   20.67   23.42
    1.35    1.35    1.85    1.85
       7   20.67   20.67   23.42
BR Coef=-1 , 0 , 0 ,, 0 ,,,.8,0,,0,
WSPro=,,,, 1 ,,,, 0 ,,,, 0 ,,,,-1 ,-1 ,-1 , 0 , 0 , 0 , 0 , 0
BC Design=,, 0 ,, 0 ,,,,,,
BC HTab HWMax=28.46

Type RM Length L Ch R = 1 ,35513.81,36.7,48.92,67.36
BEGIN DESCRIPTION:
Copy of 451s19u - xs 2/4 at west cedar bayou
Bank Station offset =       760
END DESCRIPTION:
XS GIS Cut Line= 6
     3240671.067    13853136.682     3236966.007    13853499.762
     3236527.116    13853557.315     3236471.688    13853565.734
     3236332.103    13853589.054     3228447.245    13854712.303
#Sta/Elev= 30
      25   26.85 1506.11   24.46 1524.23   27.28 1554.37   24.58 1704.22   26.28
  2171.1   23.44 2277.82   26.06 2638.96   26.19  3038.1   24.82 3106.73   21.38
 3212.28   23.27 3425.57   20.43 3725.07   23.94 4220.31      21 4261.43    7.16
 4269.43    7.16 4305.82      17 4353.91   17.97 4376.06   22.19 4477.41   22.92
 5073.95   21.29 5578.81   24.34 5593.66   21.97 7939.31   25.29 8921.47   24.81
 8951.78    27.3 8982.08   24.91 9066.33   27.88  9701.3   25.27 12352.5   27.73
#Mann= 6 ,-1 , 0
      25     .99       0 2638.96     .08       0 4220.31    .045       0
 4269.43    .045       0 4305.82     .08       0 7939.31     .99       0
#XS Ineff= 2 , 0
      25    4211   22.12    4312      25    23.9
Permanent Ineff=
       F       F
Bank Sta=4220.31,4305.82
XS Rating Curve= 0
Exp/Cntr=.5,.3

Type RM Length L Ch R = 1 ,35464.89,291.74,400,726.94
BEGIN DESCRIPTION:
Copy of 451s19u - xs 1/4 at west cedar bayou
Bank Station offset =       772
Manning's n = 0.99 used as special ineffective setting.  Flow in these areas is not anticipated to be effective.
END DESCRIPTION:
XS GIS Cut Line= 5
     3240670.733    13853090.572     3236534.353    13853507.604
     3236472.119    13853516.168     3236331.769    13853542.945
     3228446.911    13854666.193
#Sta/Elev= 30
       0   26.47 1348.55    26.2 1389.98   24.04 1466.91   24.58 1481.17      27
 1678.47   27.73 2267.37   24.03  2320.5   26.17 2386.56   23.48 2417.24   25.36
 2660.17   22.79 3530.91   24.98 4182.99      21 4224.11    7.13 4232.11    7.13
  4268.5      17 4329.75   17.97 4360.91   21.17 4474.65   22.23 8111.48   25.33
 8896.14   24.83 8917.93   26.99  8941.6   24.14  8971.9   27.65 9036.25   27.91
 9667.27   25.5110760.56   27.1510941.58    25.2 11532.6   28.4412327.51   27.73
#Mann= 6 ,-1 , 0
       0     .99       0 1678.47     .08       0 4182.99    .045       0
 4232.11    .045       0  4268.5     .08       0 8111.48     .99       0
#Block Obstruct= 2 , 0
       0   205.5   27.45               0
Bank Sta=4182.99,4268.5
XS Rating Curve= 0
Exp/Cntr=.3,.1

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
Type RM Length L Ch R = 1 ,34680.08,491.54,600.08,710.03
BEGIN DESCRIPTION:
451v26
Bank Station offset =       823
Manning's n = 0.99 used as special ineffective setting.  Flow in these areas is not anticipated to be effective.
END DESCRIPTION:
XS GIS Cut Line= 6
     3240708.089    13853042.448     3239872.145    13853073.102
     3236617.112    13852786.542     3236482.281    13852764.376
     3236097.613     13852694.51      3232112.87    13852414.012
#Sta/Elev= 30
       0   26.21   196.7   24.99  399.25   28.19  836.51   25.42    1551   26.22
 2656.01   24.73 2763.07   22.53 3010.16    24.3  3653.3   22.13 4055.06   23.65
 4126.72  21.244 4199.09    6.77 4239.09    6.77 4313.02   21.56 4405.94    23.2
 4631.73   21.58 5478.27   22.94 5509.18      21 5602.76   17.27 5647.87   22.32
 5818.64    24.5 5843.35   22.45 6497.68   22.66 6622.77   24.79 6880.91   22.21
 6926.02   23.81 8077.52   23.34 8214.05   25.19 8518.19   24.31 8626.33   26.21
#Mann= 9 ,-1 , 0
       0     .99       0    1551     .08       0 4126.72    .045       0
 4239.09    .045       0 4313.02     .08       0 4631.73     .99       0
 5509.18     .08       0 6622.77     .99       0 8214.05     .99       0
#Block Obstruct= 2 , 0
       0  399.25   28.19               0
Bank Sta=4126.72,4313.02
XS Rating Curve= 0
Exp/Cntr=.3,.1

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
Type RM Length L Ch R = 1 ,33566.98,995.25,934.56,926.07
BEGIN DESCRIPTION:
451v25
Bank Station offset =       928
END DESCRIPTION:
XS GIS Cut Line= 5
     3240764.178    13852739.795  3236972.85199513851877.0679209
 3236750.187857713851728.6251627      3232833.78    13850889.754
     3231922.338    13850601.762
#Sta/Elev= 30
       0   28.91   87.33   25.83   660.7   25.99  696.96   24.59 1472.41   26.72
 3294.19   24.12 3799.22   21.06 3982.41   21.83 4045.31     6.1 4065.31     6.1
 4085.31     6.1 4163.52   21.81  4847.5   23.52 5108.15   22.41 5184.81   19.84
 5326.76   23.01 6206.88   22.63 6365.41   21.16 6693.33   23.44 6847.17   20.64
 7105.76   22.88 7167.65   20.45 7384.75   22.83 7805.94   23.08 8170.98   22.44
 8228.75   20.68  8272.6    22.6 8397.59   23.28    9047   23.41 9146.04   26.17
#Mann= 8 ,-1 , 0
       0     .99       0 1472.41     .08       0 3982.41    .045       0
 4045.31    .025       0 4065.31    .025       0 4085.31    .045       0
 4163.52     .08       0 5326.76     .99       0
Bank Sta=3982.41,4163.52
XS Rating Curve= 0
Exp/Cntr=.3,.1

Type RM Length L Ch R = 1 ,32632.43,1243.94,1215.54,1185.9
BEGIN DESCRIPTION:
451v24
Bank Station offset =      1504
Block added in LOB since water cannot get into this area.
END DESCRIPTION:
XS GIS Cut Line= 5
     3240567.711    13851763.639     3237232.957    13850946.862
     3237086.277    13850924.173     3233161.369    13850266.501
     3231986.991    13850116.729
#Sta/Elev= 30
       0   26.63  282.88   22.75  372.29   25.72 1583.06   25.07 1741.16   22.28
 1798.87   24.94  2517.5   25.13 2625.34   21.84 3344.75   23.53 3440.49   20.31
 3475.58   11.54 3475.58    5.54 3531.58    5.54 3531.58   11.54 3564.72   19.83
 3585.51   22.93 3753.82   19.78 4057.17   24.56 4839.25   20.88 5072.73   23.21
 5204.88   20.69 6384.95   22.83  6538.1   19.94 6777.56   22.65  6954.8   19.87
 7476.91   23.17 7913.69   20.98  8051.8    24.1 8372.02   21.61 8745.27   26.15
#Mann= 8 ,-1 , 0
       0     .99       0  2517.5     .08       0 3440.49    .045       0
 3475.58    .025       0 3531.58    .025       0 3531.58    .045       0
 3564.72     .08       0 5072.73     .99       0
#Block Obstruct= 2 , 0
       0    2400   23.75               0
Bank Sta=3440.49,3564.72
XS Rating Curve= 0
Exp/Cntr=.3,.1