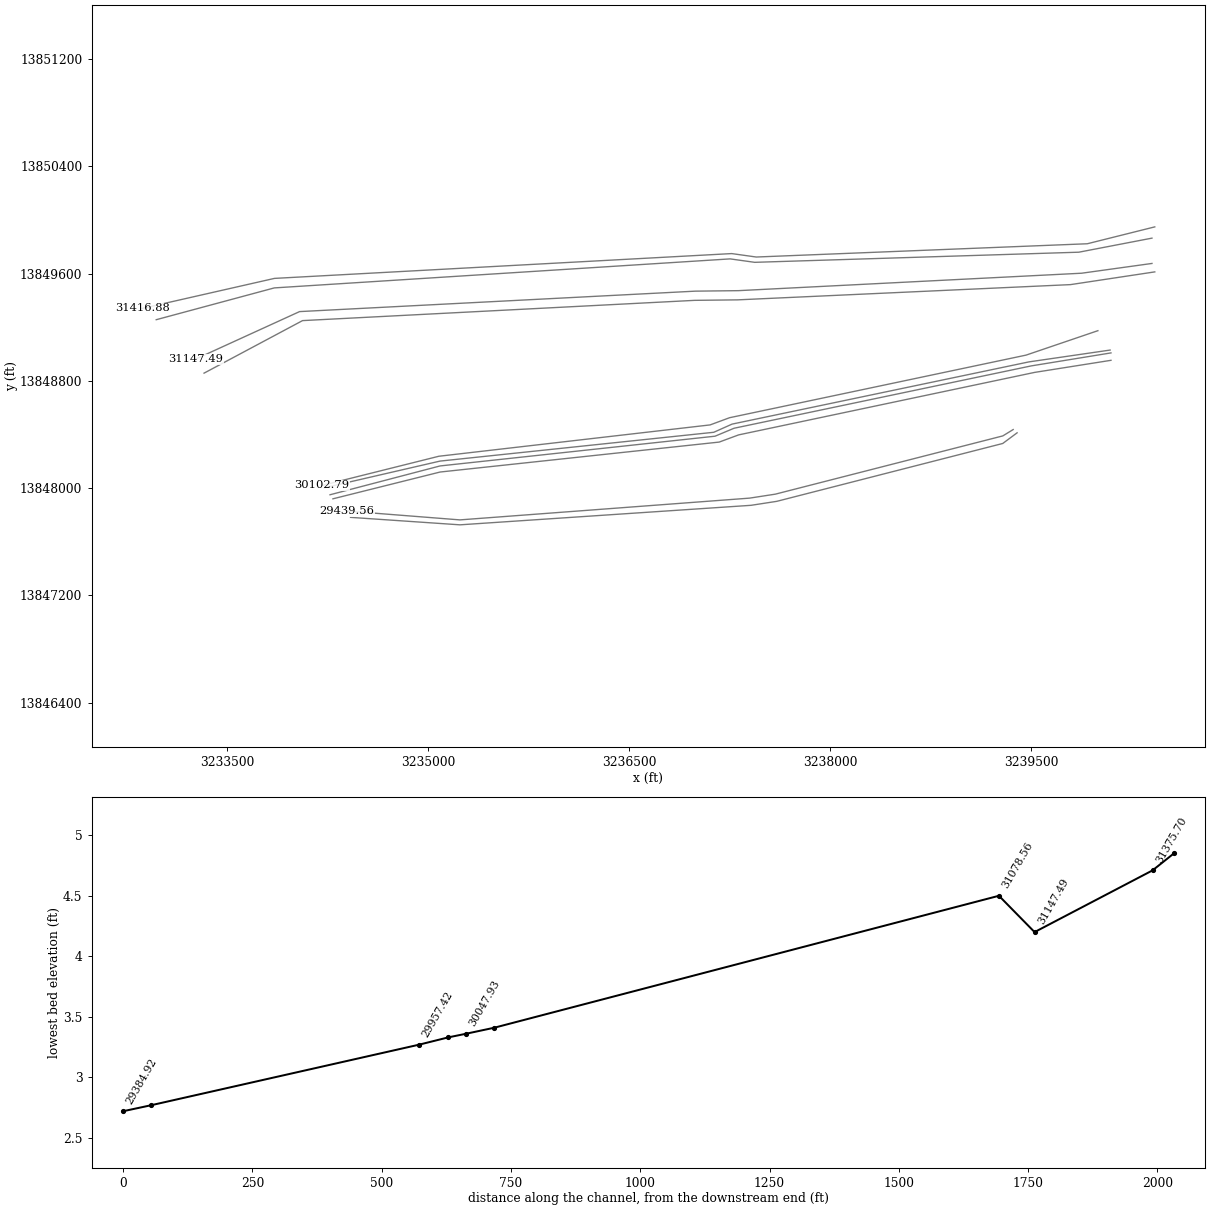
HEC-RAS study O100-00-00.prj: O100-00-00

--- O100-00-00.g01 (geometry) --- (continued)

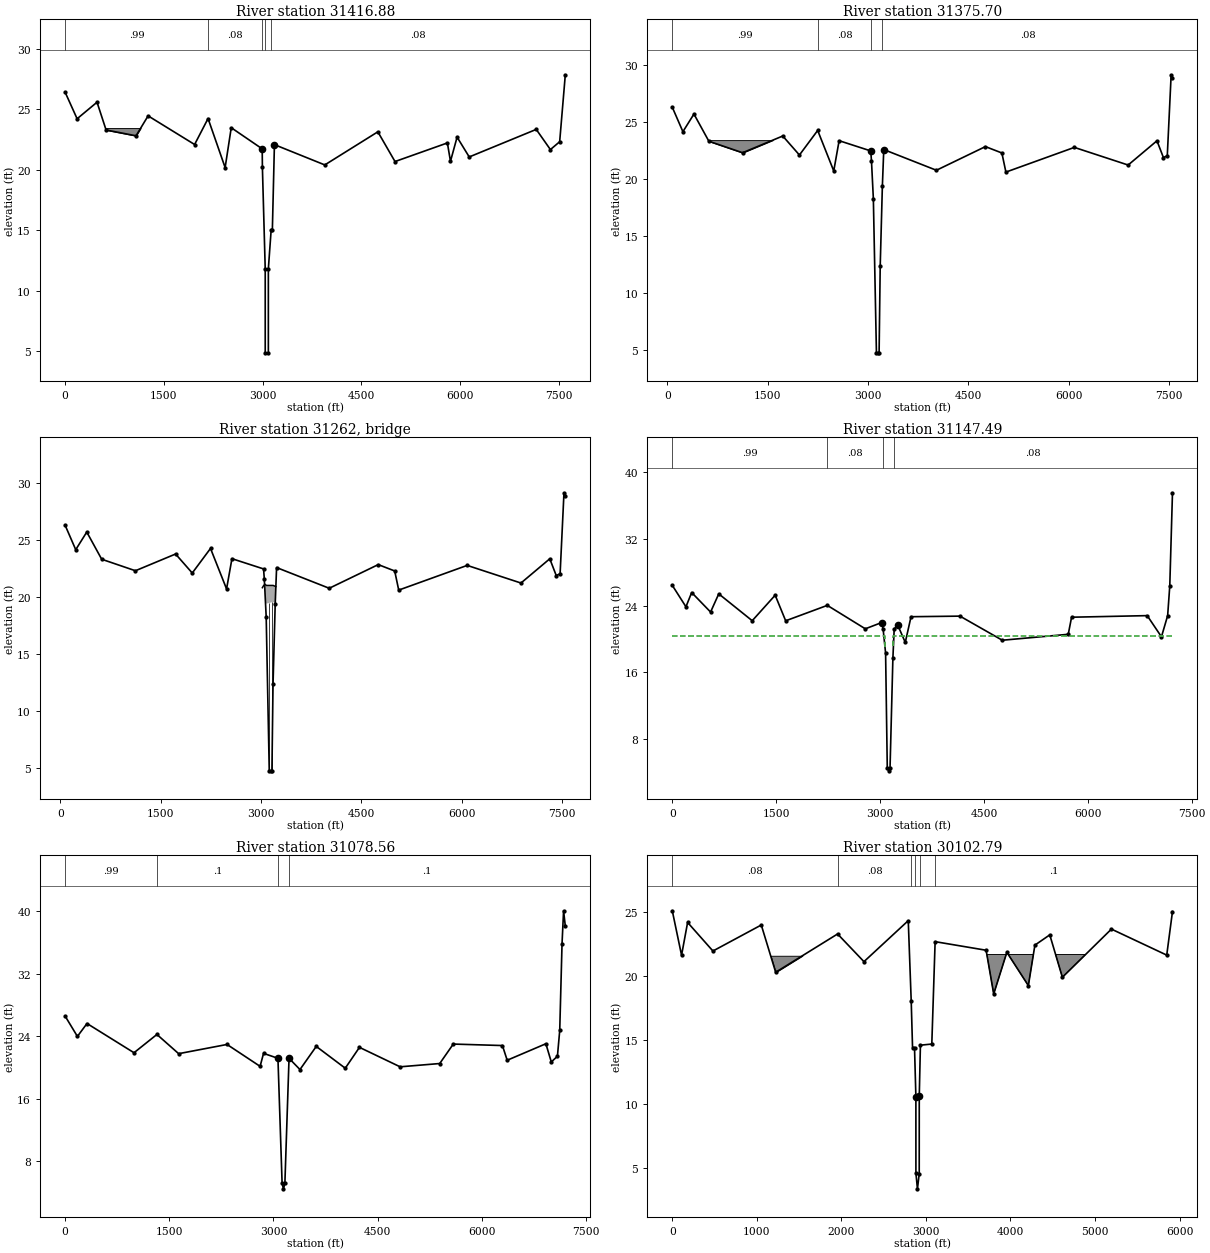
Type RM Length L Ch R = 1 ,31416.88,41.11,41.19,40.11
BEGIN DESCRIPTION:
Copy of 451s17d - xs 4/4 Baker road
Bank Station offset =      1948
Block added in LOB since water cannot get into this area.
END DESCRIPTION:
XS GIS Cut Line= 6
     3240420.852    13849948.891     3239917.338    13849823.012
       3237448.5    13849724.053     3237265.149     13849749.73
     3233854.549    13849564.635     3232868.141    13849340.478
#Sta/Elev= 30
       0   26.42  182.31   24.22  485.09   25.59  622.86   23.29 1077.81   22.81
 1261.44   24.46 1968.05   22.09  2172.5   24.24 2432.06   20.18 2524.85   23.48
 2995.45   21.73 2998.39   20.21 3041.35    11.8 3041.35    4.85 3088.95    4.85
 3088.95    11.8 3131.91   15.05 3149.96   15.05 3181.15   22.08 3946.85    20.4
 4753.03   23.14 5013.84   20.68 5810.01   22.22 5856.88    20.7 5957.44    22.7
 6141.85   21.06 7160.32   23.34 7375.67   21.67 7516.44   22.32 7602.15   27.86
#Mann= 5 ,-1 , 0
       0     .99       0  2172.5     .08       0 2998.39    .045       0
 3041.35    .015       0 3131.91     .08       0
#Block Obstruct= 2 , 0
       0    1300   23.45               0
Bank Sta=2995.45,3181.15
XS Rating Curve= 0
Exp/Cntr=.5,.3

Type RM Length L Ch R = 1 ,31375.70,210.41,228.21,228.5
BEGIN DESCRIPTION:
Copy of 451s17d - xs 3/4 Baker road
Bank Station offset =      1975
Block added in LOB since water cannot get into this area.
END DESCRIPTION:
XS GIS Cut Line= 6
     3240399.873    13849864.971     3239854.399    13849760.073
     3237436.867    13849684.501     3237253.516    13849710.177
     3233853.781    13849493.745      3232973.04    13849256.559
#Sta/Elev= 30
      73   26.29  231.75   24.14  396.82   25.69  619.94    23.3 1124.13   22.29
 1724.42   23.76 1973.83   22.09 2246.74   24.25 2486.83   20.69  2567.1   23.35
  3039.8   22.45 3050.73    21.6  3079.1   18.25    3125    4.73    3145    4.71
    3165    4.73 3181.36    12.3  3213.8   19.36 3234.69   22.57 4021.75   20.75
  4754.4   22.83 5000.43   22.27 5060.55   20.59 6084.01   22.76 6888.26   21.21
 7318.96   23.34 7415.45   21.87 7473.37   22.02 7531.21   29.14 7551.06   28.86
#Mann= 4 ,-1 , 0
      73     .99       0 2246.74     .08       0 3050.73    .045       0
  3213.8     .08       0
#Block Obstruct= 2 , 0
       0    1680    23.4               0
Bank Sta=3039.8,3234.69
XS Rating Curve= 0
Exp/Cntr=.5,.3

Type RM Length L Ch R = 3 ,31262   ,,,
BEGIN DESCRIPTION:
451s17: Baker Rd. South Bridge "Conc. Bridge"
this is a combined bridge of North and South Baker Rd due to their close proximity flow will not expand/contract between the structures; the piers used are from So. Baker with the leftmost pier set doubled in width to account for offset of peirs between No. & So. (mbb) 451s17/18
END DESCRIPTION:
Bridge Culvert--1,0,-1,-1, 0
Deck Dist Width WeirC Skew NumUp NumDn MinLoCord MaxHiCord MaxSubmerge Is_Ogee
69,90,2.6,0, 7, 7, , , .95, 0, 0,0,,
    3022    3042    3062    3082    3163    3183    3223
    20.8      21    21.1      21      21      21    20.9
                   19.35    19.4   19.52   19.52   19.52
    3024    3044    3064    3084    3165    3185    3225
    20.3    20.4    20.4   20.45    20.5    20.6    20.6
                   18.37    18.3   18.03   18.03       0
Pier Skew, UpSta & Num, DnSta & Num=  ,3124.93, 2 ,3104.58, 2 , 0 , 0 , 0 ,,
       2       2
       0   19.52
       2       2
       0   18.37
Pier Skew, UpSta & Num, DnSta & Num=  ,3164.93, 2 ,3144.58, 2 , 0 , 0 , 0 ,,
       2       2
       0   19.52
       2       2
       0   18.18
BR Coef=-1 , 0 , 0 ,, 0 ,,,.8,0,,0,
WSPro=,,,, 1 ,,,, 0 ,,,, 0 ,,,,-1 ,-1 ,-1 , 0 , 0 , 0 , 0 , 0
BR D #Sta/Elev= 200
       0   26.44   40.24    26.5   51.38   26.46   60.06   26.31  197.31   23.87
  216.69   23.89  245.17   23.92  271.68   25.23  280.07   25.58  339.33   25.41
  372.43    24.8  410.28   25.29   438.4   24.74  490.55   23.78  530.09   23.45
  552.92   23.24  591.01   24.27  655.93   24.85   671.1   25.42  692.58    24.9
  754.65    24.6   798.8   24.37  831.47   23.89     906   23.96  941.55   24.27
  977.59   23.63 1024.61   23.92 1044.09   23.78 1062.17   22.67 1086.43   22.42
 1154.31    22.2 1182.33   22.61 1203.34   22.84 1251.17   23.44 1301.92   23.89
 1323.56   24.01 1375.53   24.65 1434.63   24.76 1458.83   25.16 1467.13   25.13
 1479.24   25.21  1485.8   25.26 1557.25   24.96 1586.52   23.87 1637.33   22.19
 1656.29   22.97 1681.88    23.5 1742.05   23.73 1749.41   23.58 1755.68   23.58
  1805.4   23.19 1902.18   23.84  1926.6   23.62  1938.5   23.66 2048.88   23.05
 2152.68   23.94 2168.16   23.67 2204.58    23.7 2228.16   23.67 2238.76   24.04
 2266.69   24.04 2330.52   23.97 2352.54    23.9 2389.98   23.99 2456.71   23.71
  2484.3   23.64 2507.32   23.37 2571.06   23.28 2612.86   22.47 2646.95    22.7
 2702.23   22.68 2760.23   22.61 2787.55   21.23 2834.52   21.87 2861.04   22.25
  2870.8    22.2 2920.23   22.29 3023.32   21.98 3042.72   21.47 3068.06   20.64
 3079.95   18.69 3105.94    5.78 3124.58    4.47 3146.65    5.69 3179.65   17.03
 3207.16   20.14 3209.09   20.43 3210.78   20.55 3236.36    21.2 3254.21   21.67
  3254.5   21.69 3255.13   21.69 3299.76   21.76 3338.61   20.33  3349.7   19.64
 3364.56    19.6 3373.47    20.1 3404.86   22.15 3414.79   22.34  3425.2   22.55
 3447.57   22.68 3455.81   22.71 3525.81    21.7 3577.56   22.66 3597.26   22.64
 3631.62   22.71 3655.27   22.17 3689.13    22.3 3770.14   21.52 3828.66   21.81
 3871.09   21.96 3936.37   21.69 3993.13   22.08 4015.88   22.42  4044.6   22.25
 4044.94   22.26 4065.77   22.63  4110.8   22.56 4154.57   22.75 4156.09   22.74
 4162.06   22.73  4189.4   22.45 4220.18   22.14 4249.48   22.03  4305.6   21.17
 4334.47   21.87 4337.67   21.88 4365.04   21.81 4368.22   21.82 4388.85    21.9
 4504.33   21.78 4529.23   21.67 4569.57   21.58 4730.24   20.31 4765.35   19.86
 4811.77   19.98 4861.94   20.71 5019.01   21.22 5045.77   20.79 5057.06   20.77
 5073.14   20.77 5197.93   21.18 5207.26   21.14 5213.31   21.16 5222.21   21.21
 5372.48   20.44  5416.7   20.94  5491.4   22.02 5582.99   21.94 5660.49   21.98
 5673.72   21.88 5677.29   21.76 5717.94   20.57  5754.6   22.28    5766   22.62
 5805.25   21.84 5855.56      22 5936.32   22.11  6006.2   21.23 6034.57   21.56
  6167.5   22.23 6168.54   22.23 6168.78   22.23 6173.51   22.27 6245.12   22.64
 6250.24   22.64 6283.35   22.54 6339.08   22.18 6348.78   22.09 6370.74   22.05
 6382.35   22.25 6392.42   22.11 6426.03   22.44 6428.56   22.44 6445.57   22.48
 6449.37   22.54 6456.78   22.58 6589.89   22.48 6608.96   22.15 6667.33   21.85
 6711.92   21.52 6735.97    21.8 6858.25   22.81 6921.13   22.36 6961.64   22.42
 6987.43   22.11 7001.52   22.11 7044.47   21.33 7063.92   20.27 7082.17      21
 7116.26   22.31 7121.71   22.11  7138.9   21.66  7153.4   22.81 7171.18   24.78
 7184.18    26.4 7212.62   35.31 7218.14   37.18 7220.66    37.3 7223.11   37.54
BR D #Mann= 4
       0     .99  1485.8     .08 3105.94    .025 3179.65     .08
BR D Banks=3079.95,3179.65
BC Design=,, 0 ,, 0 ,,,,,,
BC HTab HWMax=29.17

Type RM Length L Ch R = 1 ,31147.49,70.21,68.93,68.72
BEGIN DESCRIPTION:
451s17d - xs 2/4 Baker road
Bank Station offset =      1875
Lower channel Manning's n reflects concrete channel
Block added in ROB since water cannot get into this area.
END DESCRIPTION:
XS GIS Cut Line= 6
     3240399.873    13849676.154     3239874.818    13849603.272
     3237315.176    13849473.205     3236994.062    13849469.506
     3234042.051    13849317.024     3233266.756    13848962.842
#Sta/Elev= 30
       0   26.44  197.31   23.87  280.07   25.58  552.92   23.24   671.1   25.42
 1154.31    22.2  1485.8   25.26 1637.33   22.19 2238.76   24.04 2787.55   21.23
 3023.32   21.98 3044.73    21.2 3080.35   18.32 3104.58     4.6 3124.58     4.2
 3144.58     4.6  3185.7   17.72 3204.43    21.2  3254.5   21.69 3364.56    19.6
 3447.57   22.68 4154.57   22.75 4765.35   19.86 5717.94   20.57    5766   22.62
 6858.25   22.81 7063.92   20.27  7153.4   22.81 7184.18    26.4 7223.11   37.54
#Mann= 4 ,-1 , 0
       0     .99       0 2238.76     .08       0 3044.73    .025       0
 3204.43     .08       0
#XS Ineff= 2 , 0
       0 3071.91   20.38 3193.56       0   20.38
Permanent Ineff=
       F       F
#Block Obstruct= 2 , 0
       0                    5852       0    21.9
Bank Sta=3023.32,3254.5
XS Rating Curve= 0
Exp/Cntr=.5,.3

Type RM Length L Ch R = 1 ,31078.56,881.48,975.77,941.09
BEGIN DESCRIPTION:
Copy of 451s17d - xs 1/4 Baker road
Bank Station offset =      1855
Lower channel Manning's n reflects concrete channel
Block added in ROB since water cannot get into this area.
higher c/e coefficients used to avoid negative WSELs.
END DESCRIPTION:
XS GIS Cut Line= 6
     3240420.852    13849613.214     3239791.966    13849518.239
     3237309.359     13849404.57     3236988.245    13849400.871
     3234064.334     13849249.84     3233329.696    13848857.943
#Sta/Elev= 30
       0    26.6  176.92      24   315.4   25.65  992.13   21.91 1322.05   24.25
 1635.38   21.79 2331.92   22.97 2807.95   20.17 2857.77   21.83 3065.08    21.2
 3124.93     5.2 3144.93     4.5 3164.93     5.2 3224.78    21.2 3382.19   19.76
 3616.88   22.72 4034.47   19.93 4238.96    22.6 4824.43   20.11 5394.84   20.53
  5590.1   23.02 6298.13   22.83 6366.43   20.95 6923.64   23.06 7001.75   20.73
 7089.94   21.46  7123.2   24.77 7156.46   35.88 7178.63   40.07 7203.43   38.11
#Mann= 4 ,-1 , 0
       0     .99       0 1322.05      .1       0 3065.08    .025       0
 3224.78      .1       0
#Block Obstruct= 2 , 0
       0                    5835       0    21.7
Bank Sta=3065.08,3224.78
XS Rating Curve= 0
Exp/Cntr=.4,.2

Type RM Length L Ch R = 1 ,30102.79,54.85,54.85,62.2
BEGIN DESCRIPTION:
451s16u - xs 4/4 cart bridge
Bank Station offset =      2100
Lower channel Manning's n reflects concrete channel
Block added in LOB and ROB since water cannot get into this area.
END DESCRIPTION:
XS GIS Cut Line= 6
     3239996.477    13849174.631     3239460.975    13848992.489
     3237249.264    13848525.521     3237104.287    13848471.889
       3235081.1    13848238.128      3234208.84    13848019.987
#Sta/Elev= 30
       0   25.11  109.68   21.64  181.22    24.2  480.79   21.97 1052.63      24
 1222.99   20.31 1955.14    23.3 2267.22   21.14 2791.17   24.34 2826.09   18.06
 2841.78   14.44 2865.16   14.43 2881.31   10.61 2881.65    4.64 2899.76    3.41
 2920.87    4.58 2921.33   10.65 2934.94   14.62 3069.64   14.71 3108.93    22.7
 3712.13   22.03 3801.85   18.62 3957.44   21.87 4211.71   19.27 4289.14   22.43
  4465.1   23.23    4614   19.92 5194.07   23.68 5848.54   21.65 5916.45   25.05
#Mann= 6 ,-1 , 0
       0     .08       0 1955.14     .08       0 2826.09     .04       0
 2865.16    .025       0 2934.94     .04       0 3108.93      .1       0
#XS Ineff= 2 , 0
       0 2791.17   24.34 3108.93       0    22.7
Permanent Ineff=
       F       F
#Block Obstruct= 2 ,-1
     100    1843    21.6    3110    5900    21.7
Bank Sta=2881.31,2921.33
XS Rating Curve= 0
Exp/Cntr=.5,.3

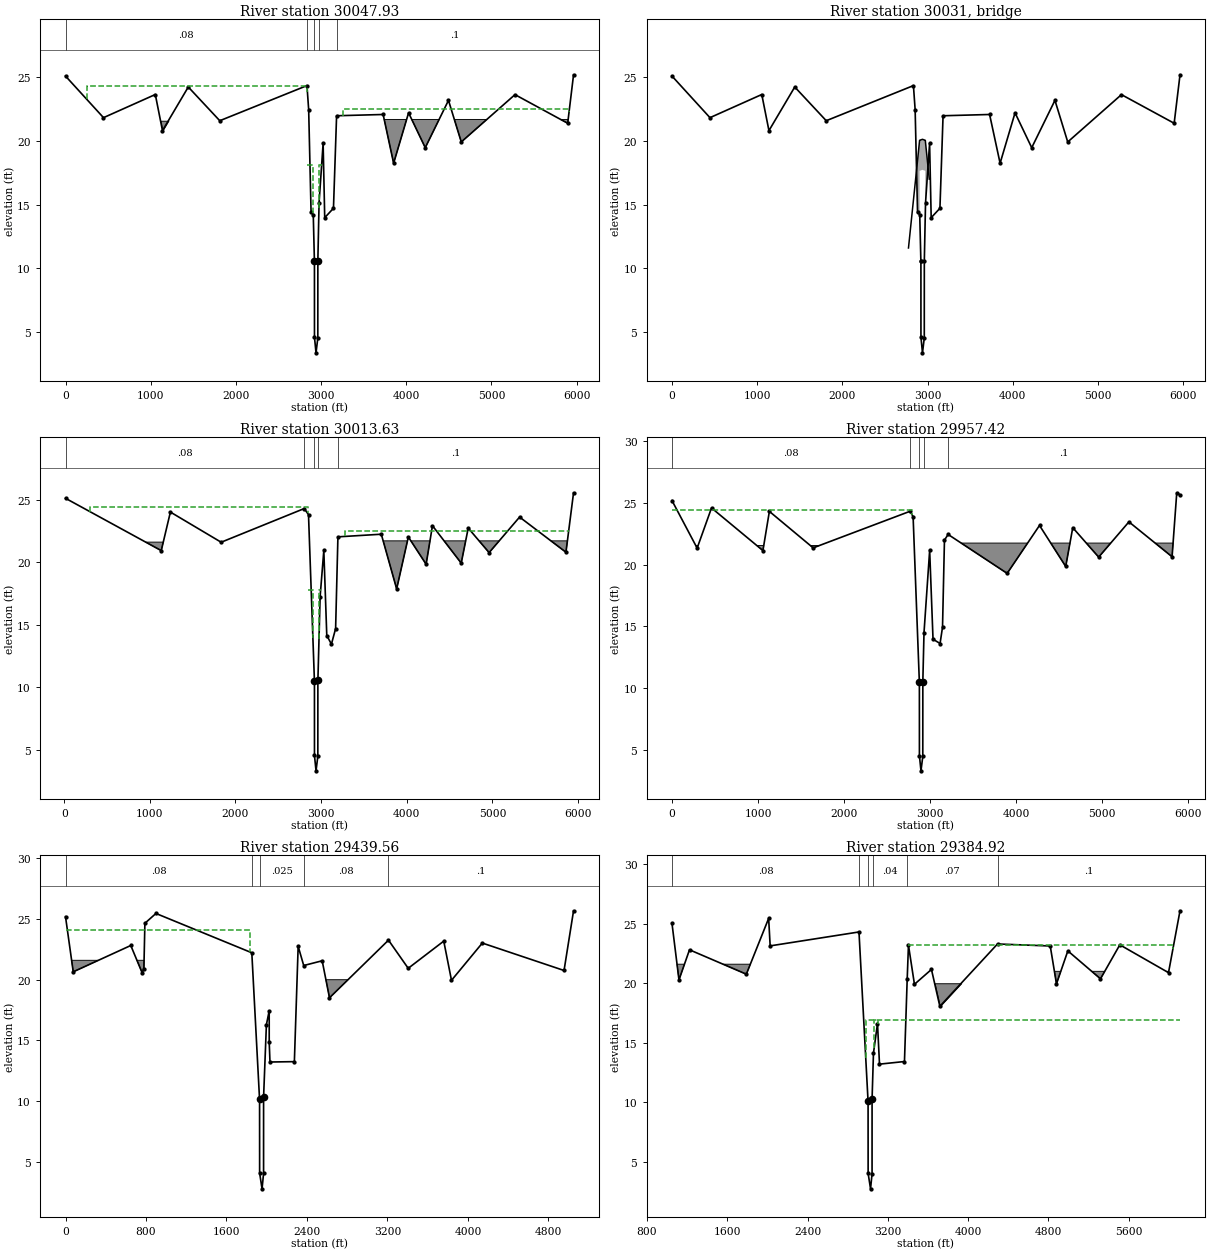
Type RM Length L Ch R = 1 ,30047.93,37.46,34.31,33.01
BEGIN DESCRIPTION:
Copy of 451s16u - xs 3/4 cart bridge
Bank Station offset =      2060
Lower channel Manning's n reflects concrete channel
LOB "n" value reflects maintained golf course
Block added in LOB and ROB since water cannot get into this area.
END DESCRIPTION:
XS GIS Cut Line= 6
     3240087.832    13849030.163     3239482.134    13848941.917
     3237268.168      13848477.9     3237131.527    13848416.884
     3235089.922    13848202.041     3234226.117     13848002.71
#Sta/Elev= 30
       0   25.11  445.87   21.84 1054.12   23.66 1138.22   20.82 1441.15   24.25
 1810.73    21.6 2834.22   24.36 2854.19   22.47 2882.45   14.39    2908   14.23
 2921.61   10.56 2921.98   10.56 2922.32    4.59 2940.43    3.36 2961.54    4.53
    2962    10.6 2976.22   15.15 3023.84   19.83  3042.5   13.98 3145.26   14.72
 3181.91   21.99 3728.19   22.09  3851.4   18.26 4026.88   22.22 4222.57   19.48
 4495.16    23.2 4645.27   19.93 5275.91   23.65 5894.54    21.4 5963.21   25.21
#Mann= 5 ,-1 , 0
       0     .08       0 2834.22     .04       0 2921.61    .025       0
 2976.22     .04       0 3181.91      .1       0
#XS Ineff= 4 ,-1
     250 2839.21   24.36    3260    5910    22.5    2975    3009    18.1
 2839.21    2904    18.1
Permanent Ineff=
       F       F       F       F
#Block Obstruct= 2 ,-1
     200    1985    21.6    3300    5900    21.7
Bank Sta=2921.98,2962
XS Rating Curve= 0
Exp/Cntr=.5,.3

Type RM Length L Ch R = 3 ,30031   ,,,
BEGIN DESCRIPTION:
451s16: Goose Creek Country Club Cart Path "Conc.
END DESCRIPTION:
Bridge Culvert--1,0,-1,-1, 0
Deck Dist Width WeirC Skew NumUp NumDn MinLoCord MaxHiCord MaxSubmerge Is_Ogee
11,12.2,2.6,0, 8, 8, , , .95, 0, 0,0,,
    2776 2876.66 2906.46 2906.47    2940 2973.45 2973.46    3020
    11.6    18.1   20.06   20.06   20.14   20.06   20.06   17.01
                           17.66   17.74   17.66
    2776 2876.66 2906.46 2906.47    2940 2973.45 2973.46    3020
    11.6    18.1   20.06   20.06   20.14   20.06   20.06   17.01
                           17.66   17.74   17.66
BR Coef=-1 , 0 , 0 ,, 0 ,,,.8,0,,0,
WSPro=,,,, 1 ,,,, 0 ,,,, 0 ,,,,-1 ,-1 ,-1 , 0 , 0 , 0 , 0 , 0
BC Design=,, 0 ,, 0 ,,,,,,
BC HTab HWMax=25.31

Type RM Length L Ch R = 1 ,30013.63,67.4,56.21,51.33
BEGIN DESCRIPTION:
Copy of 451s16u - xs 2/4 cart bridge
Bank Station offset =      2075
Lower channel Manning's n reflects concrete channel
LOB "n" value reflects maintained golf course
Block added in LOB and ROB since water cannot get into this area.
END DESCRIPTION:
XS GIS Cut Line= 6
     3240094.206    13849008.918      3239499.17    13848911.985
     3237282.778    13848446.962      3237140.98    13848387.665
     3235090.096    13848165.856     3234269.311    13847950.877
#Sta/Elev= 30
      15    25.1 1133.05   20.92 1239.71      24  1832.7   21.59 2802.55   24.28
 2852.54   23.79 2921.58   10.53 2921.95   10.53 2922.29    4.56  2940.4    3.33
 2961.51     4.5 2961.97   10.57 2962.45   10.59 2988.27   17.25 3031.38   20.93
 3065.99   14.14  3120.2   13.45 3169.14   14.69 3196.08   22.02 3702.53   22.23
    3882   17.86 4018.47   22.01 4226.16   19.83 4300.02   22.91 4635.96   19.92
 4717.64   22.72 4961.57   20.76 5317.47    23.6 5858.89   20.79 5947.55   25.54
#Mann= 5 ,-1 , 0
      15     .08       0 2802.55     .04       0 2921.58    .025       0
 2962.45     .04       0 3196.08      .1       0
#XS Ineff= 4 ,-1
     300 2842.55    24.4 3277.89    5900   22.45    2975    3004    17.8
 2842.55    2904    17.8
Permanent Ineff=
       F       F       F       F
#Block Obstruct= 2 ,-1
     100    2015    21.6    3300    5900    21.7
Bank Sta=2921.95,2961.97
XS Rating Curve= 0
Exp/Cntr=.5,.3

Type RM Length L Ch R = 1 ,29957.42,524.46,517.85,480.33
BEGIN DESCRIPTION:
Copy of 451s16u - xs 1/4 cart bridge
Bank Station offset =      2106
Lower channel Manning's n reflects concrete channel
LOB "n" value reflects maintained golf course
Block added in LOB and ROB since water cannot get into this area.
END DESCRIPTION:
XS GIS Cut Line= 6
     3240094.206     13848953.68     3239524.576    13848863.535
     3237317.155    13848397.474     3237172.178    13848343.842
     3235090.332     13848120.46     3234290.908    13847920.642
#Sta/Elev= 30
       0    25.2  292.57   21.34  459.68    24.6 1057.13   21.14 1132.16   24.32
 1641.16   21.36 2767.92   24.33 2802.86   23.89 2875.46   10.47 2875.83   10.47
 2876.17     4.5 2894.28    3.27 2915.39    4.44 2915.85   10.51 2929.46   14.48
 2995.23   21.16 3034.33   13.95 3116.17    13.6 3144.73   14.93  3167.2   21.99
  3209.6   22.45 3896.06   19.29 4272.03   23.18 4576.73   19.85 4658.47      23
 4959.76   20.61 5311.37   23.47 5812.92   20.64  5867.3   25.83  5905.2   25.66
#Mann= 5 ,-1 , 0
       0     .08       0 2767.92     .04       0 2875.46    .025       0
 2929.46     .04       0  3209.6      .1       0
#XS Ineff= 2 , 0
       0 2792.88   24.44  3209.6       0   22.45
Permanent Ineff=
       F       F
#Block Obstruct= 2 ,-1
     100    1975   21.55    3250    5900   21.75
Bank Sta=2875.83,2915.85
XS Rating Curve= 0
Exp/Cntr=.3,.1

Type RM Length L Ch R = 1 ,29439.56,54.64,54.64,58.67
BEGIN DESCRIPTION:
451s15u - xs 4/4 cart bridge
Bank Station offset =      3047
Lower channel Manning's n reflects concrete channel
Block added in ROB since water cannot get into this area.
END DESCRIPTION:
XS GIS Cut Line= 6
     3239364.622    13848437.238     3239287.478    13848389.894
     3237591.076    13847955.476     3237399.031    13847925.815
     3235237.906     13847763.46     3234394.641    13847829.778
#Sta/Elev= 30
       0    25.2   76.79   20.65  648.68   22.82  761.75   20.57     779   20.91
  788.97   24.65  898.73   25.46 1851.54   22.22 1928.22   10.19 1928.76   10.15
 1929.31    4.07 1953.34    2.77 1968.47    4.04 1968.57   10.32 1996.53   16.29
 2024.39   17.44 2024.59   14.83 2032.18   13.22 2274.56   13.25 2312.21   22.75
 2367.44   21.17 2550.94   21.56 2623.56   18.51 3209.87   23.26 3405.98   20.94
  3759.2   23.18 3836.12   19.95 4142.44   23.02 4954.66   20.76 5049.12   25.68
#Mann= 5 ,-1 , 0
       0     .08       0 1851.54     .04       0 1928.22    .025       0
 2367.44     .08       0 3209.87      .1       0
#XS Ineff= 2 , 0
       0 1836.67   24.13 2312.21       0   22.75
Permanent Ineff=
       F       F
#Block Obstruct= 3 ,-1
      50    1000    21.6    2042    2282   13.12    2310    4996      20
Bank Sta=1928.76,1968.57
XS Rating Curve= 0
Exp/Cntr=.5,.3

Type RM Length L Ch R = 1 ,29384.92,37.38,35.23,35.23
BEGIN DESCRIPTION:
Copy of 451s15u - xs 3/4 cart bridge
Bank Station offset =      3022
Lower channel Manning's n reflects concrete channel
Block added in ROB since water cannot get into this area.
END DESCRIPTION:
XS GIS Cut Line= 6
     3239393.883    13848412.854     3239286.948    13848333.441
     3237601.398    13847901.802     3237409.353    13847872.141
     3235238.284    13847726.593     3234422.357    13847782.266
#Sta/Elev= 30
 1049.32   25.04 1119.07   20.28 1223.94   22.81 1790.21   20.76 2012.49   25.45
 2027.49   23.14 2912.46   24.31 3002.45   10.14 3002.99    10.1 3003.54    4.02
 3027.57    2.72  3042.7    3.99  3042.8   10.27 3056.72   14.13 3096.85   16.61
 3116.78    13.2 3365.51   13.42  3392.9   20.39 3405.31    23.2    3465   19.91
 3634.41   21.16 3718.11   18.06 4292.42    23.3 4817.78   23.13 4879.88   19.95
 4993.21   22.72 5318.31   20.37 5511.02   23.23 5996.01   20.89 6110.64   26.09
#Mann= 6 ,-1 , 0
 1049.32     .08       0 2912.46     .04       0 3002.45    .025       0
 3056.72     .04       0  3392.9     .07       0 4292.42      .1       0
#XS Ineff= 4 ,-1
    1050 2912.46   24.31    2980    2955   16.93 3405.31    6040    23.2
 3063.32    3097   16.93
Permanent Ineff=
       F       F       F       F
#Block Obstruct= 4 ,-1
    1100    2000    21.6    3108    3358   13.12    3500    4290      20
    4290    6080      21
Bank Sta=3002.99,3042.8
XS Rating Curve= 0
Exp/Cntr=.5,.3

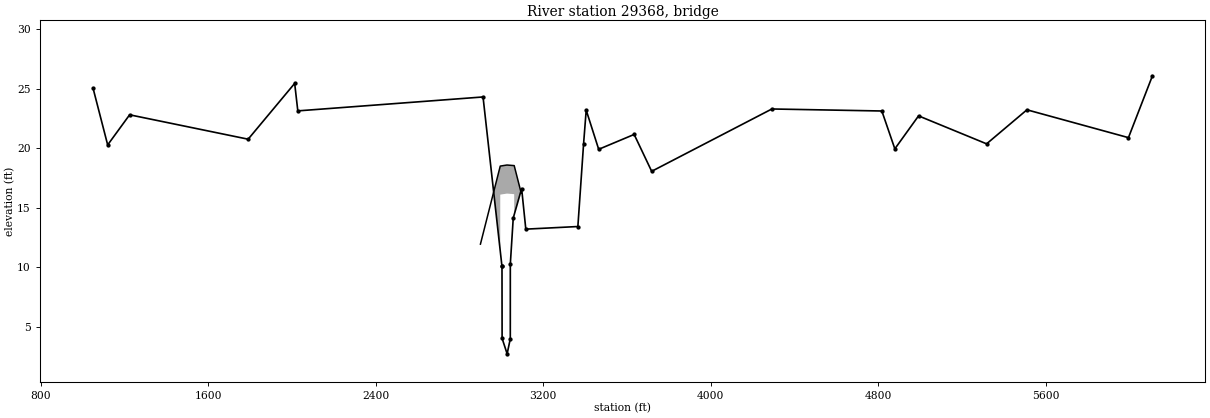
Type RM Length L Ch R = 3 ,29368   ,,,
BEGIN DESCRIPTION:
451s15: Cart Path (Goose Creek Country Club) " Conc.
END DESCRIPTION:
Bridge Culvert--1,0,-1,-1, 0
Deck Dist Width WeirC Skew NumUp NumDn MinLoCord MaxHiCord MaxSubmerge Is_Ogee
11.5,12.2,2.6,0, 5, 5, , , .95, 0, 0,0,,
    2900 2994.66 3026.91 3061.32    3095
   11.94    18.5   18.59   18.54   16.22
            16.1   16.19   16.14
    2900 2995.34 3027.59    3062    3095
   11.94    18.5   18.59   18.54   16.22
            16.1   16.19   16.14
BR Coef=-1 , 0 , 0 ,, 0 ,,,.8,0,,0,
WSPro=,,,, 1 ,,,, 0 ,,,, 0 ,,,,-1 ,-1 ,-1 , 0 , 0 , 0 , 0 , 0
BC Design=,, 0 ,, 0 ,,,,,,
BC HTab HWMax=26.09