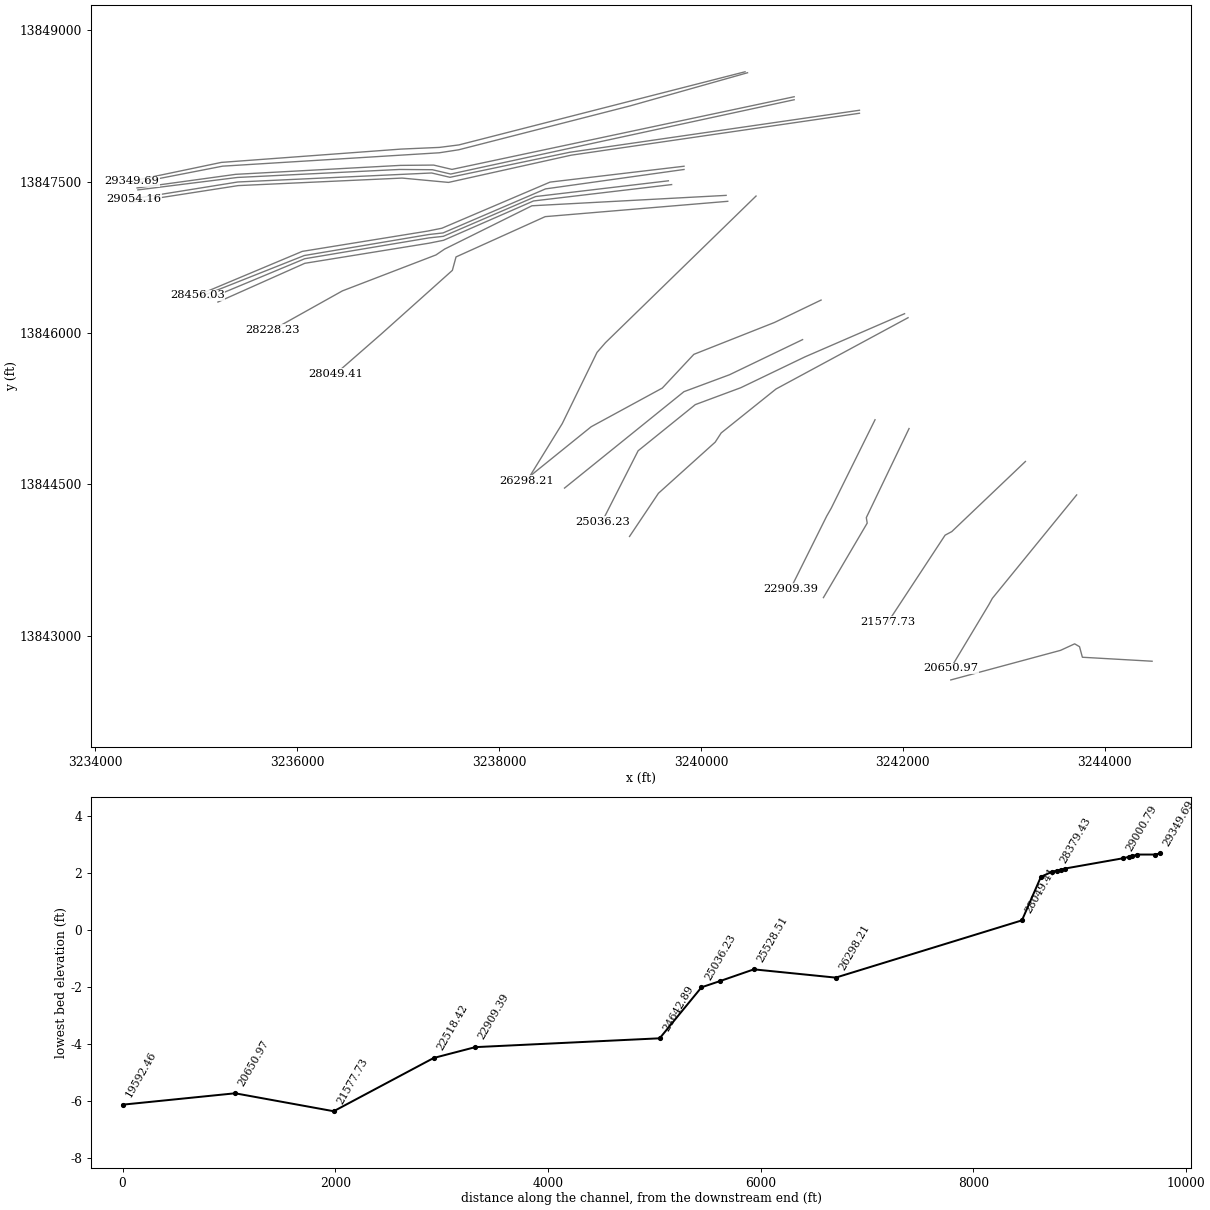
HEC-RAS study O100-00-00.prj: O100-00-00

--- O100-00-00.g01 (geometry) --- (continued)

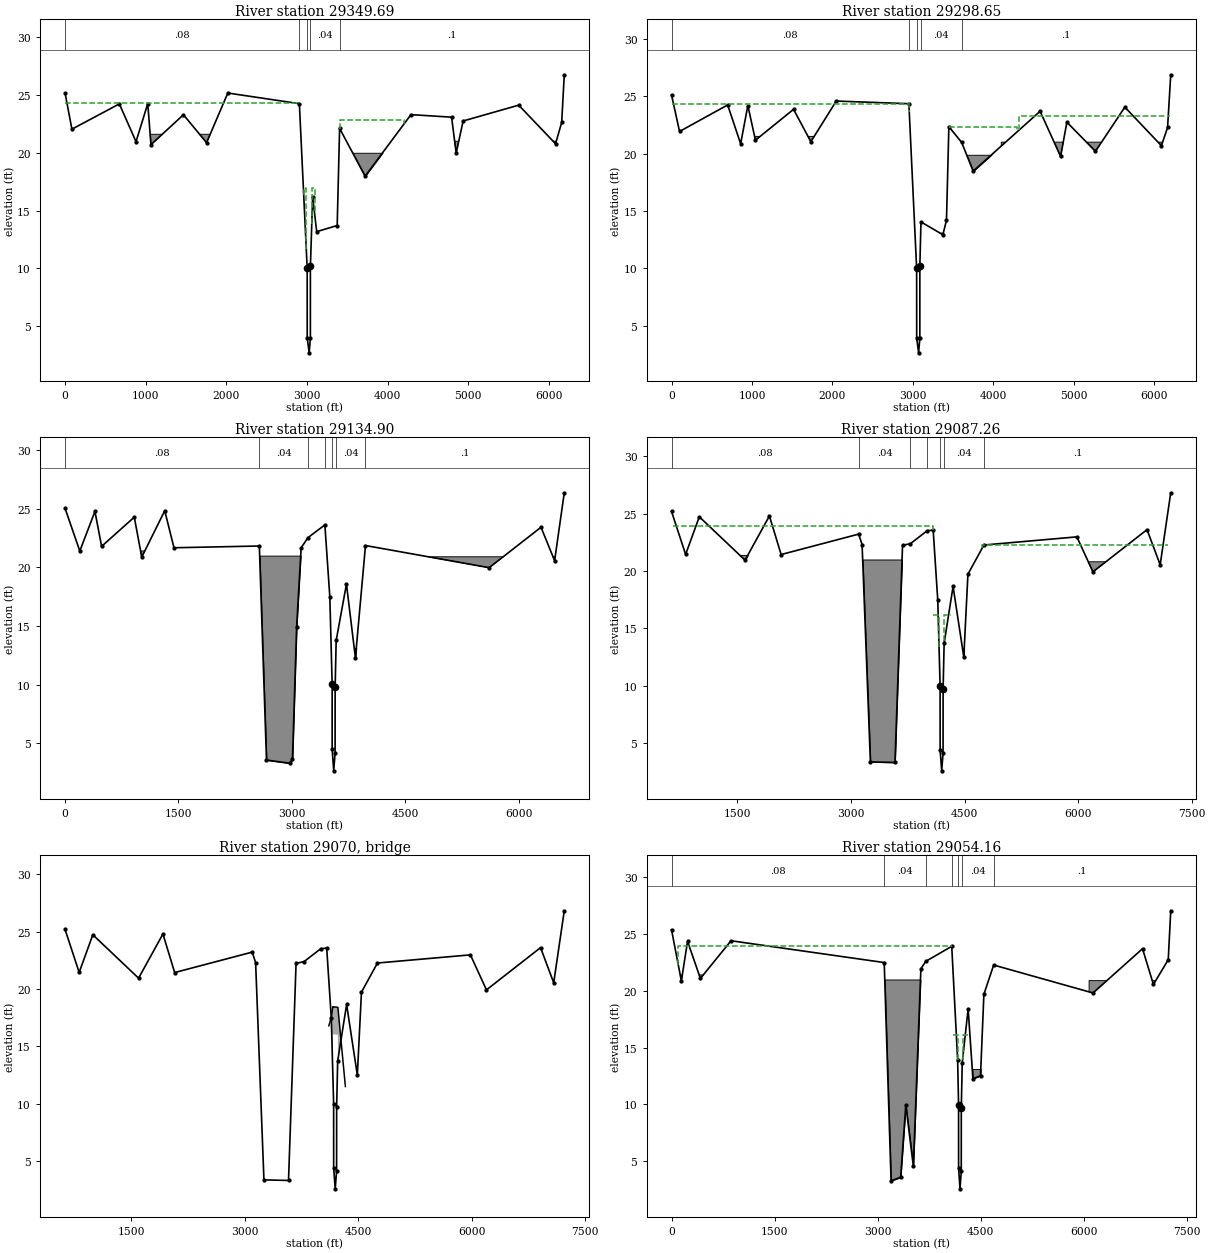
Type RM Length L Ch R = 1 ,29349.69,48.89,51.03,54.34
BEGIN DESCRIPTION:
Copy of 451s15u - xs 2/4 cart bridge
Bank Station offset =      1972
Lower channel Manning's n reflects concrete channel
LOB "n" value reflects maintained golf course
Block added in ROB since water cannot get into this area.
END DESCRIPTION:
XS GIS Cut Line= 6
     3240437.511    13848588.417     3237602.701    13847863.823
     3237409.353    13847839.111     3237030.742    13847822.563
     3235249.611    13847690.627     3234362.967    13847505.111
#Sta/Elev= 30
       0   25.17   84.82   22.04   673.3   24.23  879.93   20.96 1025.68   24.25
 1065.43    20.7 1468.07   23.29 1755.23   20.87 2018.55   25.17 2906.03   24.25
 3002.45    10.1 3002.99   10.06 3003.54    3.98 3027.57    2.68  3042.7    3.95
  3042.8   10.23 3043.47   10.25 3070.76    16.2 3120.89   13.17  3375.2    13.7
 3405.12   22.11 3721.48   17.97 4290.18    23.3 4794.13   23.08 4850.88   19.97
 4937.25   22.75 5626.48   24.12 6083.49   20.78 6159.53   22.62 6191.72   26.75
#Mann= 5 ,-1 , 0
       0     .08       0 2906.03     .04       0 3002.45    .025       0
 3043.47     .04       0 3405.12      .1       0
#XS Ineff= 5 ,-1
       0 2886.08    24.3 4290.18    6170    23.3 3410.11    4200   22.85
    3060    3096   16.93    2960    2993   16.93
Permanent Ineff=
       F       F       F       F       F
#Block Obstruct= 4 ,-1
    1000    2000    21.6    3100    3366   13.12    3500    4220      20
    4220    6185      21
Bank Sta=3002.99,3042.8
XS Rating Curve= 0
Exp/Cntr=.5,.3

Type RM Length L Ch R = 1 ,29298.65,186.59,163.76,130.49
BEGIN DESCRIPTION:
Copy of 451s15u - xs 1/4 cart bridge
Bank Station offset =      1928
Lower channel Manning's n reflects concrete channel
LOB "n" value reflects maintained golf course
Block added in ROB since water cannot get into this area.
END DESCRIPTION:
XS GIS Cut Line= 6
     3240461.895    13848578.664     3239296.869    13848249.883
     3237601.081    13847815.623     3237409.036    13847785.962
     3235261.907    13847653.286     3234378.804    13847481.355
#Sta/Elev= 30
       0   25.11    99.6   21.93   697.8   24.24  859.38   20.86  949.01   24.19
 1043.33   21.17  1517.2   23.86 1732.15   21.04 2048.39   24.58 2951.08   24.35
 3047.05   10.06 3047.59   10.02 3048.14    3.94 3072.17    2.64  3087.3    3.91
  3087.4   10.19 3101.32   14.05 3373.85   12.93 3418.53   14.19 3448.32   22.35
 3608.01   20.97 3750.34   18.47 4582.71   23.69 4837.73   19.75  4915.6   22.74
 5270.88    20.2 5636.13   24.05 6090.91   20.69 6167.66   22.28  6206.9   26.87
#Mann= 5 ,-1 , 0
       0     .08       0 2951.08     .04       0 3047.05    .025       0
 3101.32     .04       0 3608.01      .1       0
#XS Ineff= 3 ,-1
       0 2956.07   24.36 4316.19    6200   23.26 3448.32    4300   22.35
Permanent Ineff=
       F       F       F
#Block Obstruct= 4 ,-1
    1000    2000    21.5    3151    3408   13.12    3550    4100    19.9
    4100    6155      21
Bank Sta=3047.59,3087.4
XS Rating Curve= 0
Exp/Cntr=.3,.1

Type RM Length L Ch R = 1 ,29134.90,44.56,47.64,47.63
BEGIN DESCRIPTION:
451s14u - xs 4/4 cart path
Bank Station offset =      1447
Lower channel Manning's n reflects concrete channel
LOB "n" value reflects maintained golf course
Block added in LOB and ROB since water cannot get into this area.
END DESCRIPTION:
XS GIS Cut Line= 6
     3240923.835    13848341.018      3237533.82    13847621.226
     3237352.337    13847664.046     3237021.764    13847660.967
     3235392.399    13847572.415     3234414.438    13847437.802
#Sta/Elev= 30
       0   25.03   194.9   21.39  395.19   24.77   483.2   21.79   915.4   24.28
 1013.92   20.87  1318.2   24.83 1440.17   21.67 2569.13   21.82 2663.77    3.56
 2972.57    3.29 3007.44    3.62 3062.23    14.9    3122   21.66 3211.65   22.53
 3435.78   23.62 3501.22   17.48  3531.9   10.05 3532.33    4.47 3552.68    2.64
 3570.99    4.17 3571.61    9.77 3585.27   13.76 3721.21   18.57 3839.63   12.28
 3972.85   21.86 5608.79   19.97 6293.98   23.42 6473.97   20.57 6601.69   26.36
#Mann= 7 ,-1 , 0
       0     .08       0 2569.13     .04       0 3211.65     .08       0
 3435.78     .04       0  3531.9    .025       0 3585.27     .04       0
 3972.85      .1       0
#XS Ineff= 2 , 0
       0 3435.78   23.62 3972.85       0   21.86
Permanent Ineff=
       F       F
#Block Obstruct= 4 ,-1
      50    1200    21.4    2570    3210      21    3788    3880   13.12
    4100    6540    20.9
Bank Sta=3531.9,3571.61
XS Rating Curve= 0
Exp/Cntr=.5,.3

Type RM Length L Ch R = 1 ,29087.26,32.1,33.09,38.78
BEGIN DESCRIPTION:
Copy of 451s14u - xs 3/4 cart path
Bank Station offset =      1431
Lower channel Manning's n reflects concrete channel
LOB "n" value reflects maintained golf course
Block added in LOB and ROB since water cannot get into this area.
END DESCRIPTION:
XS GIS Cut Line= 6
     3240923.835    13848311.275      3237521.12    13847575.276
     3237339.637    13847618.096     3237012.787    13847620.568
     3235408.397    13847541.447     3234422.357    13847418.005
#Sta/Elev= 30
  628.79   25.18   815.1   21.44  995.57   24.72 1599.89   20.94  1921.7   24.79
 2076.78   21.43 3101.15   23.21 3146.11    22.3 3256.01    3.37  3580.7    3.32
 3680.61   22.23 3785.51   22.38 4005.31    23.5 4085.23   23.56 4146.12   17.43
  4176.8      10 4177.23    4.42 4197.58    2.59 4215.89    4.12 4216.51    9.72
 4230.17   13.71 4348.18   18.65 4489.82    12.5  4544.3   19.72 4755.52   22.26
 5983.61   22.97 6195.65   19.92 6910.31    23.6 7084.04   20.54 7223.61   26.81
#Mann= 7 ,-1 , 0
  628.79     .08       0 3101.15     .04       0 3785.51     .08       0
 4005.31     .04       0  4176.8    .025       0 4230.17     .04       0
 4755.52      .1       0
#XS Ineff= 4 ,-1
     650 4080.24   23.92 4080.24 4162.79   16.13 4234.79    4320   16.13
 4735.33    7190    22.3
Permanent Ineff=
       F       F       F       F
#Block Obstruct= 4 ,-1
    1000    2000    21.4    3140    3787      21    4380    4619   13.12
    5040    7192    20.8
Bank Sta=4176.8,4216.51
XS Rating Curve= 0
Exp/Cntr=.5,.3

Type RM Length L Ch R = 3 ,29070   ,,,
BEGIN DESCRIPTION:
451s14: Cart Path "Conc. Bridge"
END DESCRIPTION:
Bridge Culvert--1,0,-1,-1, 0
Deck Dist Width WeirC Skew NumUp NumDn MinLoCord MaxHiCord MaxSubmerge Is_Ogee
10,12.5,2.6,0, 7, 7, , , .95, 0, 0,0,,
 4113.71 4146.43 4165.64 4165.65 4232.97 4232.98    4332
   16.79   17.54   18.45   18.45    18.4    18.4    11.5
                           16.05      16
 4113.92 4146.64 4165.85 4165.86 4233.18 4233.19    4332
   16.79   17.54   18.45   18.45    18.4    18.4    11.5
                           16.05      16
BR Coef=-1 , 0 , 0 ,, 0 ,,,.8,0,,0,
WSPro=,,,, 1 ,,,, 0 ,,,, 0 ,,,,-1 ,-1 ,-1 , 0 , 0 , 0 , 0 , 0
BC Design=,, 0 ,, 0 ,,,,,,
BC HTab HWMax=27.14

Type RM Length L Ch R = 1 ,29054.16,48.72,53.37,50.8
BEGIN DESCRIPTION:
Copy of 451s14u - xs 2/4 cart path
Bank Station offset =       802
Lower channel Manning's n reflects concrete channel
LOB "n" value reflects maintained golf course
Block added in LOB and ROB since water cannot get into this area.
END DESCRIPTION:
XS GIS Cut Line= 6
     3241570.755    13848207.173      3238700.49    13847790.873
     3237514.208    13847542.907     3237332.725    13847585.727
     3235412.229    13847496.527     3234382.763      13847330.9
#Sta/Elev= 30
       0   25.38  143.25   20.87  233.04   24.36  420.06   21.09  865.91   24.41
  3094.8   22.49 3194.54    3.27 3334.19    3.58    3409    9.94 3518.72    4.55
 3628.44   21.94 3698.26   22.59  4077.3   23.92 4163.01   13.93  4176.8    9.97
 4177.23    4.39 4197.58    2.56 4215.89    4.09 4216.51    9.69 4230.17   13.68
 4316.08   18.42 4385.35   12.26 4495.93   12.52 4545.25    19.7 4687.55   22.27
  6133.1   19.81 6853.57   23.71 7011.91   20.56 7227.75   22.74    7264   27.05
#Mann= 7 ,-1 , 0
       0     .08       0  3094.8     .04       0 3698.26     .08       0
  4077.3     .04       0 4163.01    .025       0 4230.17     .04       0
 4687.55      .1       0
#XS Ineff= 4 ,-1
     100 4072.31   23.93 4101.84    4163   16.13    4235    4316   16.13
 4687.55    7264   22.27
Permanent Ineff=
       F       F       F       F
#Block Obstruct= 4 ,-1
      30    2200    21.4    3101    3695      21    4378    4520   13.12
    6076    7264    20.9
Bank Sta=4176.8,4216.51
XS Rating Curve= 0
Exp/Cntr=.5,.3

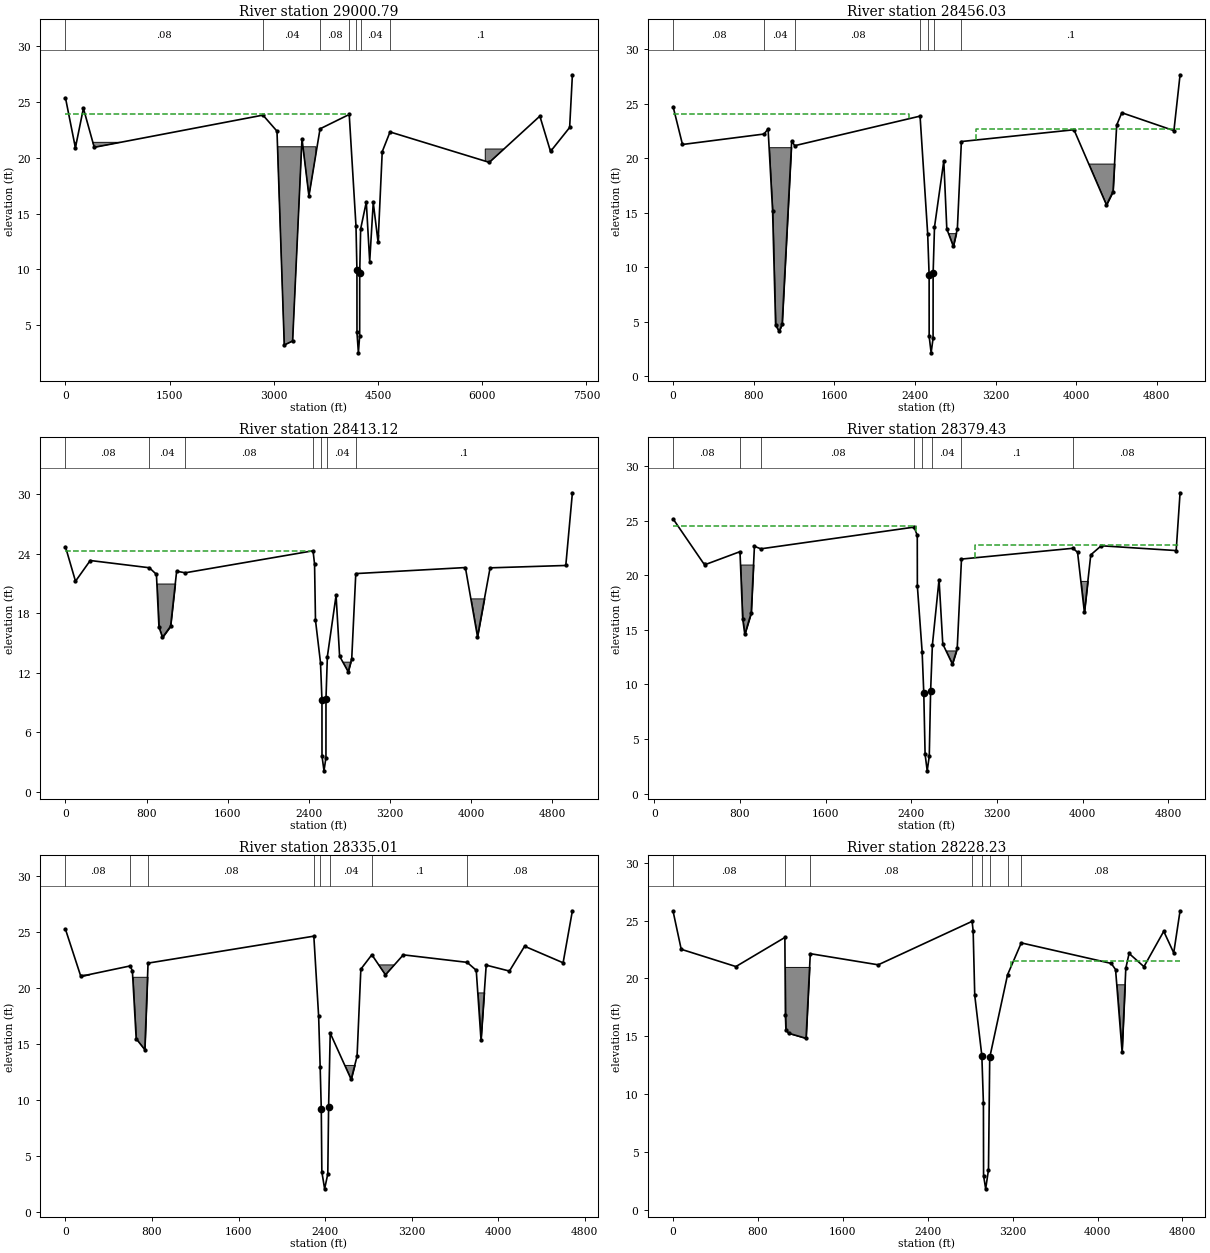
Type RM Length L Ch R = 1 ,29000.79,437.63,544.76,581.23
BEGIN DESCRIPTION:
Copy of 451s14u - xs 1/4 cart path
Bank Station offset =       782
Lower channel Manning's n reflects concrete channel
LOB "n" value reflects maintained golf course
Block added in LOB and ROB since water cannot get into this area.
END DESCRIPTION:
XS GIS Cut Line= 6
     3241570.755    13848177.429     3238715.123    13847762.197
     3237499.815    13847492.318     3237039.719    13847535.281
     3235416.195    13847460.687     3234351.089    13847295.265
#Sta/Elev= 30
       0    25.4  143.26   20.91  258.43   24.45  414.52   20.95  2843.5   23.84
 3045.65    22.4 3150.65    3.21 3270.64    3.57 3405.63   21.72 3505.62   16.58
 3665.61   22.61 4085.58    23.9    4183   13.88 4196.79    9.92 4197.22    4.34
 4217.57    2.51 4235.88    4.04  4236.5    9.64 4250.16   13.63 4331.39   16.04
 4380.38    10.7 4431.48      16 4501.14   12.44 4560.84   20.56 4673.08   22.33
 6102.62    19.6 6830.29   23.75 6983.73   20.58 7259.08   22.73 7298.77   27.46
#Mann= 7 ,-1 , 0
       0     .08       0  2843.5     .04       0 3665.61     .08       0
 4085.58     .04       0    4183    .025       0 4250.16     .04       0
 4673.08      .1       0
#XS Ineff= 2 , 0
       0 4070.58   23.94 4673.08       0   22.33
Permanent Ineff=
       F       F
#Block Obstruct= 4 ,-1
      30    2000    21.4    3050    3605      21    4452    4540   13.12
    6044    7200    20.8
Bank Sta=4196.79,4236.5
XS Rating Curve= 0
Exp/Cntr=.3,.1

Type RM Length L Ch R = 1 ,28456.03,50.4,42.91,37.29
BEGIN DESCRIPTION:
451s13u - xs 4/4 cart path REMOVED
Bank Station offset =      2439
Concrete channel - manning's n = 0.025
Near Overbank "n" value reflects maintained golf course.
END DESCRIPTION:
XS GIS Cut Line= 6
     3239832.837    13847652.576     3238505.642    13847495.427
     3237434.247    13847038.557     3237291.481    13847009.927
     3236050.714    13846809.006     3235010.424    13846372.216
#Sta/Elev= 30
       0   24.71   92.92   21.25  903.75   22.21  942.51   22.69  987.39   15.15
 1017.31    4.69 1052.22    4.12 1082.14    4.77 1176.89   21.57 1206.81   21.14
 2451.21   23.85 2526.77   13.06 2541.17    9.26  2541.4    3.67 2561.01    2.15
 2580.41    3.49 2580.79    9.44 2594.43   13.68 2686.71   19.74 2716.64   13.51
 2781.48   11.91 2821.39   13.52 2861.29   21.52 3979.01    22.6 4301.49   15.71
 4366.56   16.93 4402.95   23.03  4453.7   24.16 4970.98   22.52 5032.01   27.64
#Mann= 7 ,-1 , 0
       0     .08       0  903.75     .04       0 1206.81     .08       0
 2451.21     .04       0 2526.77    .025       0 2594.43     .04       0
 2861.29      .1       0
#XS Ineff= 2 , 0
       0 2341.24   24.01 3003.12       0   22.65
Permanent Ineff=
       F       T
#Block Obstruct= 4 ,-1
     900    1200      21    2717    2824   13.12    3000    3900    21.2
    3900    4545    19.5
Bank Sta=2541.17,2580.79
XS Rating Curve= 0
Exp/Cntr=.3,.1

Type RM Length L Ch R = 1 ,28413.12,33.69,33.69,34.91
BEGIN DESCRIPTION:
Copy of 451s13u - xs 3/4 cart path REMOVED
Bank Station offset =      2451
Concrete channel - manning's n = 0.025
Near Overbank "n" value reflects maintained golf course.
END DESCRIPTION:
XS GIS Cut Line= 6
     3239832.837      13847620.5      3238461.14    13847428.189
     3237445.475    13846991.873     3237304.041    13846976.082
     3236070.902    13846767.999     3235035.418    13846357.219
#Sta/Elev= 30
       0   24.71   99.05   21.23   244.5   23.32  827.08   22.59  896.84   21.92
  921.75   16.61  956.62   15.57 1036.34   16.69 1096.13   22.24 1180.83   22.08
 2440.74    24.3 2455.67   22.95 2464.77   17.29 2514.29   13.02 2528.69    9.22
 2528.92    3.63 2548.53    2.11 2567.93    3.45 2568.31     9.4 2581.95   13.64
 2667.72    19.8 2702.59   13.67 2787.29    12.1 2822.17   13.43 2862.03      22
 3942.51   22.61 4061.86   15.64 4186.12   22.58  4932.3   22.82  4997.4   30.15
#Mann= 7 ,-1 , 0
       0     .08       0  827.08     .04       0 1180.83     .08       0
 2440.74     .04       0 2514.29    .025       0 2581.95     .04       0
 2862.03      .1       0
#XS Ineff= 2 , 0
       0 2420.82   24.32 2862.03       0      22
Permanent Ineff=
       F       F
#Block Obstruct= 4 ,-1
     900    1082      21    2698    2821   13.12    3000    3950    21.2
    3950    4500    19.5
Bank Sta=2528.69,2568.31
XS Rating Curve= 0
Exp/Cntr=.3,.1

Type RM Length L Ch R = 1 ,28379.43,39.74,44.42,53.71
BEGIN DESCRIPTION:
Copy of 451s13u - xs 2/4 cart path REMOVED
Bank Station offset =      2627
LOB and ROB reach lengths > channel reach length
Concrete channel - manning's n = 0.025
Near Overbank "n" value reflects maintained golf course.
END DESCRIPTION:
XS GIS Cut Line= 6
     3239677.802    13847508.233     3238363.009    13847352.428
     3237448.221    13846958.231     3237305.414     13846942.44
     3236075.345    13846736.294     3235130.399    13846342.222
#Sta/Elev= 30
   175.5   25.18  469.02   20.97  800.03   22.18  825.01   16.05  844.99    14.6
  904.95   16.55  934.92   22.67  994.88   22.44 2425.87   24.43 2455.75   23.68
 2456.64   19.03 2501.29   12.99 2516.69    9.19 2528.92     3.6 2548.53    2.08
 2567.93    3.42 2580.31    9.37 2596.95   13.61 2659.23   19.62 2694.15   13.71
 2783.95   11.87 2828.85    13.3 2868.76    21.5 3909.85   22.49 3952.96   22.12
 4016.81   16.61 4076.42   21.89 4173.95   22.72 4873.97   22.28  4910.3   27.58
#Mann= 8 ,-1 , 0
   175.5     .08       0  800.03     .04       0  994.88     .08       0
 2425.87     .04       0 2501.29    .025       0 2596.95     .04       0
 2868.76      .1       0 3909.85     .08       0
#XS Ineff= 2 , 0
       0 2445.79   24.53 2994.58       0   22.82
Permanent Ineff=
       F       F
#Block Obstruct= 5 ,-1
     450     480    21.2     800     950      21    2685    2830   13.12
    2990    3900    21.2    3910    4200    19.5
Bank Sta=2516.69,2580.31
XS Rating Curve= 0
Exp/Cntr=.3,.1

Type RM Length L Ch R = 1 ,28335.01,82.88,106.78,134.66
BEGIN DESCRIPTION:
Copy of 451s13u - xs 1/4 cart path REMOVED
Bank Station offset =      2604
Concrete channel - manning's n = 0.025
Near Overbank "n" value reflects maintained golf course.
END DESCRIPTION:
XS GIS Cut Line= 6
     3239709.879    13847470.811     3238342.048    13847308.716
     3237450.546     13846919.03      3237307.78      13846890.4
     3236076.204    13846690.968     3235215.381    13846307.229
#Sta/Elev= 30
       0   25.25  141.88   21.04  598.87   21.97  618.83   21.51  653.77   15.46
  733.62   14.48  763.56   22.22 2296.03   24.63 2340.49   17.45 2354.44   12.95
 2364.84    9.15 2370.07    3.56 2395.68    2.04 2425.08    3.38 2432.46    9.33
 2447.44   15.96  2640.7   11.83  2695.6   13.89 2730.53   21.68 2832.18   22.97
 2958.29   21.17 3122.83   22.96 3712.62   22.29 3797.23   21.58 3841.27   15.36
 3889.27   22.04 4103.99   21.51 4244.15   23.73 4600.19   22.25 4686.07    26.9
#Mann= 8 ,-1 , 0
       0     .08       0  598.87     .04       0  763.56     .08       0
 2296.03     .04       0 2354.44    .025       0 2447.44     .04       0
 2832.18      .1       0 3712.62     .08       0
#XS Ineff= 2 , 0
       0 2296.03   24.63 2832.18       0   22.97
Permanent Ineff=
       F       F
#Block Obstruct= 5 ,-1
      90     320    21.2     625     795      21    2497    2692   13.12
    2760    3700   22.06    3710    4100    19.6
Bank Sta=2364.84,2432.46
XS Rating Curve= 0
Exp/Cntr=.3,.1

Type RM Length L Ch R = 1 ,28228.23,129.1,178.82,262.95
BEGIN DESCRIPTION:
451v23
Bank Station offset =      2054
LOB and ROB reach lengths > channel reach length
Concrete channel - manning's n = 0.025
Near Overbank "n" value reflects maintained golf course.
END DESCRIPTION:
XS GIS Cut Line= 6
     3240249.828     13847363.89      3238325.95    13847260.914
     3237460.827    13846831.793     3237375.644    13846773.957
     3236449.084    13846418.023     3235759.667    13846032.842
#Sta/Elev= 30
       0   25.78   76.22   22.52  591.69   21.03 1053.16   23.54 1058.15   16.85
 1063.14   15.57  1088.1   15.28 1252.81   14.84 1292.74   22.14 1932.73   21.18
 2817.67   24.93 2827.62    24.1 2842.56   18.55 2909.55   13.34 2924.31    9.23
 2925.79       3  2945.6    1.86 2972.08    3.51 2983.76   13.19 3151.68   20.32
 3280.96   23.07 4129.14    21.3 4169.67   20.77 4231.07    13.7 4266.35   20.89
 4297.19   22.16 4437.19   21.02 4623.73   24.07 4717.86   22.21 4777.59   25.84
#Mann= 8 ,-1 , 0
       0     .08       0 1053.16     .04       0 1292.74     .08       0
 2817.67     .04       0 2909.55    .025       0 2983.76     .04       0
 3151.68      .1       0 3280.96     .08       0
#XS Ineff= 2 , 0
       0 2817.67   24.93  3182.9       0   21.47
Permanent Ineff=
       F       F
#Block Obstruct= 3 ,-1
     211    1300      21    3185    4400    19.5    4400    4800   21.03
Bank Sta=2909.55,2983.76
XS Rating Curve= 0
Exp/Cntr=.3,.1

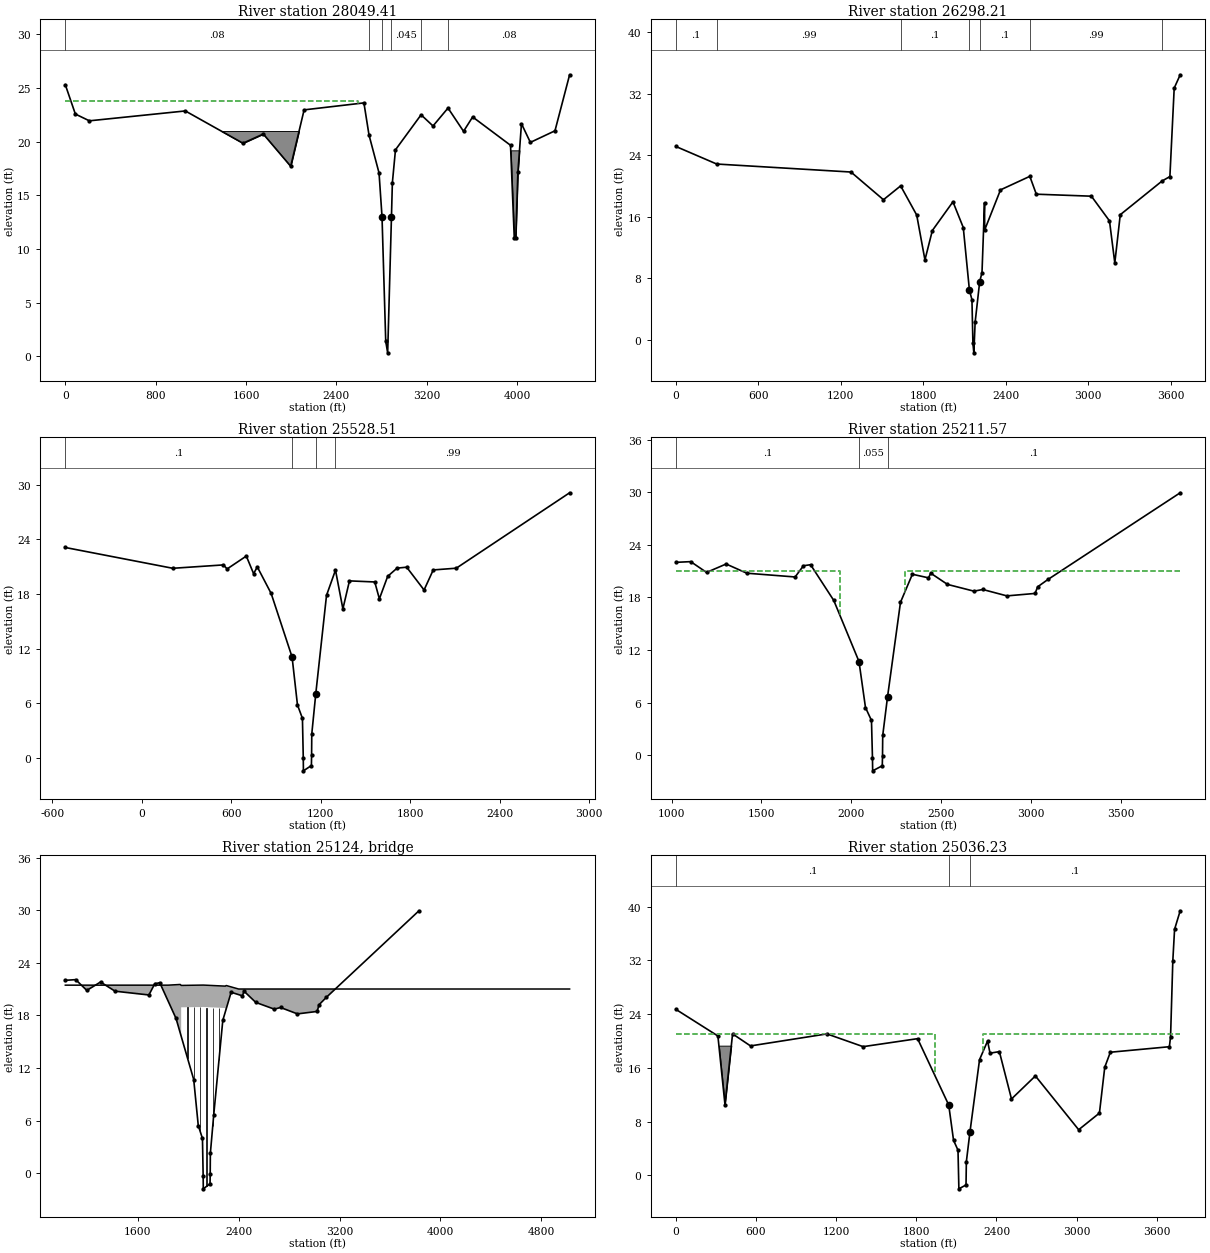
Type RM Length L Ch R = 1 ,28049.41,1704.9,1751.2,1705.9
BEGIN DESCRIPTION:
451v22
Bank Station offset =      2146
Near Overbank "n" value reflects maintained golf course.
Set manning's "n" of channel to 0.03 as this is a section at transition from grass-lined to concrete lined channel.
END DESCRIPTION:
XS GIS Cut Line= 6
     3240265.866    13847305.083     3238457.465    13847153.238
     3237574.103    13846754.125     3237537.809    13846621.049
     3236837.377    13845994.004     3236382.871    13845597.006
#Sta/Elev= 30
       0   25.31   88.93   22.58  212.93   21.95 1062.62   22.87 1572.94   19.86
 1753.03   20.72  1995.8   17.71 2114.56   22.97  2644.2   23.62 2689.16   20.63
 2778.09   17.09 2804.41   13.01 2837.31     1.4 2854.44     .33    2888   12.99
 2896.08   16.18 2923.59   19.25 3150.36   22.51 3256.01   21.47 3388.81   23.14
 3526.38   20.97 3606.87   22.31 3942.36   19.67 3975.68   11.01 3988.78   11.03
 4007.57   17.14 4039.26   21.68 4118.02   19.94 4335.96   21.02 4465.62   26.24
#Mann= 6 ,-1 , 0
       0     .08       0 2689.16     .04       0 2804.41     .03       0
    2888    .045       0 3150.36      .1       0 3388.81     .08       0
#XS Ineff= 2 , 0
       0 2594.23   23.79 3150.36       0   22.51
Permanent Ineff=
       F       F
#Block Obstruct= 2 ,-1
     246    2100      21    3900    4100    19.2
Bank Sta=2804.41,2888
XS Rating Curve= 0
Exp/Cntr=.3,.1

Type RM Length L Ch R = 1 ,26298.21,823.43,769.7,573.06
BEGIN DESCRIPTION:
451v21
Bank Station offset =      2832
Block added in ROB since water cannot get into this area.
END DESCRIPTION:
XS GIS Cut Line= 5
     3240546.167     13847357.36 3239054.506387613845904.6995442
 3238970.6412651 13845808.127585     3238626.478    13845102.999
     3238276.337    13844535.016
#Sta/Elev= 30
       0   25.14  296.86   22.86 1274.07   21.82 1510.41   18.22 1635.43   20.02
 1752.33   16.23 1812.31    10.4 1866.23   14.22 2016.13   17.95 2091.21   14.61
 2135.85    6.49 2154.34    5.22 2161.38    -.44 2168.19   -1.68 2177.45    2.27
 2210.66    7.58 2227.48    8.74 2245.99   17.83 2246.92   14.29 2362.12    19.5
  2575.5   21.26 2622.74   18.94 3023.68   18.68 3155.24   15.47 3193.95      10
 3233.61   16.27 3538.46   20.66 3594.85   21.23 3626.16   32.73 3669.84   34.46
#Mann= 7 ,-1 , 0
       0      .1       0  296.86     .99       0 1635.43      .1       0
 2135.85     .04       0 2210.66      .1       0  2575.5     .99       0
 3538.46      .1       0
#Block Obstruct= 2 , 0
       0                    2575       0   19.75
Bank Sta=2135.85,2210.66
XS Rating Curve= 0
Exp/Cntr=.3,.1

Type RM Length L Ch R = 1 ,25528.51,300.28,316.95,367.64
BEGIN DESCRIPTION:
Copy of 451s12u - xs 4/4 of Rolling brook drive
Bank Station offset =      3916
LOB and ROB extended to contain 500yr profile
END DESCRIPTION:
XS GIS Cut Line= 6
  3241190.48680413846326.8756185     3240729.058    13846105.003
 3239930.007449813845789.0673302 3239617.4192661 13845454.877524
     3238912.863    13845071.838 3238321.858384313844594.7323294
#Sta/Elev= 30
    -512    23.1  208.37   20.82  547.22   21.19  572.51   20.75  701.12   22.16
  749.95   20.23  774.73   20.97  867.61   18.06 1007.84   11.09  1043.9    5.84
 1077.27    4.36 1082.85     .02 1083.83   -1.39 1137.34    -.81  1138.7     .36
 1139.83    2.65 1166.64    7.06 1238.65   17.85 1298.76   20.62 1348.41   16.37
 1392.34   19.44 1562.03   19.32 1592.93   17.47 1648.66   19.94 1711.68   20.84
 1775.94   20.94 1892.48   18.44 1953.92   20.64 2108.45   20.83    2868    29.1
#Mann= 4 ,-1 , 0
    -512      .1       0 1007.84    .045       0 1166.64      .1       0
 1298.76     .99       0
Bank Sta=1007.84,1166.64
XS Rating Curve= 0
Exp/Cntr=.5,.3

Type RM Length L Ch R = 1 ,25211.57,186.7,175.33,175.33
BEGIN DESCRIPTION:
451s12u - xs 3/4 of Rolling brook drive
Bank Station offset =      3906
ROB extended to contain 500 yr profile
END DESCRIPTION:
XS GIS Cut Line= 5
     3241007.092    13845934.995     3240283.202    13845586.921
     3239831.747    13845419.174 3239220.915922413844926.0636107
 3238648.912244613844464.2977206
#Sta/Elev= 30
 1024.34      22 1106.71   22.08 1194.77   20.85 1303.74   21.81  1418.7   20.76
 1687.37   20.33 1733.83   21.61  1773.4   21.73 1902.49   17.65 2042.72   10.68
 2078.78    5.43 2112.15    3.95 2117.73    -.39 2118.71    -1.8 2172.22   -1.22
 2173.58    -.05 2174.71    2.24 2201.52    6.65 2273.53   17.44 2339.65   20.64
 2429.29   20.23 2441.84   20.76    2535   19.48 2682.06   18.71 2731.22    18.9
 2865.47   18.17 3022.03   18.45 3036.68   19.21 3094.21   20.05 3829.34   29.94
#Mann= 3 , 0 , 0
 1024.34      .1       0 2042.72    .055       0 2201.52      .1       0
#XS Ineff= 2 , 0
 1024.34 1938.34   21.01 2296.34 1024.34   21.01
Permanent Ineff=
       F       F
Bank Sta=2042.72,2201.52
XS Rating Curve= 0
Exp/Cntr=.5,.3

Type RM Length L Ch R = 3 ,25124   ,,,
BEGIN DESCRIPTION:
451s12: Rolling Brook Dr. "Conc. Bridge"
END DESCRIPTION:
Bridge Culvert--1,0,-1,-1, 0
Deck Dist Width WeirC Skew NumUp NumDn MinLoCord MaxHiCord MaxSubmerge Is_Ogee
50,74,2.6,0, 11, 11, , , .95, 0, 0,0,,
 1024.34 1840.01 1935.82 1943.41 1943.42 2118.34 2293.29  2293.3 2300.69 2399.03
 5024.34
   21.45   21.45   21.53   21.42   21.42   21.46   21.34   21.34   21.41   21.01
   21.01
                                   18.92   18.96   18.84
        
       0 1840.67 1936.48 1944.07 1944.08    2119 2293.95 2293.96 2301.35 2399.69
    4000
   21.45   21.45   21.53   21.42   21.42   21.46   21.34   21.34   21.41   21.01
   21.01
                                   18.92   18.96   18.84
        
Pier Skew, UpSta & Num, DnSta & Num=  ,1993.57, 4 ,1993.57, 4 , 3 , 3 , 0 ,,
    1.35    1.35       2       2
      -2   16.39   16.39   18.99
    1.35    1.35       2       2
      -2   16.39   16.39   18.99
Pier Skew, UpSta & Num, DnSta & Num=  ,2043.85, 4 ,2043.85, 4 , 3 , 3 , 0 ,,
    1.35    1.35       2       2
      -2   16.32   16.32   18.92
    1.35    1.35       2       2
      -2   16.32   16.32   18.92
Pier Skew, UpSta & Num, DnSta & Num=  ,2093.49, 4 ,2093.49, 4 , 3 , 3 , 0 ,,
    1.35    1.35       2       2
      -2   16.43   16.43   19.03
    1.35    1.35       2       2
      -2   16.43   16.43   19.03
Pier Skew, UpSta & Num, DnSta & Num=  ,2143.66, 4 ,2143.66, 4 , 3 , 3 , 0 ,,
    1.35    1.35       2       2
      -2   16.28   16.28   18.88
    1.35    1.35       2       2
      -2   16.28   16.28   18.88
Pier Skew, UpSta & Num, DnSta & Num=  ,2193.97, 4 ,2193.97, 4 , 3 , 3 , 0 ,,
    1.35    1.35       2       2
      -2   16.19   16.19   18.79
    1.35    1.35       2       2
      -2   16.19   16.19   18.79
Pier Skew, UpSta & Num, DnSta & Num=  ,2243.61, 4 ,2243.61, 4 , 3 , 3 , 0 ,,
    1.35    1.35       2       2
      -2   16.37   16.37   18.97
    1.35    1.35       2       2
      -2   16.37   16.37   18.97
BR Coef=-1 , 1 , 1 ,1.25, 0 ,,,.8,-1,2,0,
WSPro=,,,, 1 ,,,, 0 ,,,, 0 ,,,,-1 ,-1 ,-1 , 0 , 0 , 0 , 0 , 0
BC Design=,, 0 ,, 0 ,,,,,,
BC HTab HWMax=29.94

Type RM Length L Ch R = 1 ,25036.23,294.87,393.34,443.69
BEGIN DESCRIPTION:
Copy of 451s12u - xs 2/4 of Rolling brook drive
Bank Station offset =      2881
Block added in LOB since water cannot get into this area.
END DESCRIPTION:
XS GIS Cut Line= 6
     3242017.511    13846191.817     3241029.628     13845763.59
     3240395.819     13845458.83     3239944.363    13845291.084
     3239378.122    13844833.969     3239021.608    13844132.904
#Sta/Elev= 30
       0    24.7  314.47   20.74  367.35   10.53  424.37   21.05  558.56   19.26
 1130.68   21.05 1401.82   19.15 1809.61   20.34 2042.72   10.46 2078.78    5.21
 2112.15    3.73 2118.71   -2.02 2172.22   -1.44 2174.71    2.02 2201.52    6.43
 2273.53   17.22 2333.64   19.99 2351.87   18.18 2421.85   18.41 2512.69   11.36
 2691.58   14.79 3015.61    6.78 3171.08    9.26 3210.95   16.09 3252.84   18.32
 3694.89   19.14 3703.69   20.65 3720.52   31.93 3733.68   36.62 3775.82   39.38
#Mann= 3 , 0 , 0
       0      .1       0 2042.72    .055       0 2201.52      .1       0
#XS Ineff= 2 , 0
       0    1939   21.01    2299       0   21.01
Permanent Ineff=
       F       F
#Block Obstruct= 2 , 0
       0     430    19.3               0
Bank Sta=2042.72,2201.52
XS Rating Curve= 0
Exp/Cntr=.5,.3

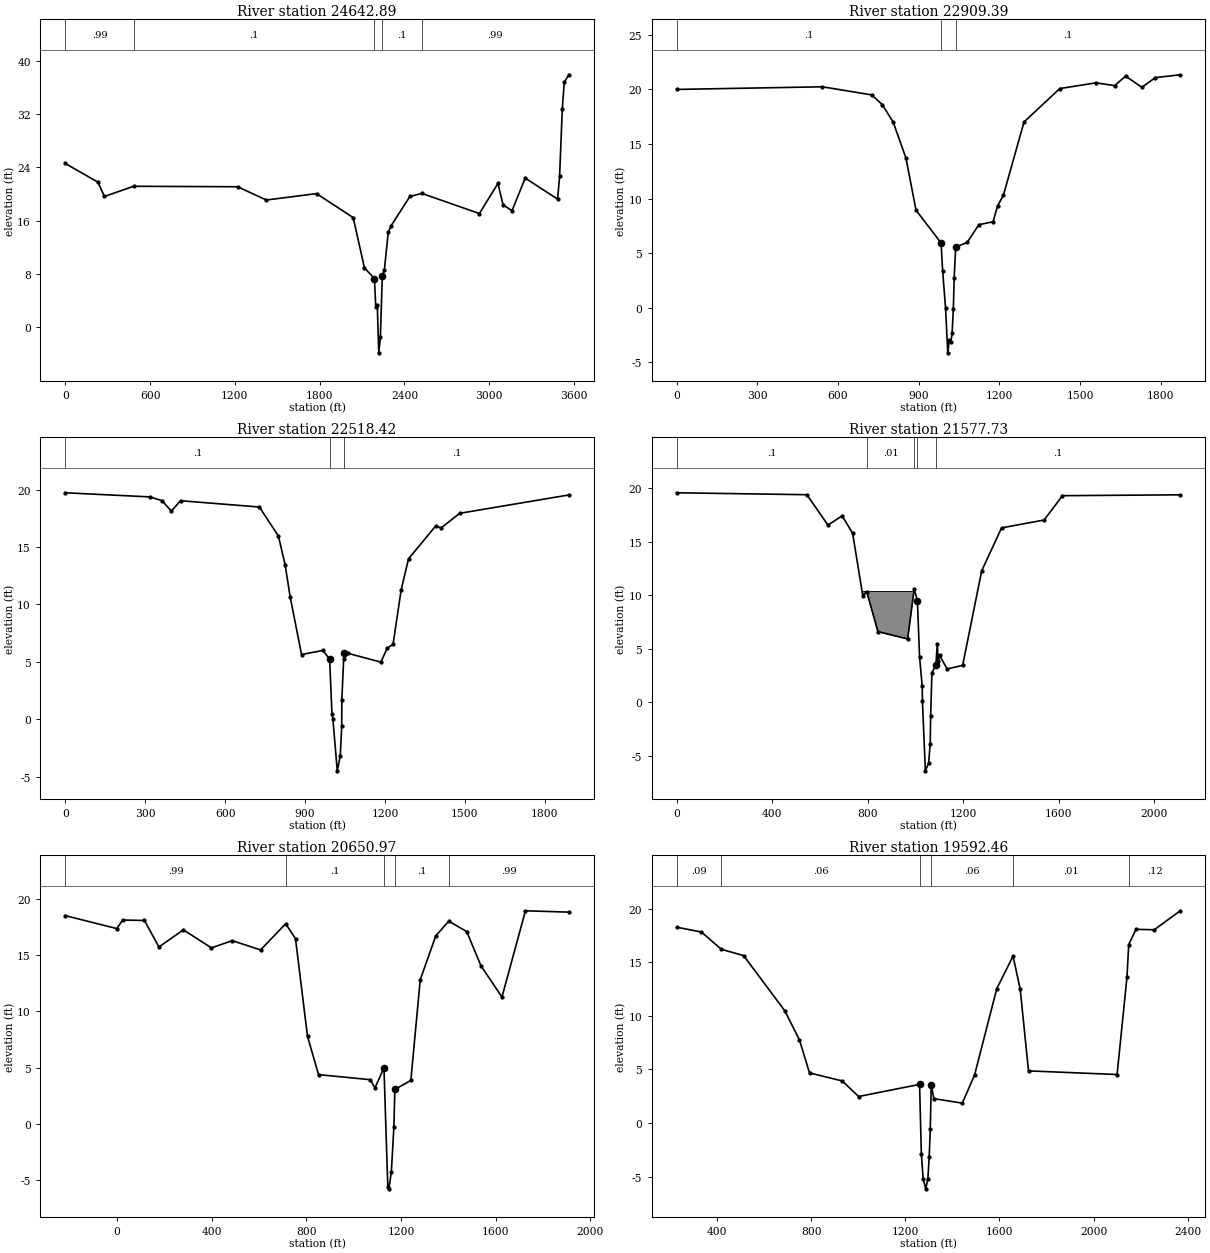
Type RM Length L Ch R = 1 ,24642.89,1368.9,1733.5,1484.26
BEGIN DESCRIPTION:
451v20 - xs 1/4 of Rolling brook drive
Bank Station offset =      2782
END DESCRIPTION:
XS GIS Cut Line= 6
     3242051.901    13846151.957     3240744.166    13845445.928
     3240200.874     13845010.55     3240141.532    13844919.251
     3239579.456    13844413.078     3239292.842    13843984.958
#Sta/Elev= 30
       0    24.6  231.04    21.8     277   19.65  483.79   21.18 1218.72   21.11
 1423.19   19.12  1777.7   20.08  2037.4   16.48 2117.02    8.93  2187.6    7.34
 2197.25       3 2207.72    3.42 2218.31   -3.81 2229.59    -1.5 2243.47     7.7
 2258.11    8.65  2285.2   14.25 2304.34   15.22 2438.59   19.65 2522.73   20.11
 2930.47   17.09 3061.46   21.61  3097.9    18.4 3161.13   17.51 3254.47   22.41
 3483.69   19.25  3497.9   22.67  3516.8   32.75 3531.03   36.79 3562.86   37.91
#Mann= 5 ,-1 , 0
       0     .99       0  483.79      .1       0  2187.6    .055       0
 2243.47      .1       0 2522.73     .99       0
Bank Sta=2187.6,2243.47
XS Rating Curve= 0
Exp/Cntr=.3,.1

Type RM Length L Ch R = 1 ,22909.39,359.38,390.97,375.03
BEGIN DESCRIPTION:
451v19
Bank Station offset =      3992
END DESCRIPTION:
XS GIS Cut Line= 4
      3241724.87    13845141.089     3241290.428    13844263.937
     3241246.138    13844186.694     3240887.462    13843466.274
#Sta/Elev= 30
       0   19.99  541.88   20.23  725.37   19.49  765.12   18.58  805.07   16.99
  852.45   13.71  890.05    8.93  983.14    5.94  989.04    3.38  999.81    -.06
 1008.14   -4.12 1013.53   -2.95 1019.92    -3.1 1024.24   -2.28 1028.81    -.07
 1031.89    2.77 1037.49    5.55 1080.32    5.99 1123.62    7.61 1176.56    7.88
 1193.15    9.32 1214.99   10.31 1291.64   17.01 1424.79   20.07 1558.87   20.59
 1629.19   20.34 1669.35   21.21 1730.06   20.18 1779.69   21.07 1872.65   21.33
#Mann= 3 , 0 , 0
       0      .1       0  983.14    .055       0 1037.49      .1       0
Bank Sta=983.14,1037.49
XS Rating Curve= 0
Exp/Cntr=.3,.1

Type RM Length L Ch R = 1 ,22518.42,955.45,940.69,858.87
BEGIN DESCRIPTION:
451v18
Bank Station offset =      3979
END DESCRIPTION:
XS GIS Cut Line= 4
     3242062.008    13845054.086     3241638.602    13844171.598
     3241647.379    13844117.242     3241213.725    13843379.271
#Sta/Elev= 30
       0   19.72  318.32   19.36  363.45   19.03  398.27   18.12  432.49   19.03
  728.44   18.48  799.83   15.96   825.3   13.43  843.91   10.67  886.84    5.63
  967.29    5.99  992.15    5.22 1000.98     .48  1004.5    -.01  1020.9    -4.5
 1032.14   -3.19 1037.66    -.57 1038.05    1.68 1045.88    5.77 1046.96    5.22
 1060.14    5.74  1184.7    4.97 1208.14    6.18 1230.25    6.52 1260.68   11.27
 1288.42   13.97 1390.63   16.84 1410.87   16.66 1480.02   17.93 1889.82   19.53
#Mann= 3 , 0 , 0
       0      .1       0  992.15    .055       0 1045.88      .1       0
Bank Sta=992.15,1045.88
XS Rating Curve= 0
Exp/Cntr=.3,.1

Type RM Length L Ch R = 1 ,21577.73,814.64,926.75,845.53
BEGIN DESCRIPTION:
451v17
Blocked at pond on near LOB.  Reduced Manning's n due to flow over water at this location.
Bank Station offset =      3959
END DESCRIPTION:
XS GIS Cut Line= 4
     3243214.802    13844727.823     3242485.276    13844033.231
     3242418.879    13843997.684     3241855.375    13843140.012
#Sta/Elev= 30
       0   19.54  544.97   19.36  633.31   16.53  692.56   17.39  736.63   15.78
   779.4    9.91   795.5   10.34  842.73     6.6   967.1    5.92  994.67   10.58
 1008.03    9.47 1016.95    4.26 1028.09    1.53 1029.03     .16 1041.29   -6.37
 1054.76   -5.67 1061.67   -3.86 1063.44   -1.25 1068.79    2.79 1085.35    3.45
 1091.15    5.45 1095.17    3.84 1100.95    4.38 1132.55    3.12 1197.55    3.46
 1277.28   12.27 1360.51   16.27 1538.61      17 1615.65   19.27 2108.84   19.35
#Mann= 5 ,-1 , 0
       0      .1       0   795.5     .01       0  994.67      .1       0
 1008.03    .055       0 1085.35      .1       0
#Block Obstruct= 2 , 0
       0  994.67   10.34               0
Bank Sta=1008.03,1085.35
XS Rating Curve= 0
Exp/Cntr=.3,.1

Type RM Length L Ch R = 1 ,20650.97,1265.84,1058.51,630.2
BEGIN DESCRIPTION:
451v16
Bank Station offset =      3851
Cross section extended on LOB to contain 500 yr profile
END DESCRIPTION:
XS GIS Cut Line= 5
 3243722.315954813844396.5191604     3243584.567    13844227.554
     3242887.041    13843371.957     3242853.085    13843310.353
     3242474.727     13842680.17
#Sta/Elev= 30
    -218   18.49       0   17.34   24.08    18.1  116.58   18.06  177.78   15.71
  280.78   17.23  399.63   15.63  487.54   16.27  607.12   15.45  713.19   17.77
  754.68   16.44   805.4    7.78     852    4.39 1070.45    3.94 1090.53    3.21
 1128.38    5.01 1144.74   -5.59 1148.83   -5.74 1159.47   -4.28 1170.46    -.22
 1174.46    3.07 1242.07    3.88 1281.56   12.79 1347.05   16.68 1401.82      18
 1477.96   17.08 1538.23   14.04 1626.98   11.27 1726.17   18.92 1909.28    18.8
#Mann= 5 ,-1 , 0
    -218     .99       0  713.19      .1       0 1128.38    .055       0
 1174.46      .1       0 1401.82     .99       0
Bank Sta=1128.38,1174.46
XS Rating Curve= 0
Exp/Cntr=.3,.1

Type RM Length L Ch R = 1 ,19592.46,477.93,855.3,686.03
BEGIN DESCRIPTION:
451v15 - xs 4/4 of state HWY 146 (North service rd)
Bank Station offset =      3713
LOB 2 points deleted to contain length of cross section to 500 yr profile
EF Goose Creek in LOB, block in right overbank is pond; Manning's set to smooth value
END DESCRIPTION:
XS GIS Cut Line= 6
 3244469.509874313842749.0537824     3243778.941    13842788.428
     3243750.766    13842893.077     3243702.466    13842921.252
     3243562.991    13842856.856     3242475.274    13842563.614
#Sta/Elev= 30
  227.49   18.26  332.41   17.81     417    16.2  511.95   15.61   687.5   10.45
  749.54    7.74  792.13    4.67  931.32    3.92 1000.98    2.47 1260.21     3.6
 1267.71   -2.85 1275.56   -5.23 1286.53   -6.14 1295.56   -5.19 1301.18   -3.15
  1305.7    -.57 1309.86    3.53 1320.92    2.27 1441.89    1.85 1494.06    4.47
 1588.57   12.53 1657.72   15.56 1688.26   12.48  1723.5    4.86 2100.22    4.52
 2142.34   13.62 2149.76   16.64 2180.58   18.06 2258.54   18.02 2368.82   19.79
#Mann= 6 ,-1 , 0
  227.49     .09       0     417     .06       0 1260.21     .03       0
 1309.86     .06       0 1657.72     .01       0 2149.76     .12       0
#Block Obstruct= 2 , 0
       0                 1657.72       0   15.56
Bank Sta=1260.21,1309.86
XS Rating Curve= 0
Exp/Cntr=.5,.3