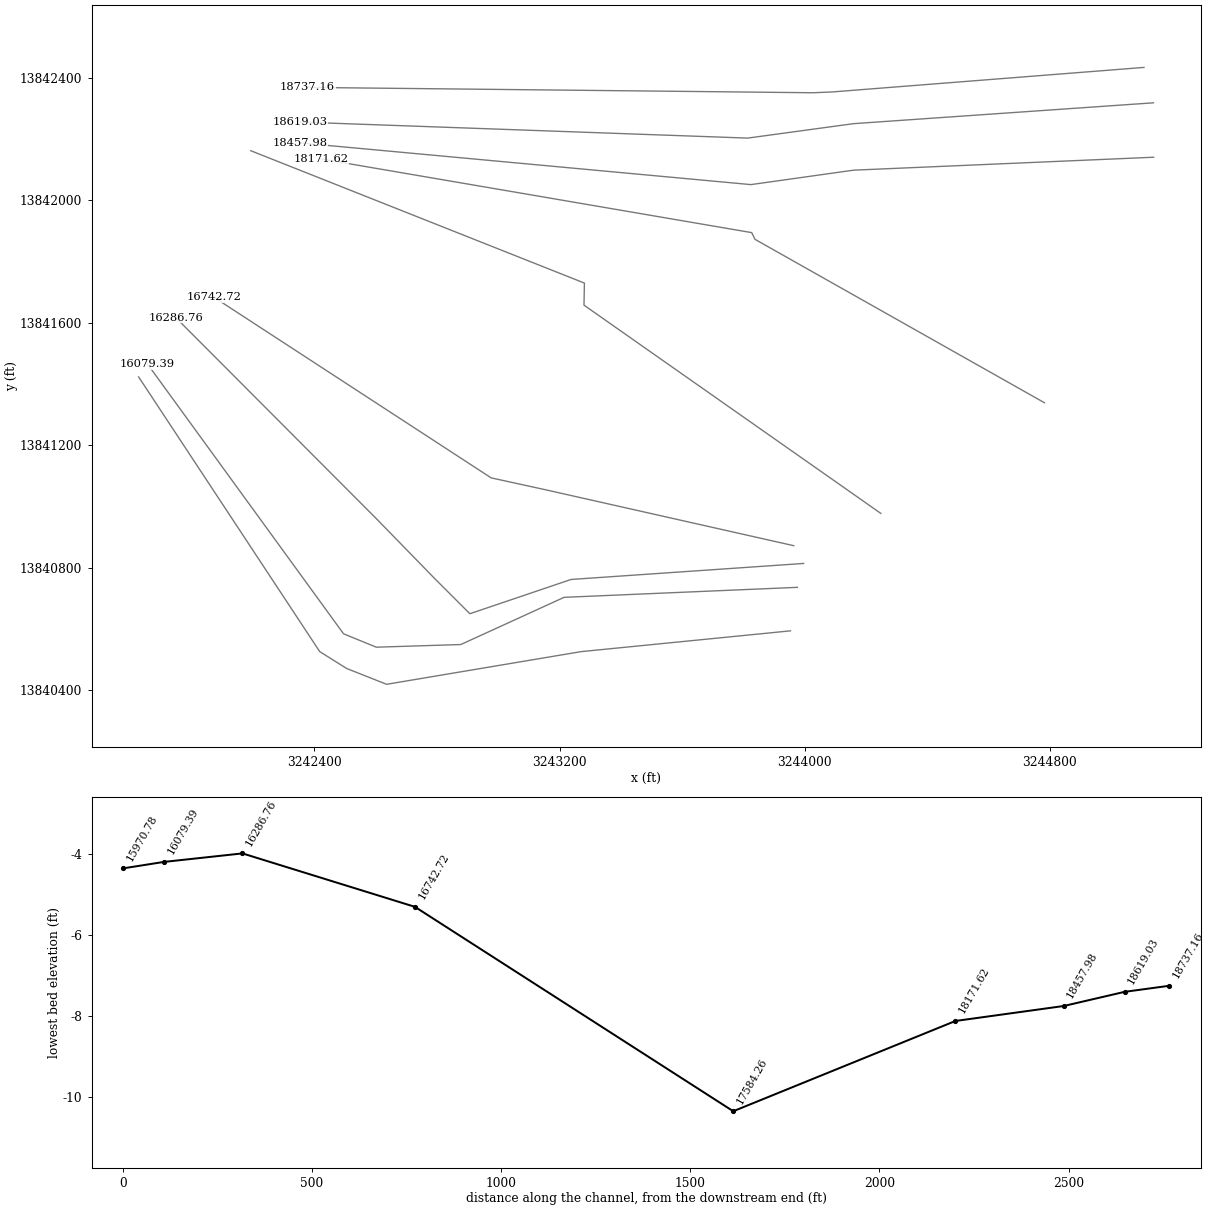
HEC-RAS study O100-00-00.prj: O100-00-00

--- O100-00-00.g01 (geometry) --- (continued)

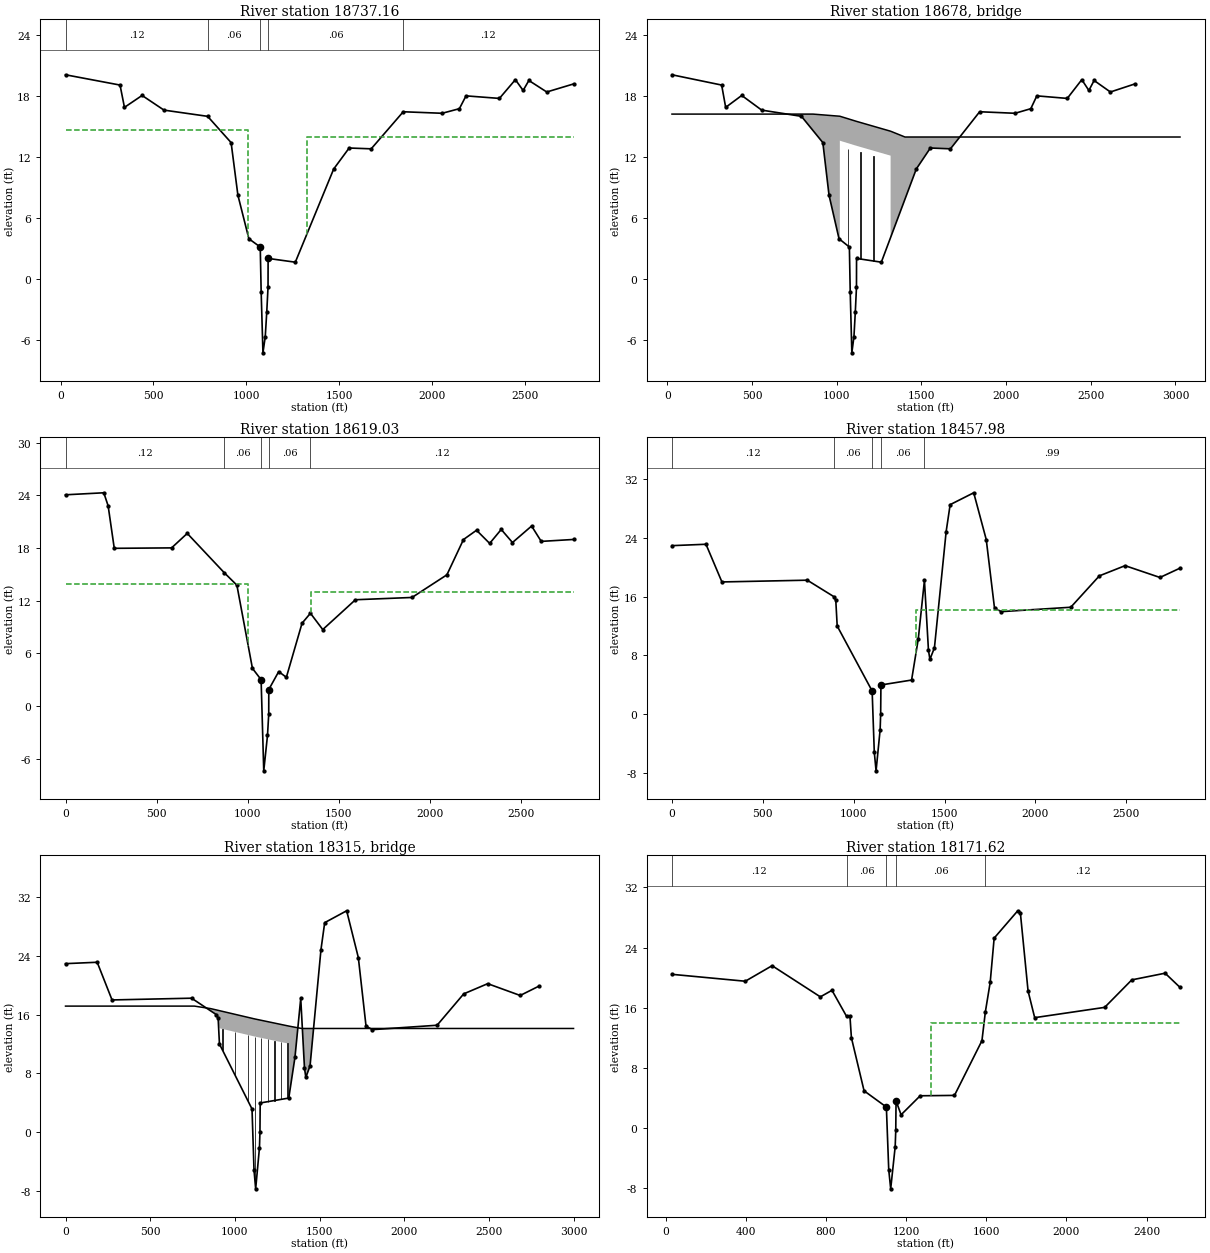
Type RM Length L Ch R = 1 ,18737.16,109.42,118.13,179.04
BEGIN DESCRIPTION:
451s11u - xs 3/4 of state HWY 146 (North service rd)
Bank Station offset =      3938
END DESCRIPTION:
XS GIS Cut Line= 4
     3245107.125    13842433.109      3244090.62    13842353.119
     3244026.437    13842350.433     3242377.395    13842367.857
#Sta/Elev= 30
   26.84   20.05  320.19   19.04  343.97   16.85  438.83   18.02  556.74   16.58
  791.41   15.97  917.73   13.39   954.2    8.23 1013.32    3.95 1074.45    3.14
 1079.33   -1.23 1088.97   -7.25  1101.4   -5.66 1109.53   -3.22 1116.36    -.79
 1116.75    2.02 1263.11    1.65 1469.55    10.8 1552.68   12.86 1671.31   12.78
 1843.74   16.42 2052.86   16.27 2145.62   16.72 2181.42   17.98 2361.09   17.73
 2446.93   19.57 2488.62   18.51 2519.51   19.49 2615.78   18.36 2759.86   19.15
#Mann= 5 ,-1 , 0
   26.84     .12       0  791.41     .06       0 1074.45     .03       0
 1116.75     .06       0 1843.74     .12       0
#XS Ineff= 2 , 0
       0 1010.84    14.6 1323.84       0   13.94
Permanent Ineff=
       F       F
Bank Sta=1074.45,1116.75
XS Rating Curve= 0
Exp/Cntr=.5,.3

Type RM Length L Ch R = 3 ,18678   ,,,
BEGIN DESCRIPTION:
451s11: North Service Rd. (State Highway 146) "Conc.
Bridge"
NOTE:  State Highway 146 would be the next downstream bridge, however, due to its large size it will not be included unless the water surface elevations are greater than 29.0'
END DESCRIPTION:
Bridge Culvert--1,0,-1,-1, 0
Deck Dist Width WeirC Skew NumUp NumDn MinLoCord MaxHiCord MaxSubmerge Is_Ogee
38,41,2.6,0, 9, 9, , , .95, 0, 0,0,,
   26.84  859.87 1018.07 1018.08 1115.84 1317.77 1317.78 1402.86 3026.84
   16.19   16.19   15.98   15.98   15.48   14.51   14.51   13.94   13.94
                           13.58   13.08   12.11
       0  867.03 1025.23 1025.24    1123 1324.93 1324.94 1410.02    3000
   16.19   16.19   15.98   15.98   15.48   14.51   14.51   13.94   13.94
                           13.58   13.08   12.11
Pier Skew, UpSta & Num, DnSta & Num=  ,1065.33, 4 ,1065.33, 4 , 3 , 3 , 0 ,,
     1.5     1.5     2.9     2.9
      -8   10.38   10.38   12.78
     1.5     1.5     2.9     2.9
      -8   10.38   10.38   12.78
Pier Skew, UpSta & Num, DnSta & Num=  ,1140.71, 4 ,1140.71, 4 , 3 , 3 , 0 ,,
     1.5     1.5     2.9     2.9
      -8   10.06   10.06   12.46
     1.5     1.5     2.9     2.9
      -8   10.06   10.06   12.46
Pier Skew, UpSta & Num, DnSta & Num=  ,1216.19, 4 ,1216.19, 4 , 3 , 3 , 0 ,,
     1.5     1.5     2.9     2.9
      -8    9.67    9.67   12.07
     1.5     1.5     2.9     2.9
      -8    9.67    9.67   12.07
BR Coef=-1 , 0 , 0 ,, 0 ,,,.8,-1,,0,
WSPro=,,,, 1 ,,,, 0 ,,,, 0 ,,,,-1 ,-1 ,-1 , 0 , 0 , 0 , 0 , 0
BC Design=,, 0 ,, 0 ,,,,,,
BC HTab HWMax=20.13

Type RM Length L Ch R = 1 ,18619.03,152.49,161.05,171.15
BEGIN DESCRIPTION:
Copy of 451s11u -
xs 4/4 of state HWY 146 (south service rd)
xs 2/4 of state HWY 146 (North service rd)
Bank Station offset =      3911
END DESCRIPTION:
XS GIS Cut Line= 4
     3245138.027    13842317.614      3244159.34    13842249.577
     3243813.921    13842202.474     3242353.742     13842254.81
#Sta/Elev= 30
       0   24.06  210.38   24.29  234.19    22.8  267.85   17.96  582.77   18.01
  668.73   19.66  871.14    15.2  941.44   13.76 1026.82    4.28 1074.45    2.99
 1088.97    -7.4 1109.53   -3.37 1116.36    -.94 1116.75    1.87 1171.13    3.91
  1213.2    3.26 1299.32    9.42 1345.45   10.56 1413.12     8.7 1592.71    12.1
 1903.58   12.36 2095.09   14.94  2186.1   18.96 2257.85   20.02 2329.97   18.52
 2393.52   20.11 2455.32   18.62 2560.39    20.5 2613.24   18.75 2790.78   18.97
#Mann= 5 ,-1 , 0
       0     .12       0  871.14     .06       0 1074.45     .03       0
 1116.75     .06       0 1345.45     .12       0
#XS Ineff= 2 , 0
       0 1004.25   13.94 1345.91       0      13
Permanent Ineff=
       F       F
Bank Sta=1074.45,1116.75
XS Rating Curve= 0
Exp/Cntr=.5,.3

Type RM Length L Ch R = 1 ,18457.98,386.76,286.36,358.29
BEGIN DESCRIPTION:
Copy of 451s9d -
xs 3/4 of state HWY 146 (south service rd)
xs 1/4 of state HWY 146 (North service rd)
Bank Station offset =      3877
station adjustments needed on left overbank to make piers visible
LOB and ROB rech lengths >channel reach length due to shape of d/s cross section cut line
Block ROB in area beyond the road embankment/roadway.
END DESCRIPTION:
XS GIS Cut Line= 4
     3245138.527    13842140.027      3244159.34    13842097.802
     3243824.389    13842050.699     3242353.742    13842186.773
#Sta/Elev= 30
       0   22.96   187.1   23.15   274.8   18.01  744.48   18.25  890.37   16.01
  901.38   15.48  909.05      12 1101.34    3.14 1113.19   -5.21 1122.93   -7.75
 1145.34   -2.13 1148.21     .02 1149.67    3.96 1318.34    4.63 1355.13   10.22
 1389.05   18.22  1411.2     8.7 1419.18    7.45 1444.11    9.03 1508.53   24.88
 1530.51   28.55  1660.2   30.17 1729.15   23.79 1774.61   14.44 1811.88   13.96
 2194.23   14.56 2351.49   18.84 2493.08   20.23 2684.92   18.62 2795.27   19.89
#Mann= 5 ,-1 , 0
       0     .12       0  890.37     .06       0 1101.34     .03       0
 1149.67     .06       0 1389.05     .99       0
#XS Ineff= 2 , 0
       0  857.19   14.12 1342.02       0   14.12
Permanent Ineff=
       F       F
#Block Obstruct= 2 , 0
       0                    1675       0      30
Bank Sta=1101.34,1149.67
XS Rating Curve= 0
Exp/Cntr=.5,.3

Type RM Length L Ch R = 3 ,18315   ,,,
BEGIN DESCRIPTION:
451s9: South Service Rd. (State Highway 146) "
NOTE:  State Highway 146 would be the next upstream bridge, however, due to its large size it will not be included unless the water surface elevations are greater than 29.0'
END DESCRIPTION:
Bridge Culvert--1,0,-1,-1, 0
Deck Dist Width WeirC Skew NumUp NumDn MinLoCord MaxHiCord MaxSubmerge Is_Ogee
124,37.8,2.6,0, 9, 9, , , .95, 0, 0,0,,
       0  760.97  857.18  857.19 1117.53 1320.11 1320.12 1393.88    3000
   17.17   17.17   16.83   16.83   15.42   14.44   14.44   14.12   14.12
                           14.43   13.02   12.04
   31.75  760.72  856.93  856.94 1117.28 1319.86 1319.87 1393.63 3031.75
   17.17   17.17   16.83   16.83   15.42   14.44   14.44   14.12   14.12
                           14.43   13.02   12.04
Pier Skew, UpSta & Num, DnSta & Num=  ,927.13, 4 ,927.13, 4 , 3 , 3 , 0 ,,
     1.5     1.5     2.9     2.9
       0      12      12    14.5
     1.5     1.5     2.9     2.9
       0      12      12    14.5
Pier Skew, UpSta & Num, DnSta & Num=  ,1002.46, 4 ,1002.46, 4 , 3 , 3 , 0 ,,
     1.5     1.5     2.4     2.4
       0    11.6    11.6      14
     1.5     1.5     2.4     2.4
       0    11.6    11.6      14
Pier Skew, UpSta & Num, DnSta & Num=  ,1076.91, 4 ,1076.91, 4 , 3 , 3 , 0 ,,
     1.5     1.5     2.4     2.4
       0    11.1    11.1    13.5
     1.5     1.5     2.4     2.4
       0    11.1    11.1    13.5
Pier Skew, UpSta & Num, DnSta & Num=  ,1117.53, 4 ,1117.53, 4 , 3 , 3 , 0 ,,
     1.5     1.5     2.4     2.4
       0    10.6    10.6    13.2
     1.5     1.5     2.4     2.4
       0    10.6    10.6    13.2
Pier Skew, UpSta & Num, DnSta & Num=  ,1155.81, 4 ,1155.81, 4 , 3 , 3 , 0 ,,
     1.5     1.5     2.4     2.4
       0    10.6    10.6    13.2
     1.5     1.5     2.4     2.4
       0    10.6    10.6    13.2
Pier Skew, UpSta & Num, DnSta & Num=  ,1194.88, 4 ,1194.88, 4 , 3 , 3 , 0 ,,
     1.5     1.5     2.4     2.4
       0    10.6    10.6    13.2
     1.5     1.5     2.4     2.4
       0    10.6    10.6    13.2
Pier Skew, UpSta & Num, DnSta & Num=  ,1233.9, 4 ,1233.9, 4 , 3 , 3 , 0 ,,
     1.5     1.5     2.4     2.4
       0    10.1    10.1    12.8
     1.5     1.5     2.4     2.4
       0    10.1    10.1    12.8
Pier Skew, UpSta & Num, DnSta & Num=  ,1273.19, 4 ,1273.19, 4 , 3 , 3 , 0 ,,
     1.5     1.5     2.4     2.4
       0    10.1    10.1    12.8
     1.5     1.5     2.4     2.4
       0    10.1    10.1    12.8
Pier Skew, UpSta & Num, DnSta & Num=  ,1311.48, 4 ,1311.48, 4 , 3 , 3 , 0 ,,
     1.5     1.5     2.4     2.4
       0     9.8     9.8    12.4
     1.5     1.5     2.4     2.4
       0     9.8     9.8    12.4
BR Coef=-1 , 1 , 1 ,1.25, 0 ,,,.8,-1,2,0,
WSPro=,,,, 1 ,,,, 0 ,,,, 0 ,,,,-1 ,-1 ,-1 , 0 , 0 , 0 , 0 , 0
BC Design=,, 0 ,, 0 ,,,,,,
BC HTab HWMax=30.17

Type RM Length L Ch R = 1 ,18171.62,569.29,587.36,365.69
BEGIN DESCRIPTION:
451s9d  - xs 2/4 of state HWY 146 (south service rd)
Bank Station offset =      3909
station/elevation adjustment made in left overbank to make piers visible
END DESCRIPTION:
XS GIS Cut Line= 4
     3244782.141    13841338.927     3243837.688    13841872.136
     3243826.994    13841894.042     3242421.779    13842134.437
#Sta/Elev= 30
   31.75   20.44  397.51   19.52  531.31   21.59  771.99   17.44  829.98   18.31
  902.88   14.84  919.62   14.88  926.92      12  990.13    4.93 1101.34    2.77
 1113.19   -5.58 1122.93   -8.12 1145.34    -2.5 1148.21    -.35 1149.67    3.59
 1174.76    1.74 1270.12    4.27 1441.13    4.32 1578.15    11.6 1595.22   15.44
 1619.29   19.36 1639.08   25.26  1756.8    28.9  1769.8   28.64 1808.27   18.22
 1841.29   14.67 2190.46   16.04 2325.68    19.7 2491.91   20.59 2566.33    18.7
#Mann= 5 ,-1 , 0
   31.75     .12       0  902.88     .06       0 1101.34     .03       0
 1149.67     .06       0 1595.22     .12       0
#XS Ineff= 2 , 0
       0  856.94    13.9 1321.75       0    13.9
Permanent Ineff=
       F       F
Bank Sta=1101.34,1149.67
XS Rating Curve= 0
Exp/Cntr=.5,.3

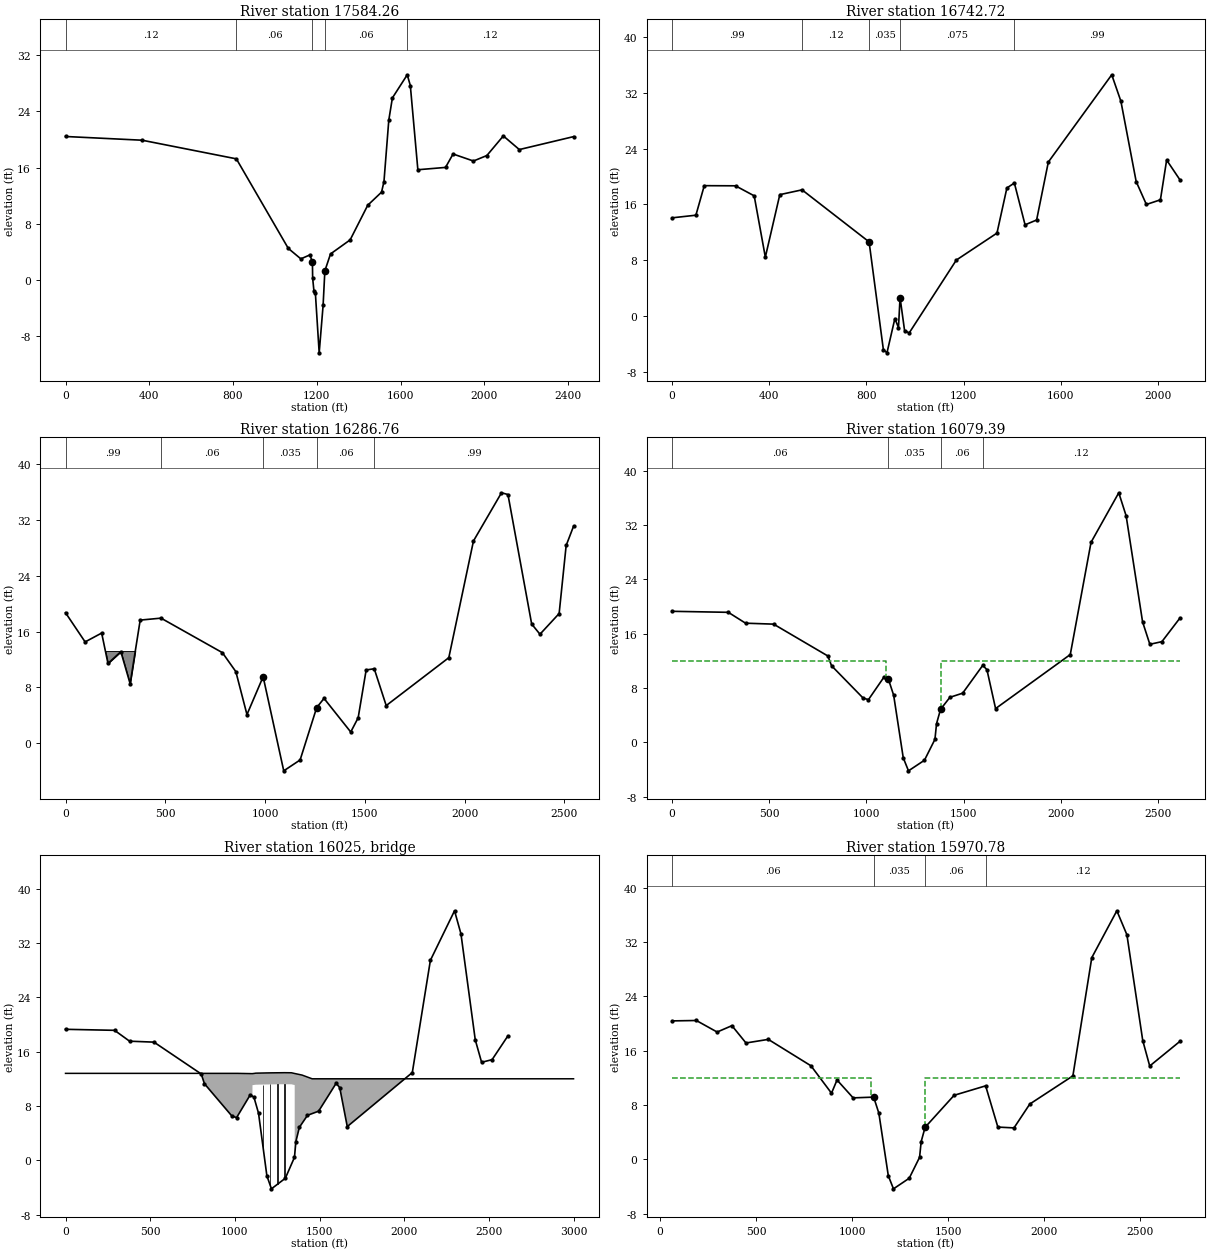
Type RM Length L Ch R = 1 ,17584.26,551.24,841.54,708.29
BEGIN DESCRIPTION:
451v14  - xs 1/4 of state HWY 146 (south service rd)
Bank Station offset =      3770
END DESCRIPTION:
XS GIS Cut Line= 4
     3244248.312    13840977.808     3243279.705    13841657.344
     3243281.053    13841729.394     3242192.513    13842161.224
#Sta/Elev= 30
       0   20.43  365.97    19.9  815.97   17.25 1063.97    4.51 1123.98    3.02
 1166.88    3.58  1179.2     2.6 1180.32     .29 1186.35   -1.51 1193.31   -1.84
 1211.51  -10.35 1230.22   -3.61 1238.63    1.31 1265.64    3.72 1359.38    5.72
 1443.47   10.65 1509.35   12.51  1520.9   14.01 1544.01   22.77 1561.18   25.92
 1632.14   29.21 1646.79   27.68 1682.78    15.7 1814.92   16.03 1850.89   17.94
 1948.18   16.94 2012.31   17.72 2090.98   20.51 2167.35   18.57 2426.33   20.41
#Mann= 5 ,-1 , 0
       0     .12       0  815.97     .06       0  1179.2     .03       0
 1238.63     .06       0 1632.14     .12       0
Bank Sta=1179.2,1238.63
XS Rating Curve= 0
Exp/Cntr=.3,.1

Type RM Length L Ch R = 1 ,16742.72,266.72,455.96,506.75
BEGIN DESCRIPTION:
451v13
Bank Station offset =      4115
ROB Manning's n decreased from 0.08 to 0.075 to avoid negative changes in 500yr WSEL
Block ROB in area beyond the road embankment/roadway.
END DESCRIPTION:
XS GIS Cut Line= 4
     3243964.063    13840872.469     3243156.715    13841054.379
      3242976.75    13841093.747     3242072.883    13841682.705
#Sta/Elev= 30
       0   14.08   98.44   14.46  132.88    18.7  261.47   18.68  338.35   17.24
   384.2    8.44  443.74   17.41  535.25    18.1  811.16   10.63  869.88   -4.83
  884.72    -5.3  917.17    -.39   932.1   -1.67   938.6    2.63  957.17    -2.1
  976.07   -2.45 1170.22    8.02 1337.37   11.89 1378.21   18.37 1408.98   19.08
 1453.02   13.08 1500.49   13.77 1548.74   22.09 1809.69   34.62 1847.37   30.82
 1910.24   19.29  1952.2      16 2009.97   16.67  2035.6   22.38 2090.63   19.52
#Mann= 5 ,-1 , 0
       0     .99       0  535.25     .12       0  811.16    .035       0
   938.6    .075       0 1408.98     .99       0
#Block Obstruct= 2 , 0
       0                 1809.69       0   34.62
Bank Sta=811.16,938.6
XS Rating Curve= 0
Exp/Cntr=.3,.1

Type RM Length L Ch R = 1 ,16286.76,120.7,207.36,185.36
BEGIN DESCRIPTION:
Copy of 451s8u - xs 4/4 of Park Avenue
Bank Station offset =      3906
Block added in LOB since water cannot get into this area.
Block ROB in area beyond the road embankment/roadway.
END DESCRIPTION:
XS GIS Cut Line= 6
     3243996.445    13840814.506 3243237.597096613840762.2427372
 3242907.219341413840650.4225739 3242792.857810813840764.7841046
 3242604.7966271 13840957.928023     3241947.357    13841617.024
#Sta/Elev= 30
       0    18.7   98.25   14.51  181.22   15.78  212.84   11.42  277.39   13.11
  323.86    8.51  374.29   17.64  478.64   17.92  786.24   12.97  853.64   10.25
  909.37    4.09  990.43    9.52  1093.7   -3.98 1175.78   -2.42 1258.61    5.08
 1295.56    6.41 1429.47    1.59 1466.68    3.63 1506.75   10.49 1547.28   10.66
 1607.22    5.38 1920.98   12.25 2044.54   28.99 2184.97    35.9 2217.37   35.65
  2336.2   17.08 2377.75   15.61 2473.84   18.58 2509.03   28.34 2546.08    31.1
#Mann= 5 ,-1 , 0
       0     .99       0  478.64     .06       0  990.43    .035       0
 1258.61     .06       0 1547.28     .99       0
#Block Obstruct= 2 , 0
       0     385    13.2 2184.97       0    35.9
Bank Sta=990.43,1258.61
XS Rating Curve= 0
Exp/Cntr=.5,.3

Type RM Length L Ch R = 1 ,16079.39,169.74,108.61,93.77
BEGIN DESCRIPTION:
451s8u - xs 3/4 of Park Avenue
Bank Station offset =      3784
Block ROB in area beyond the road embankment/roadway.
END DESCRIPTION:
XS GIS Cut Line= 6
     3243976.082    13840736.544     3243214.802    13840703.917
     3242877.608    13840549.882     3242602.023    13840541.233
     3242495.111    13840584.896     3241855.375    13841465.197
#Sta/Elev= 30
       0   19.31  289.63   19.16  378.37   17.56  522.58   17.42  801.42   12.73
  820.49   11.29  982.72    6.53 1010.24     6.3 1091.02    9.66 1112.75    9.31
 1139.81    6.95 1189.11   -2.27 1216.02   -4.19  1298.1   -2.63 1352.04     .45
 1360.37    2.77 1380.93    4.87 1428.96    6.64  1494.6    7.25 1597.94   11.35
  1619.4   10.71 1663.84    4.98 2047.91   12.94 2154.62   29.47  2297.2   36.77
 2335.06   33.38  2419.6   17.76 2457.03   14.45    2519   14.84  2612.1   18.33
#Mann= 4 ,-1 , 0
       0     .06       0 1112.75    .035       0 1380.93     .06       0
 1597.94     .12       0
#XS Ineff= 2 , 0
       0    1099   12.02 1380.93       0   12.02
Permanent Ineff=
       F       F
#Block Obstruct= 2 , 0
       0                  2297.2       0   36.77
Bank Sta=1112.75,1380.93
XS Rating Curve= 0
Exp/Cntr=.5,.3

Type RM Length L Ch R = 3 ,16025   ,,,
BEGIN DESCRIPTION:
451s8: Park Avenue "Conc. Bridge"
END DESCRIPTION:
Bridge Culvert--1,0,-1,-1, 0
Deck Dist Width WeirC Skew NumUp NumDn MinLoCord MaxHiCord MaxSubmerge Is_Ogee
33,42.6,2.6,0, 13, 13, , , .95, 0, 0,0,,
       0 1015.19 1104.01 1104.02 1124.11 1197.38 1291.57 1333.51 1353.31 1353.32
 1396.85 1456.51    3000
   12.82   12.82   12.78   12.78   12.85   12.89   12.92   12.91    12.8    12.8
   12.57   12.02   12.02
                           11.08   11.15   11.19   11.22   11.21    11.1
                        
   61.54 1014.73 1103.55 1103.56 1123.65 1196.92 1291.11 1333.05 1352.85 1352.86
 1396.39 1456.05 3061.54
   12.82   12.82   12.78   12.78   12.85   12.89   12.92   12.91    12.8    12.8
   12.57   12.02   12.02
                           11.08   11.15   11.19   11.22   11.21    11.1
                        
Pier Skew, UpSta & Num, DnSta & Num=  ,1167.69, 4 ,1167.69, 4 , 3 , 3 , 0 ,,
    1.35    1.35       2       2
    -4.5     8.7     8.7    11.2
    1.35    1.35       2       2
    -4.5     8.7     8.7    11.2
Pier Skew, UpSta & Num, DnSta & Num=  ,1209.3, 4 ,1209.3, 4 , 3 , 3 , 0 ,,
    1.35    1.35       2       2
    -4.5     8.7     8.7    11.2
    1.35    1.35       2       2
    -4.5     8.7     8.7    11.2
Pier Skew, UpSta & Num, DnSta & Num=  ,1251.58, 4 ,1251.58, 4 , 3 , 3 , 0 ,,
    1.35    1.35       2       2
    -4.5     8.7     8.7    11.2
    1.35    1.35       2       2
    -4.5     8.7     8.7    11.2
Pier Skew, UpSta & Num, DnSta & Num=  ,1292.6, 4 ,1292.6, 4 , 3 , 3 , 0 ,,
    1.35    1.35       2       2
    -4.5     8.7     8.7    11.2
    1.35    1.35       2       2
    -4.5     8.7     8.7    11.2
BR Coef=-1 , 0 , 0 ,, 0 ,,,.8,-1,,0,
WSPro=,,,, 1 ,,,, 0 ,,,, 0 ,,,,-1 ,-1 ,-1 , 0 , 0 , 0 , 0 , 0
BC Design=,, 0 ,, 0 ,,,,,,
BC HTab HWMax=36.77

Type RM Length L Ch R = 1 ,15970.78,205.74,177.08,51.53
BEGIN DESCRIPTION:
Copy of 451s8u - xs 2/4 of Park Aveue
Bank Station offset =      3846
Block ROB in area beyond the road embankment/roadway.
END DESCRIPTION:
XS GIS Cut Line= 6
     3243953.543    13840594.587     3243270.357    13840526.753
     3242635.624    13840420.156     3242505.106    13840471.769
     3242417.313    13840526.895     3241826.461    13841423.131
#Sta/Elev= 30
   61.54   20.37   188.5   20.43   296.9   18.73  373.99   19.67  447.27   17.12
  563.56   17.65  786.01   13.76  892.97    9.73  921.83   11.67  1005.8    9.04
 1112.75    9.15 1139.81    6.79 1189.11   -2.43 1216.02   -4.35  1298.1   -2.79
 1352.04     .29 1360.37    2.61 1380.93    4.71 1532.07    9.42 1696.32   10.81
 1760.09    4.74 1844.13    4.62 1926.43    8.13  2151.1   12.28 2249.56   29.68
  2380.2   36.58 2432.62   33.05 2515.19   17.48 2551.48   13.73 2709.42   17.37
#Mann= 4 ,-1 , 0
   61.54     .06       0 1112.75    .035       0 1380.93     .06       0
 1696.32     .12       0
#XS Ineff= 2 , 0
       0 1098.54   12.02 1380.93       0   12.02
Permanent Ineff=
       F       F
#Block Obstruct= 2 , 0
   61.54                  2380.2   61.54   36.58
Bank Sta=1112.75,1380.93
XS Rating Curve= 0
Exp/Cntr=.5,.3