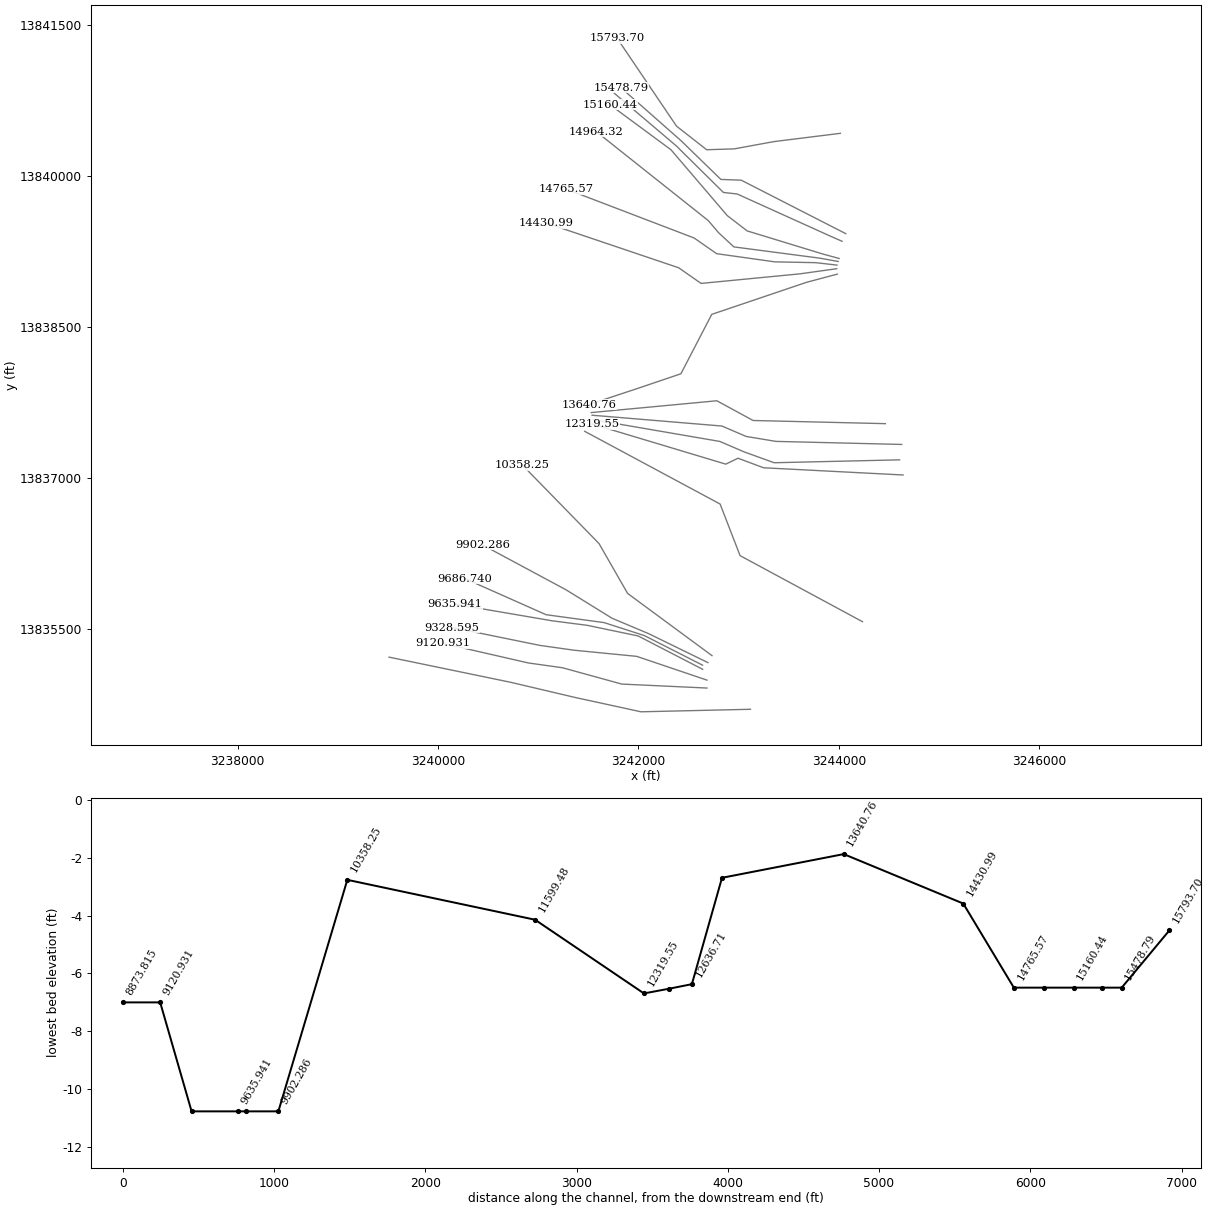
HEC-RAS study O100-00-00.prj: O100-00-00

--- O100-00-00.g01 (geometry) --- (continued)

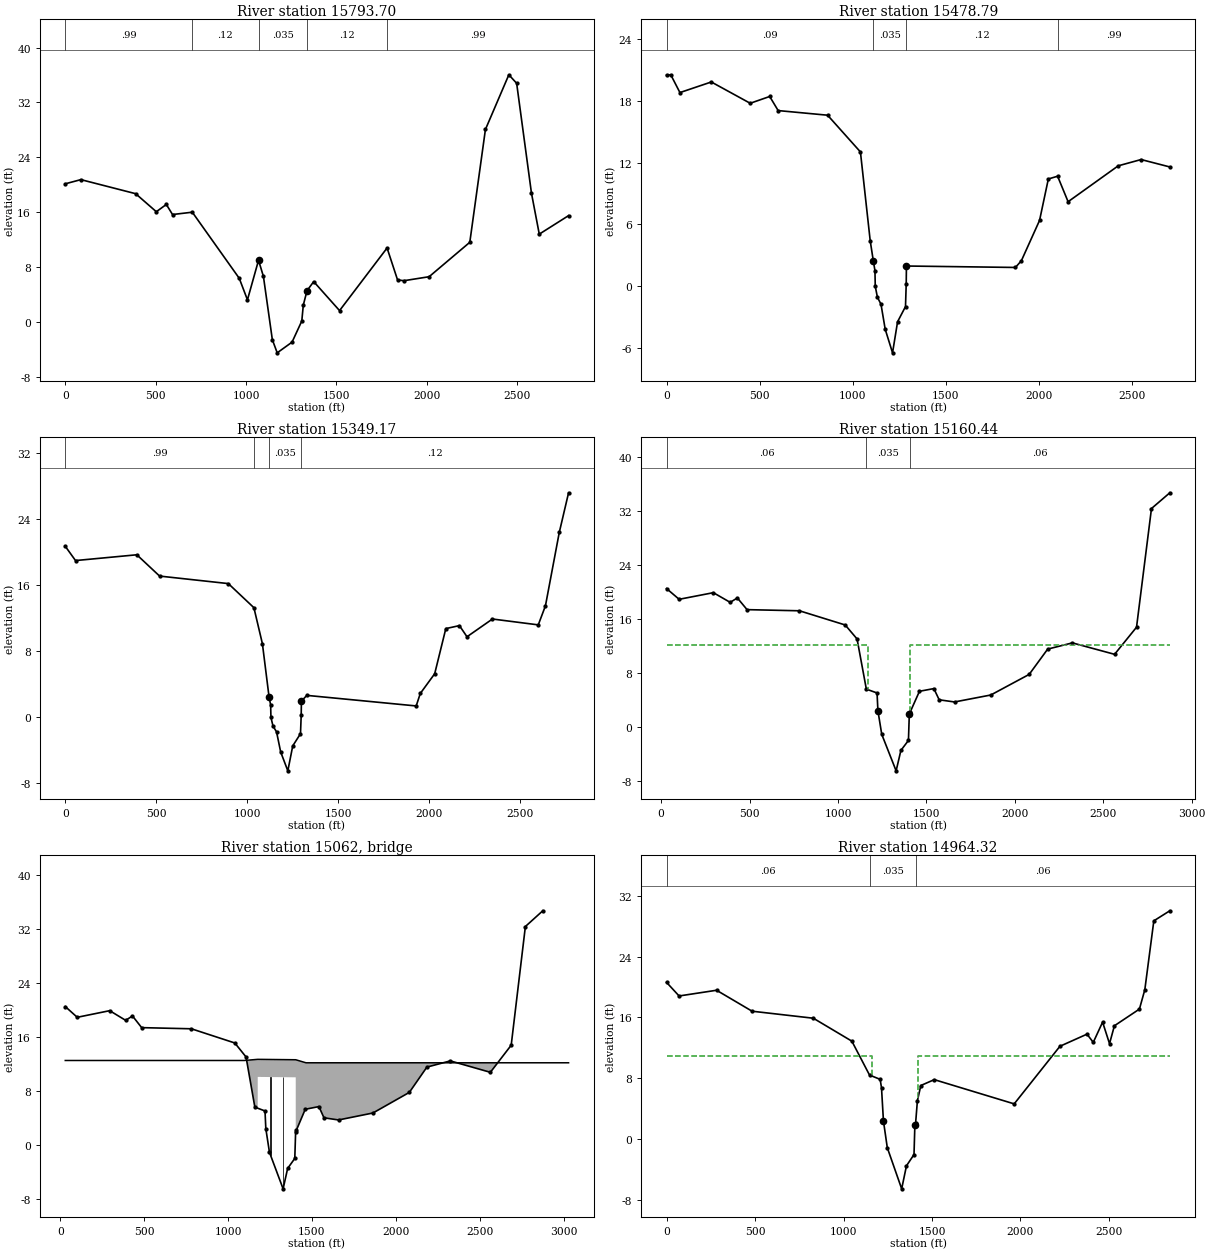
Type RM Length L Ch R = 1 ,15793.70,468.39,314.91,30.26
BEGIN DESCRIPTION:
Copy of 451s8u - xs 1.5/4 of Park Avenue
Bank Station offset =      3828
This is an intermediate section between xsec 1/4 and 2/4. Hence ineffective flow (0.99) applied based on expansion ratio
Block ROB in area beyond the road embankment/roadway.
higher c/e coefficients used to avoid negative WSELs.
END DESCRIPTION:
XS GIS Cut Line= 6
     3244016.531    13840425.002     3243352.727    13840342.632
     3242956.834    13840270.415     3242681.249    13840261.766
     3242380.562    13840496.269     3241787.699    13841369.833
#Sta/Elev= 30
       0   20.14   86.39   20.75  389.21    18.7  503.67   16.07  559.04   17.13
   593.3   15.66  702.71      16   962.4    6.36 1007.76    3.22  1069.1    8.99
 1096.16    6.63 1145.46   -2.59 1172.37   -4.51 1254.45   -2.95 1308.39     .13
 1316.72    2.45 1337.28    4.55 1374.23    5.88 1517.22    1.65  1780.1   10.78
 1838.16    6.12 1873.63    6.01 2012.61    6.59 2237.73   11.61 2324.12   28.06
 2453.71   36.04 2496.91    34.8 2578.93   18.76 2622.05    12.8 2784.11    15.5
#Mann= 5 ,-1 , 0
       0     .99       0  702.71     .12       0  1069.1    .035       0
 1337.28     .12       0  1780.1     .99       0
#Block Obstruct= 2 , 0
       0                 2453.71       0   36.04
Bank Sta=1069.1,1337.28
XS Rating Curve= 0
Exp/Cntr=.5,.3

Type RM Length L Ch R = 1 ,15478.79,102.89,129.62,29.46
BEGIN DESCRIPTION:
Copy of 451s7u -   xs 4/4 of state HWY 330
xs 1/4 of Park Avenue
Bank Station offset =      3785
This cross section is added to account for the recommended contraction ratio for 451s7 and recommended expansion ratio for 451s8
END DESCRIPTION:
XS GIS Cut Line= 5
     3244069.958    13839427.782  3243026.663605 13839959.170667
 3242823.354217213839966.7947691  3242426.90091113840350.5412386
     3241826.848    13840877.176
#Sta/Elev= 30
       0   20.49   22.82   20.54   72.02   18.81  240.75   19.84  449.79   17.77
  554.57   18.43  600.03   17.06  865.79   16.61 1042.26   13.04 1094.86     4.4
 1111.88    2.41 1120.29    1.51 1121.98    -.02 1133.61   -1.09 1152.74   -1.76
 1175.46    -4.2 1214.88   -6.49  1241.9   -3.47 1284.56   -1.99 1288.42     .25
 1289.52    1.95 1875.31    1.81 1907.27    2.46 2005.06    6.38 2052.29   10.41
 2102.09   10.68 2158.49     8.2 2427.99   11.69 2550.97    12.3  2705.3   11.58
#Mann= 4 ,-1 , 0
       0     .09       0 1111.88    .035       0 1289.52     .12       0
 2102.09     .99       0
Bank Sta=1111.88,1289.52
XS Rating Curve= 0
Exp/Cntr=.3,.1

Type RM Length L Ch R = 1 ,15349.17,216.88,188.73,123.94
BEGIN DESCRIPTION:
Copy of 451s7u - xs 3.5/4 of state HWY 330
Bank Station offset =      3776
This is an intermediate section between xsec 3/4 and 4/4. Hence ineffective flow (0.99) applied based on contraction ratio
END DESCRIPTION:
XS GIS Cut Line= 6
     3244033.549    13839351.722     3243914.309    13839403.918
 3242986.001727513839821.9368302 3242848.767890713839837.1850343
 3242378.614931413840299.7138916     3241753.897    13840827.916
#Sta/Elev= 30
       0   20.71   56.39   18.98  393.64   19.68  518.85    17.1  896.91   16.19
 1037.58   13.27 1084.34    8.91 1121.21    2.41 1129.62    1.51 1131.31    -.02
 1142.94   -1.09 1162.07   -1.76 1184.79    -4.2 1224.21   -6.49 1251.23   -3.47
 1293.89   -1.99 1297.75     .25 1298.85    1.95 1328.59    2.65 1930.29    1.37
  1952.8    2.88 2032.01    5.27 2093.23   10.74 2168.05    11.1 2209.73    9.75
 2349.65    11.9 2601.77   11.19 2641.24    13.5  2717.2   22.38 2768.43   27.19
#Mann= 4 ,-1 , 0
       0     .99       0 1037.58     .09       0 1121.21    .035       0
 1298.85     .12       0
Bank Sta=1121.21,1298.85
XS Rating Curve= 0
Exp/Cntr=.5,.3

Type RM Length L Ch R = 1 ,15160.44,196.12,196.12,445.93
BEGIN DESCRIPTION:
451s7u - xs 3/4 of state HWY 330
Bank Station offset =      3702
END DESCRIPTION:
XS GIS Cut Line= 6
      3244003.61    13839181.071     3243839.766    13839225.679
     3243085.836    13839455.051     3242887.514    13839606.741
 3242325.246217113840261.5933814     3241717.135    13840708.439
#Sta/Elev= 30
    30.2   20.48  101.62   18.89  295.07   19.87  390.12   18.44  430.78   19.09
  485.61   17.36  782.04   17.19 1040.78   15.09 1107.78   13.02 1160.22     5.6
 1220.79    5.03 1225.64    2.41 1247.37   -1.09 1328.64   -6.49 1355.66   -3.47
 1398.32   -1.99 1403.28    1.95 1407.51    2.17 1460.62    5.28 1542.04    5.68
 1572.17    4.02 1658.99     3.7 1864.08    4.73 2081.16    7.78 2185.66   11.52
 2325.32   12.44 2564.06   10.75  2688.2   14.76 2772.73   32.32  2876.5   34.65
#Mann= 3 ,-1 , 0
    30.2     .06       0 1160.22    .035       0 1407.51     .06       0
#XS Ineff= 2 , 0
    30.2  1172.2   12.16  1408.2    30.2   12.16
Permanent Ineff=
       F       F
Bank Sta=1225.64,1403.28
XS Rating Curve= 0
Exp/Cntr=.5,.3

Type RM Length L Ch R = 3 ,15062   ,,,
BEGIN DESCRIPTION:
451s7: State Highway 330
END DESCRIPTION:
Bridge Culvert--1,0,-1,-1, 0
Deck Dist Width WeirC Skew NumUp NumDn MinLoCord MaxHiCord MaxSubmerge Is_Ogee
47.76,100.6,2.6,0, 8, 8, , , .95, 0, 0,0,,
    30.2 1097.28 1177.35 1177.36  1403.9 1403.91 1464.92  3030.2
    12.5    12.5   12.67   12.67   12.61   12.61   12.16   12.16
                           10.07   10.01
       0 1098.08 1178.15 1178.16  1404.7 1404.71 1465.72    3000
    12.5    12.5   12.67   12.67   12.61   12.61   12.16   12.16
                           10.07   10.01
Pier Skew, UpSta & Num, DnSta & Num=  ,1254.25, 4 ,1254.25, 4 , 3 , 3 , 0 ,,
    1.35    1.35       2       2
      -7    8.07    8.07   10.07
    1.35    1.35       2       2
      -7    8.07    8.07   10.07
Pier Skew, UpSta & Num, DnSta & Num=  ,1329, 4 ,1329, 4 , 3 , 3 , 0 ,,
    1.35    1.35       2       2
      -7    8.01    8.01   10.01
    1.35    1.35       2       2
      -7    8.01    8.01   10.01
BR Coef=-1 , 0 , 0 ,, 0 ,,,.8,-1,,0,
WSPro=,,,, 1 ,,,, 0 ,,,, 0 ,,,,-1 ,-1 ,-1 , 0 , 0 , 0 , 0 , 0
BC Design=,, 0 ,, 0 ,,,,,,
BC HTab HWMax=35.07

Type RM Length L Ch R = 1 ,14964.32,140.14,198.75,351.59
BEGIN DESCRIPTION:
Copy of 451s7u - xs 2/4 of state HWY 330
Bank Station offset =      3671
END DESCRIPTION:
XS GIS Cut Line= 6
     3243994.628    13839151.132     3243811.986    13839183.949
     3242952.894    13839296.132     3242800.299    13839437.156
     3242697.866    13839557.198     3241579.277    13840441.914
#Sta/Elev= 30
       0   20.61   70.91   18.82   282.7   19.57  483.43   16.82  829.46    15.9
 1047.15   12.89    1147    8.44 1207.06    7.88  1214.7    6.76 1225.64    2.41
 1247.37   -1.09 1328.64   -6.49 1355.66   -3.47 1398.32   -1.99 1403.28    1.95
 1407.51    2.17 1417.54    5.09 1436.93    7.07 1512.85    7.84 1964.35    4.66
 2222.91   12.22 2375.73   13.81 2411.15   12.73 2463.89   15.39 2502.99   12.56
 2530.56   14.91 2671.96    17.1 2702.43   19.64 2753.32   28.68 2843.71      30
#Mann= 3 ,-1 , 0
       0     .06       0    1147    .035       0 1407.51     .06       0
#XS Ineff= 2 , 0
       0  1161.6      11 1421.27       0      11
Permanent Ineff=
       F       F
Bank Sta=1225.64,1403.28
XS Rating Curve= 0
Exp/Cntr=.5,.3

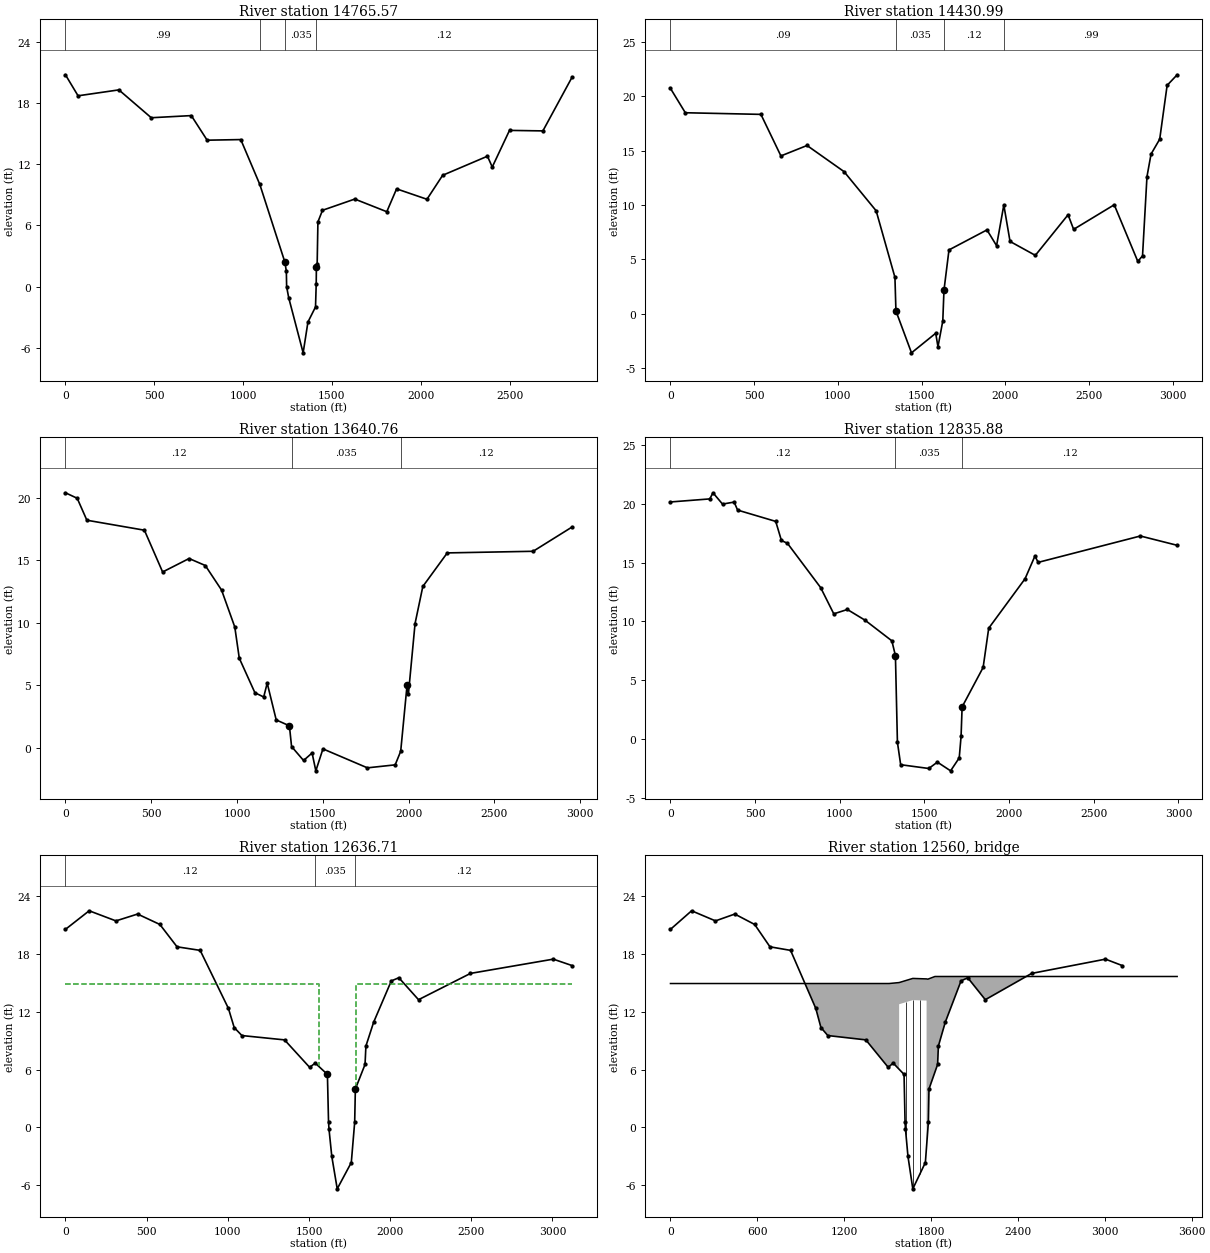
Type RM Length L Ch R = 1 ,14765.57,283.98,334.58,349.88
BEGIN DESCRIPTION:
Copy of 451s7u - xs 1.5/4 of state HWY 330
Bank Station offset =      3662
This is an intermediate section between xsec 1/4 and 2/4. Hence ineffective flow (0.99) applied based on expansion ratio
higher c/e coefficients used to avoid negative WSELs.
END DESCRIPTION:
XS GIS Cut Line= 6
     3243982.653    13839115.205     3243770.032    13839139.332
     3243361.838    13839147.336     3242780.979    13839228.647
       3242556.4    13839384.425      3241275.99    13839872.101
#Sta/Elev= 30
       0   20.76   71.03    18.7  300.73   19.28  483.06   16.55   708.5   16.76
  797.64   14.35  986.95   14.41 1094.16   10.01 1235.02    2.41 1243.43    1.51
 1245.12    -.02 1256.75   -1.09 1338.02   -6.49 1365.04   -3.47  1407.7   -1.99
 1411.56     .25 1412.66    1.95 1416.89    2.17 1421.16    6.34 1446.93    7.48
 1628.63    8.58 1808.85    7.34    1864    9.58 2034.92    8.56 2123.33   10.91
 2375.46   12.78 2402.53   11.72 2499.61   15.31 2687.49   15.26 2852.24   20.54
#Mann= 4 ,-1 , 0
       0     .99       0 1094.16     .09       0 1235.02    .035       0
 1412.66     .12       0
Bank Sta=1235.02,1412.66
XS Rating Curve= 0
Exp/Cntr=.5,.3

Type RM Length L Ch R = 1 ,14430.99,365.65,790.23,1399.55
BEGIN DESCRIPTION:
451v12 - xs 1/4 of state HWY 330
Bank Station offset =      3560
END DESCRIPTION:
XS GIS Cut Line= 5
     3243979.659    13839079.279     3243609.237    13839027.902
     3242625.929    13838933.084     3242401.351    13839088.863
     3241082.989    13839532.051
#Sta/Elev= 30
       0   20.73   88.84   18.49  540.24   18.34  659.66   14.52  815.76   15.48
 1036.59   13.08 1228.38    9.48 1340.63    3.36 1346.58     .27 1439.52   -3.58
 1584.11   -1.78 1597.65   -3.02 1626.41    -.65 1633.42    2.17 1663.41    5.88
 1890.23    7.72 1947.59    6.27 1990.84   10.01    2028    6.66 2179.13    5.38
 2374.55    9.11  2407.8    7.77 2650.27   10.03  2791.1    4.82 2819.24    5.34
 2845.78   12.62 2870.11   14.69 2921.82   16.06 2966.13   21.01 3026.02   21.98
#Mann= 4 ,-1 , 0
       0     .09       0 1346.58    .035       0 1633.42     .12       0
 1990.84     .99       0
Bank Sta=1346.58,1633.42
XS Rating Curve= 0
Exp/Cntr=.3,.1

Type RM Length L Ch R = 1 ,13640.76,1596.68,804.89,364.89
BEGIN DESCRIPTION:
451v11
Bank Station offset =      3540
END DESCRIPTION:
XS GIS Cut Line= 6
     3243985.647    13839025.389     3243677.538    13838943.776
     3242732.217    13838625.454     3242424.342    13838035.067
      3241985.88    13837887.184      3241502.52    13837728.029
#Sta/Elev= 30
       0   20.42   68.52   19.98  124.94   18.22  460.29   17.42   566.5   14.07
  720.85   15.15  815.21   14.59  910.11   12.62  987.14    9.66  1013.3    7.16
 1104.48    4.39  1155.7    4.05  1176.1    5.16 1228.68    2.21 1305.52    1.74
 1318.11     .08 1387.98   -1.04 1437.76    -.44 1459.56   -1.87 1500.98    -.11
 1760.13   -1.63 1922.09   -1.39 1954.24     -.3 1991.49    5.02 1999.04    4.26
 2037.97    9.94 2083.25   12.91 2225.71    15.6 2726.31   15.73 2953.67   17.68
#Mann= 3 ,-1 , 0
       0     .12       0 1318.11    .035       0 1954.24     .12       0
Bank Sta=1305.52,1991.49
XS Rating Curve= 0
Exp/Cntr=.3,.1

Type RM Length L Ch R = 1 ,12835.88,188.13,199.16,266.58
BEGIN DESCRIPTION:
451v10 - xs 4/4 of west texas
Bank Station offset =      3346
END DESCRIPTION:
XS GIS Cut Line= 5
     3244465.476     13837539.17       3243413.9    13837564.271
     3243144.916    13837570.692      3242783.06     13837766.69
     3241528.771    13837649.274
#Sta/Elev= 30
       0   20.14  232.38    20.4  251.21   20.92  307.44   19.96  376.13   20.13
   396.6   19.45  621.67   18.49  655.27   16.87  690.92   16.63  886.89   12.87
  964.54   10.64 1044.77   11.01 1149.16    10.1 1307.43    8.35 1328.55    7.09
 1340.31    -.26  1359.5   -2.17 1525.54   -2.49 1576.29   -1.95 1654.35   -2.69
 1705.33   -1.59 1716.17     .23 1722.37    2.74 1846.47    6.09 1879.42    9.42
 2094.08   13.62  2152.4   15.55 2171.31   15.01    2775   17.25 2992.24   16.46
#Mann= 3 , 0 , 0
       0     .12       0 1328.55    .035       0 1722.37     .12       0
Bank Sta=1328.55,1722.37
XS Rating Curve= 0
Exp/Cntr=.5,.3

Type RM Length L Ch R = 1 ,12636.71,195,153.95,153.95
BEGIN DESCRIPTION:
451s6u - xs 3/4 of west texas
Bank Station offset =      3326
END DESCRIPTION:
XS GIS Cut Line= 5
     3244628.607    13837332.537      3243372.51    13837362.919
     3243075.251    13837412.255     3242833.842    13837515.543
     3241537.522    13837623.023
#Sta/Elev= 30
       0   20.56   146.2   22.49  311.14   21.44  444.39   22.15  581.67   21.07
  687.42   18.75  829.87   18.38 1003.84   12.36 1039.45   10.37 1086.97    9.54
 1349.61    9.09 1504.19    6.24 1538.43    6.68 1613.63    5.51  1620.5     .59
 1623.41    -.17 1640.53   -2.99 1674.06   -6.37 1760.79   -3.64 1781.61     .55
  1785.8    3.99 1845.37    6.54 1850.76    8.45 1898.49   10.93 2007.22   15.21
 2053.64   15.54 2174.87   13.26 2494.88   15.99 3004.99   17.47 3121.13    16.8
#Mann= 3 ,-1 , 0
       0     .12       0 1538.43    .035       0  1785.8     .12       0
#XS Ineff= 2 , 0
       0 1560.01   14.94  1788.8       0   14.94
Permanent Ineff=
       F       F
Bank Sta=1613.63,1785.8
XS Rating Curve= 0
Exp/Cntr=.5,.3

Type RM Length L Ch R = 3 ,12560   ,,,
BEGIN DESCRIPTION:
451s6:  West Texas
END DESCRIPTION:
Bridge Culvert--1,0,-1,-1, 0
Deck Dist Width WeirC Skew NumUp NumDn MinLoCord MaxHiCord MaxSubmerge Is_Ogee
54,46.25,2.6,0, 11, 11, , , .95, 0, 0,0,,
       0 1509.65 1572.59 1579.59  1579.6    1674  1769.2 1769.21 1777.54 1826.96
    3500
   14.94   14.94   15.03   15.04   15.04   15.47   15.42   15.42   15.39   15.67
   15.67
                                   12.79   13.22   13.17
        
  134.72 1509.37 1572.31 1579.31 1579.32 1673.72 1768.92 1768.93 1777.26 1826.68
 3634.72
   14.94   14.94   15.03   15.04   15.04   15.47   15.42   15.42   15.39   15.67
   15.67
                                   12.79   13.22   13.17
        
Pier Skew, UpSta & Num, DnSta & Num=  ,1627.24, 4 ,1627.24, 4 , 3 , 3 , 0 ,,
     1.5     1.5       2       2
   -6.75   11.01   11.01   13.01
     1.5     1.5       2       2
   -6.75   11.01   11.01   13.01
Pier Skew, UpSta & Num, DnSta & Num=  ,1674.6, 4 ,1674.6, 4 , 3 , 3 , 0 ,,
     1.5     1.5       2       2
   -6.75   11.22   11.22   13.22
     1.5     1.5       2       2
   -6.75   11.22   11.22   13.22
Pier Skew, UpSta & Num, DnSta & Num=  ,1721.72, 4 ,1721.72, 4 , 3 , 3 , 0 ,,
     1.5     1.5       2       2
   -6.75    11.2    11.2    13.2
     1.5     1.5       2       2
   -6.75    11.2    11.2    13.2
BR Coef=-1 , 0 , 0 ,, 0 ,,,.8,-1,,0,
WSPro=,,,, 1 ,,,, 0 ,,,, 0 ,,,,-1 ,-1 ,-1 , 0 , 0 , 0 , 0 , 0
BC Design=,, 0 ,, 0 ,,,,,,
BC HTab HWMax=22.49

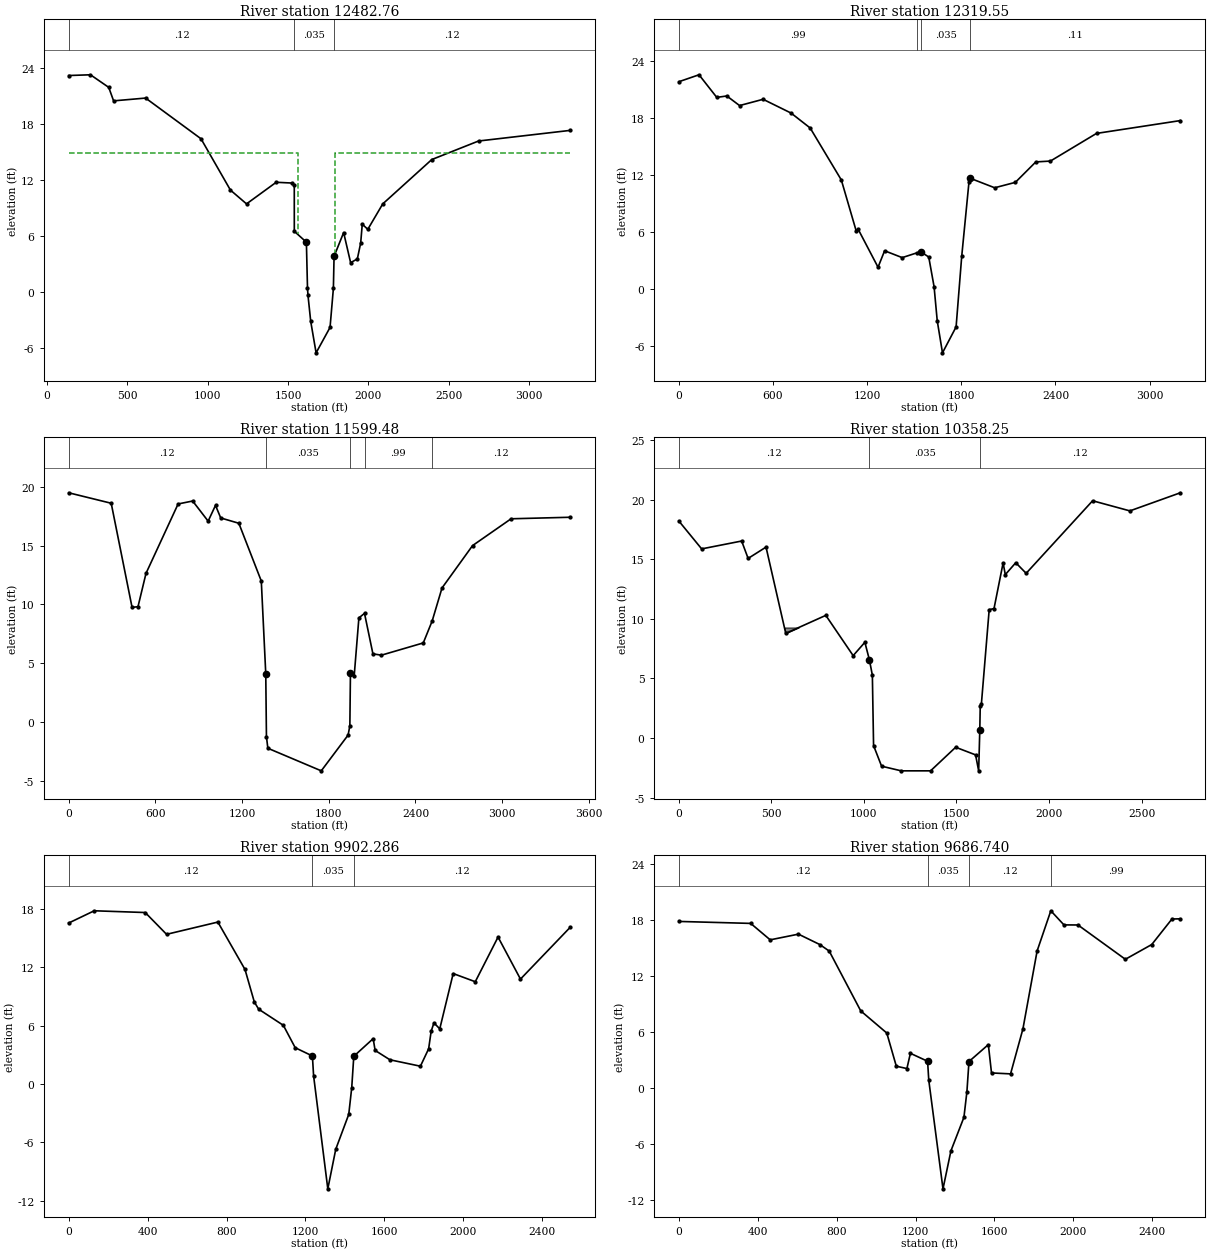
Type RM Length L Ch R = 1 ,12482.76,77.18,162.91,160.16
BEGIN DESCRIPTION:
Copy of 451s6u - xs 2/4 of west texas
Bank Station offset =      3461
END DESCRIPTION:
XS GIS Cut Line= 5
     3244607.453     13837179.48     3243355.431    13837150.659
     3243054.097    13837259.197     3242812.687    13837362.486
     3241546.272     13837579.27
#Sta/Elev= 30
  134.72   23.24   270.2   23.32  383.87   21.97  414.16   20.52  613.32   20.82
  957.99   16.45 1141.09   10.94 1241.21    9.46 1425.81   11.78 1521.47    11.7
 1538.32   11.47 1538.43    6.52 1613.63    5.35  1620.5     .43 1623.41    -.33
 1640.53   -3.15 1674.06   -6.53 1760.79    -3.8 1781.61     .39  1785.8    3.83
 1845.37    6.38 1888.83    3.15 1930.57    3.55  1951.5    5.27 1961.22    7.28
 1995.71    6.73 2088.79    9.46 2393.81   14.22 2684.77   16.21 3254.77   17.35
#Mann= 3 ,-1 , 0
  134.72     .12       0 1538.43    .035       0  1785.8     .12       0
#XS Ineff= 2 , 0
       0 1559.57   14.94 1788.68       0   14.94
Permanent Ineff=
       F       F
Bank Sta=1613.63,1785.8
XS Rating Curve= 0
Exp/Cntr=.5,.3

Type RM Length L Ch R = 1 ,12319.55,1370.58,720.07,304.09
BEGIN DESCRIPTION:
Copy of 451s6u - xs 1/4 of west texas
Bank Station offset =      3587
Higher c/e coeeficients used to avoid negative changes in WSEL. This agrees with the change in cross sectional area d/s.
Lowered overbank Manning's from 0.12 to 0.11 to avoid -ve changes in WSEL. The use of lower manning's is justified based on aerial photographs.
END DESCRIPTION:
XS GIS Cut Line= 6
      3244642.25       13837029.     3243249.182     13837100.75
      3242993.91    13837195.774       3242943.7     13837170.97
     3242872.257    13837136.814       3241537.5       13837536.
#Sta/Elev= 30
       0   21.84  128.56   22.57  241.67   20.19  305.66   20.34  386.95   19.33
  536.86   19.99  715.18   18.54  836.84   16.97  1035.4    11.5 1129.76    6.16
 1142.47    6.32 1269.31    2.32 1311.14    4.05  1423.3    3.33 1514.74    3.82
 1544.51    3.92 1592.53    3.39 1626.45     .27 1646.48   -3.31 1680.01   -6.69
 1766.74   -3.96 1802.49    3.46 1848.64   11.26 1855.03   11.69 2012.57   10.68
 2144.33   11.25 2274.61    13.4 2367.86   13.49 2661.41    16.4 3195.66   17.75
#Mann= 4 ,-1 , 0
       0     .99       0 1514.74     .11       0 1544.51    .035       0
 1855.03     .11       0
Bank Sta=1544.51,1855.03
XS Rating Curve= 0
Exp/Cntr=.5,.3

Type RM Length L Ch R = 1 ,11599.48,1185.06,1241.23,1269.02
BEGIN DESCRIPTION:
451v9
Bank Station offset =      3252
END DESCRIPTION:
XS GIS Cut Line= 4
     3244237.092    13835570.719     3243015.005    13836227.372
     3242815.674    13836740.234      3241463.86    13837463.042
#Sta/Elev= 30
       0   19.49  294.29    18.6  438.67    9.75  479.68    9.81  535.06   12.64
   757.3   18.54  857.98   18.79  965.09   17.08  1016.1   18.42 1052.22   17.35
 1177.56    16.9 1332.98   11.99  1363.9     4.1 1368.55   -1.23 1378.31   -2.22
 1747.96   -4.14 1933.75    -1.1 1945.87     -.3  1949.9    4.17 1975.71    3.91
 2008.37    8.86 2047.21    9.24 2105.49     5.8 2164.42    5.69 2453.94    6.73
 2515.61     8.6 2583.53    11.4 2794.85      15 3061.63   17.28 3470.49   17.41
#Mann= 5 ,-1 , 0
       0     .12       0  1363.9    .035       0  1949.9     .12       0
 2047.21     .99       0 2515.61     .12       0
Bank Sta=1363.9,1949.9
XS Rating Curve= 0
Exp/Cntr=.3,.1

Type RM Length L Ch R = 1 ,10358.25,316.79,455.97,586.41
BEGIN DESCRIPTION:
451v8
Bank Station offset =      3640
Small area inundated on ROB in 100yr flows back into main stem. So it is not ineffective
END DESCRIPTION:
XS GIS Cut Line= 4
     3242734.669    13835233.566       3241892.5    13835851.464
     3241606.684    13836347.607     3240841.809    13837127.489
#Sta/Elev= 30
       0   18.21  123.24   15.87  339.33   16.53  374.29   15.07  471.02   16.02
  577.58    8.78  793.98   10.29  941.81    6.91  1005.1    8.03  1029.6    6.55
 1045.54    5.27 1052.06    -.64  1095.4   -2.37 1201.57   -2.76 1360.08   -2.76
 1495.64    -.78 1603.22   -1.42 1619.85   -2.76 1625.97     .66 1628.39     2.7
 1634.44    2.83 1676.73   10.77 1702.78   10.86  1751.9   14.69 1763.78   13.71
 1820.27   14.71 1876.43   13.82 2235.53   19.91 2436.82   19.06 2709.47   20.58
#Mann= 3 , 0 , 0
       0     .12       0  1029.6    .035       0 1625.97     .12       0
#Block Obstruct= 2 , 0
       0     720    9.27               0
Bank Sta=1029.6,1625.97
XS Rating Curve= 0
Exp/Cntr=.3,.1

Type RM Length L Ch R = 1 ,9902.286,146.41,215.54,310.33
BEGIN DESCRIPTION:
Copy of 451s5u - xs 4/4 of Market street
Bank offset =     3686
END DESCRIPTION:
XS GIS Cut Line= 5
     3242693.896    13835164.148     3242102.066    13835451.944
     3241736.899    13835605.079     3241277.494    13835887.789
     3240441.142    13836335.414
#Sta/Elev= 30
       0   16.54   129.6    17.8     388   17.62   496.2   15.38  756.25   16.64
  893.77   11.77  940.99    8.43  963.02    7.69  1088.2    6.03 1148.31    3.73
 1235.46    2.88 1241.51     .84 1313.53  -10.77 1353.82    -6.7 1419.67   -3.12
 1434.87    -.36 1445.22    2.85 1543.48    4.66 1553.39    3.45 1628.42    2.49
 1782.97    1.83 1824.68    3.62 1837.31    5.41 1851.52    6.28 1881.03    5.67
 1949.08   11.35 2061.08   10.51  2176.5    15.1 2290.13   10.78  2542.1    16.1
#Mann= 3 , 0 , 0
       0     .12       0 1235.46    .035       0 1445.22     .12       0
Bank Sta=1235.46,1445.22
XS Rating Curve= 0
Exp/Cntr=.3,.1

Type RM Length L Ch R = 1 ,9686.740,79,50.8,50.8
BEGIN DESCRIPTION:
Copy of 451s5u - xs 3.5/4 of Market street
Bank Station offset =      3661
END DESCRIPTION:
XS GIS Cut Line= 5
     3242640.094    13835138.879     3242059.888    13835432.564
     3241658.759    13835561.498     3241078.553    13835640.292
      3240269.13    13835998.443
#Sta/Elev= 30
       0   17.84  364.21   17.63  463.11   15.87  606.32   16.48  714.36   15.37
   762.3   14.67  922.05    8.27 1054.16     5.9 1102.47    2.35  1156.1     2.1
 1173.83    3.73 1260.98    2.88 1267.03     .84 1339.05  -10.77 1379.34    -6.7
 1445.19   -3.12 1460.39    -.36 1470.74    2.85    1569    4.66 1585.01    1.63
  1681.6    1.53 1744.24    6.34  1816.2   14.68 1885.72   18.98 1952.22   17.47
 2023.36   17.46 2263.54   13.79 2397.42   15.37 2499.77    18.1 2542.29   18.12
#Mann= 4 ,-1 , 0
       0     .12       0 1260.98    .035       0 1470.74     .12       0
 1885.72     .99       0
Bank Sta=1260.98,1470.74
XS Rating Curve= 0
Exp/Cntr=.5,.3

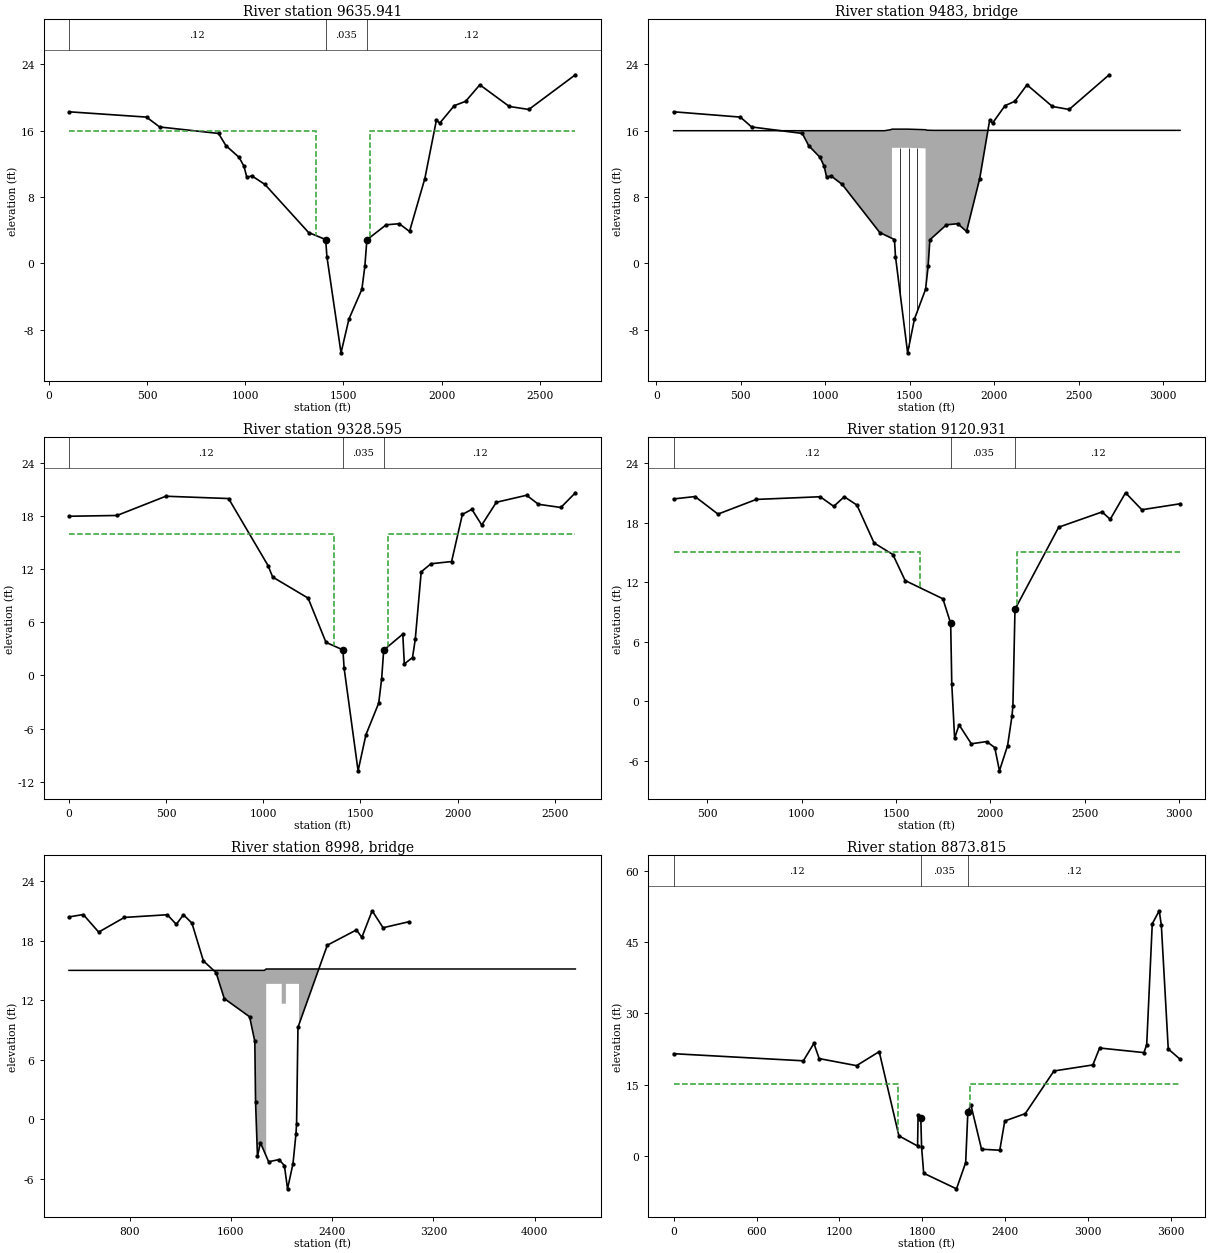
Type RM Length L Ch R = 1 ,9635.941,292.76,307.35,307.52
BEGIN DESCRIPTION:
451s5u - xs 3/4 of Market street
Bank Station offset =      3614
END DESCRIPTION:
XS GIS Cut Line= 5
     3242641.549    13835097.468     3241996.755    13835429.339
      3241488.42    13835534.794     3241140.882    13835579.405
     3240169.685    13835744.726
#Sta/Elev= 30
  101.72   18.28  496.96   17.64  563.66   16.45  863.84   15.67  901.23   14.21
  968.54   12.79  993.14   11.73 1008.11   10.38 1033.54   10.56 1100.38    9.52
 1322.58    3.73 1409.73    2.88 1415.78     .84  1487.8  -10.77 1528.09    -6.7
 1593.94   -3.12 1609.14    -.36 1619.49    2.85 1717.75    4.66  1784.6    4.79
 1836.72    3.86 1914.86   10.24 1973.74   17.28  1990.6   16.91 2064.59   19.02
 2122.67   19.54 2194.79   21.53 2345.17   18.92 2444.42   18.56 2681.62   22.74
#Mann= 3 , 0 , 0
  101.72     .12       0 1409.73    .035       0 1619.49     .12       0
#XS Ineff= 2 , 0
  101.72 1361.72      16 1636.72  101.72      16
Permanent Ineff=
       F       F
Bank Sta=1409.73,1619.49
XS Rating Curve= 0
Exp/Cntr=.5,.3

Type RM Length L Ch R = 3 ,9483    ,,,
BEGIN DESCRIPTION:
451s5:  Market st.
END DESCRIPTION:
Bridge Culvert--1,0,-1,-1, 0
Deck Dist Width WeirC Skew NumUp NumDn MinLoCord MaxHiCord MaxSubmerge Is_Ogee
126,54,2.6,0, 9, 9, , , .95, 0, 0,0,,
  101.72 1350.18 1387.32 1394.97 1487.72 1594.14 1601.77 1643.47 3101.72
      16      16   16.12   16.19   16.19   16.12   16.06   16.04   16.04
                           13.94   13.94   13.87
       0 1350.46  1387.6 1395.25    1488 1594.42 1602.05 1643.75    3000
      16      16   16.12   16.19   16.19   16.12   16.06   16.04   16.04
                           13.94   13.94   13.87
Pier Skew, UpSta & Num, DnSta & Num=  ,1444.28, 4 ,1444.28, 4 , 3 , 3 , 0 ,,
     1.5     1.5     2.2     2.2
     -11   11.74   11.74   13.94
     1.5     1.5     2.2     2.2
     -11   11.74   11.74   13.94
Pier Skew, UpSta & Num, DnSta & Num=  ,1494.2, 4 ,1494.2, 4 , 3 , 3 , 0 ,,
     1.5     1.5     2.2     2.2
     -11   11.74   11.74   13.94
     1.5     1.5     2.2     2.2
     -11   11.74   11.74   13.94
Pier Skew, UpSta & Num, DnSta & Num=  ,1543.94, 4 ,1543.94, 4 , 3 , 3 , 0 ,,
     1.3     1.3     2.2     2.2
     -11   11.74   11.74   13.94
     1.3     1.3     2.2     2.2
     -11   11.74   11.74   13.94
BR Coef=-1 , 0 , 0 ,, 0 ,,,.8,-1,,0,
WSPro=,,,, 1 ,,,, 0 ,,,, 0 ,,,,-1 ,-1 ,-1 , 0 , 0 , 0 , 0 , 0
BC Design=,, 0 ,, 0 ,,,,,,
BC HTab HWMax=22.74

Type RM Length L Ch R = 1 ,9328.595,208,207.66,202.12
BEGIN DESCRIPTION:
Copy of 451s5u -
xs 4/4 of UP rail road
xs 2/4 of Market street
Bank Station offset =      3512
END DESCRIPTION:
XS GIS Cut Line= 5
     3242684.527    13834990.023      3241982.55    13835226.403
     3241359.177    13835287.136     3241016.709    13835335.121
     3240141.651    13835512.924
#Sta/Elev= 30
       0   17.96  247.69   18.05  498.53   20.22  821.45   19.96 1024.33    12.4
 1048.38    11.1 1230.71    8.72 1322.58    3.73 1409.73    2.88 1415.78     .84
  1487.8  -10.77 1528.09    -6.7 1593.94   -3.12 1609.14    -.36 1619.49    2.85
 1717.75    4.66 1725.73    1.29  1767.8    2.02 1781.95    4.06 1812.57   11.69
 1862.72    12.6 1968.94   12.85 2024.34   18.17 2073.12   18.74 2124.01   16.97
 2199.22   19.54 2354.87   20.33 2415.81   19.31  2531.1   18.95 2605.78   20.61
#Mann= 3 , 0 , 0
       0     .12       0 1409.73    .035       0 1619.49     .12       0
#XS Ineff= 2 , 0
       0    1363      16    1640       0      16
Permanent Ineff=
       F       F
Bank Sta=1409.73,1619.49
XS Rating Curve= 0
Exp/Cntr=.5,.3

Type RM Length L Ch R = 1 ,9120.931,272.31,247.12,233.6
BEGIN DESCRIPTION:
451s4u - xs 3/4 of UP rail road
xs 1/4 of Market street
Bank Station offset =      3273
END DESCRIPTION:
XS GIS Cut Line= 5
     3242684.527    13834911.229     3241833.624     13834950.82
     3241242.956    13835112.806     3240900.489    13835160.791
     3240048.531    13835355.338
#Sta/Elev= 30
  321.09   20.42  434.54   20.66  556.04   18.89  759.08   20.37 1097.94   20.64
 1169.47   19.67 1225.42   20.64 1292.47    19.8  1383.3   15.98 1482.97   14.81
 1547.91   12.19 1748.03   10.35 1789.24    7.87  1795.1    1.78 1810.21   -3.71
 1833.78   -2.36  1898.6   -4.27  1980.3   -4.05 2022.99   -4.66 2047.73      -7
 2090.93   -4.45 2114.18   -1.47 2119.13    -.43 2130.08    9.29 2361.81   17.57
 2591.94   19.11 2634.67   18.36 2716.02   21.04 2802.27   19.33 3005.09   19.93
#Mann= 3 , 0 , 0
  321.09     .12       0 1789.24    .035       0 2130.08     .12       0
#XS Ineff= 2 , 0
  321.09 1624.77   15.03 2143.09  321.09   15.03
Permanent Ineff=
       F       F
Bank Sta=1789.24,2130.08
XS Rating Curve= 0
Exp/Cntr=.5,.3

Type RM Length L Ch R = 3 ,8998    ,,,
BEGIN DESCRIPTION:
451s4:  UP rail road
END DESCRIPTION:
Bridge Culvert--1,0,-1,-1, 0
Deck Dist Width WeirC Skew NumUp NumDn MinLoCord MaxHiCord MaxSubmerge Is_Ogee
121,5,2.6,0, 12, 12, , , .95, 0, 0,0,,
   321.1 1864.49 1878.98 1878.99 2001.97 2001.97 2034.52 2034.52  2138.1 2138.11
  2163.1  4321.1
   15.03   15.03   15.17   15.17   15.17   15.17   15.17   15.17   15.17   15.17
   15.17   15.17
                           13.67   13.67   11.67   11.67   13.67   13.67
                
       0 1864.39 1878.88 1878.89 2001.87 2001.87 2034.42 2034.42    2138 2138.01
    2163    4000
   15.03   15.03   15.17   15.17   15.17   15.17   15.17   15.17   15.17   15.17
   15.17   15.17
                           13.67   13.67   11.67   11.67   13.67   13.67
                
Pier Skew, UpSta & Num, DnSta & Num=  ,1559.21, 2 ,1880.21, 2 , 0 , 0 , 0 ,,
     1.2     1.2
      -7
     1.2     1.2
      -7
Pier Skew, UpSta & Num, DnSta & Num=  ,1893.05, 2 ,1893.05, 2 , 0 , 0 , 0 ,,
     1.2     1.2
      -7
     1.2     1.2
      -7
Pier Skew, UpSta & Num, DnSta & Num=  ,1908.3, 2 ,1908.3, 2 , 0 , 0 , 0 ,,
     1.2     1.2
      -7
     1.2     1.2
      -7
Pier Skew, UpSta & Num, DnSta & Num=  ,1922.15, 2 ,1922.15, 2 , 0 , 0 , 0 ,,
     1.2     1.2
      -7
     1.2     1.2
      -7
Pier Skew, UpSta & Num, DnSta & Num=  ,1935.63, 2 ,1935.63, 2 , 0 , 0 , 0 ,,
     1.2     1.2
      -7
     1.2     1.2
      -7
Pier Skew, UpSta & Num, DnSta & Num=  ,1949.86, 2 ,1949.86, 2 , 0 , 0 , 0 ,,
     1.2     1.2
      -7
     1.2     1.2
      -7
Pier Skew, UpSta & Num, DnSta & Num=  ,1963.76, 2 ,1963.76, 2 , 0 , 0 , 0 ,,
     1.2     1.2
      -7
     1.2     1.2
      -7
Pier Skew, UpSta & Num, DnSta & Num=  ,1977.59, 2 ,1977.59, 2 , 0 , 0 , 0 ,,
     1.2     1.2
      -7
     1.2     1.2
      -7
Pier Skew, UpSta & Num, DnSta & Num=  ,1991.52, 2 ,1991.52, 2 , 0 , 0 , 0 ,,
     1.2     1.2
      -7
     1.2     1.2
      -7
Pier Skew, UpSta & Num, DnSta & Num=  ,2006.15, 2 ,2006.15, 2 , 0 , 0 , 0 ,,
     1.2     1.2
      -7
     1.2     1.2
      -7
Pier Skew, UpSta & Num, DnSta & Num=  ,2019.95, 2 ,2019.95, 2 , 0 , 0 , 0 ,,
     1.2     1.2
      -7
     1.2     1.2
      -7
Pier Skew, UpSta & Num, DnSta & Num=  ,2034.1, 2 ,2034.1, 2 , 0 , 0 , 0 ,,
     1.2     1.2
      -7
     1.2     1.2
      -7
Pier Skew, UpSta & Num, DnSta & Num=  ,2047.74, 2 ,2047.74, 2 , 0 , 0 , 0 ,,
     1.2     1.2
      -7
     1.2     1.2
      -7
Pier Skew, UpSta & Num, DnSta & Num=  ,2061.48, 2 ,2061.48, 2 , 0 , 0 , 0 ,,
     1.2     1.2
      -7
     1.2     1.2
      -7
Pier Skew, UpSta & Num, DnSta & Num=  ,2075.22, 2 ,2075.22, 2 , 0 , 0 , 0 ,,
     1.2     1.2
      -7
     1.2     1.2
      -7
Pier Skew, UpSta & Num, DnSta & Num=  ,2089.29, 2 ,2089.29, 2 , 0 , 0 , 0 ,,
     1.2     1.2
      -7
     1.2     1.2
      -7
Pier Skew, UpSta & Num, DnSta & Num=  ,2103.92, 2 ,2103.92, 2 , 0 , 0 , 0 ,,
     1.2     1.2
      -7
     1.2     1.2
      -7
Pier Skew, UpSta & Num, DnSta & Num=  ,2118.21, 2 ,2118.21, 2 , 0 , 0 , 0 ,,
     1.2     1.2
      -7
     1.2     1.2
      -7
Pier Skew, UpSta & Num, DnSta & Num=  ,2131.76, 2 ,2131.76, 2 , 0 , 0 , 0 ,,
     1.2     1.2
      -7
     1.2     1.2
      -7
Pier Skew, UpSta & Num, DnSta & Num=  ,145.2, 2 ,2145.2, 2 , 0 , 0 , 0 ,,
     1.2     1.2
      -7
     1.2     1.2
      -7
Pier Skew, UpSta & Num, DnSta & Num=  ,2159.62, 2 ,2159.62, 2 , 0 , 0 , 0 ,,
     1.2     1.2
      -7
     1.2     1.2
      -7
Pier Skew, UpSta & Num, DnSta & Num=  ,2173.18, 2 ,2173.18, 2 , 0 , 0 , 0 ,,
     1.2     1.2
      -7
     1.2     1.2
      -7
Pier Skew, UpSta & Num, DnSta & Num=  ,2187.39, 2 ,2187.39, 2 , 0 , 0 , 0 ,,
     1.2     1.2
      -7
     1.2     1.2
      -7
Pier Skew, UpSta & Num, DnSta & Num=  ,2200.98, 2 ,2200.98, 2 , 0 , 0 , 0 ,,
     1.2     1.2
      -7
     1.2     1.2
      -7
Pier Skew, UpSta & Num, DnSta & Num=  ,2215.24, 2 ,2215.24, 2 , 0 , 0 , 0 ,,
     1.2     1.2
      -7
     1.2     1.2
      -7
Pier Skew, UpSta & Num, DnSta & Num=  ,2229.42, 2 ,2229.42, 2 , 0 , 0 , 0 ,,
     1.2     1.2
      -7
     1.2     1.2
      -7
Pier Skew, UpSta & Num, DnSta & Num=  ,2237.98, 2 ,2237.98, 2 , 0 , 0 , 0 ,,
     1.2     1.2
      -7
     1.2     1.2
      -7
Pier Skew, UpSta & Num, DnSta & Num=  ,2252.45, 2 ,2252.45, 2 , 0 , 0 , 0 ,,
     1.2     1.2
      -7
     1.2     1.2
      -7
Pier Skew, UpSta & Num, DnSta & Num=  ,2256.08, 2 ,2256.08, 2 , 0 , 0 , 0 ,,
     1.2     1.2
      -7
     1.2     1.2
      -7
Pier Skew, UpSta & Num, DnSta & Num=  ,2288.63, 2 ,2288.63, 2 , 0 , 0 , 0 ,,
     1.2     1.2
      -7
     1.2     1.2
      -7
Pier Skew, UpSta & Num, DnSta & Num=  ,2292.81, 2 ,2292.81, 2 , 0 , 0 , 0 ,,
     1.2     1.2
      -7
     1.2     1.2
      -7
Pier Skew, UpSta & Num, DnSta & Num=  ,2307.23, 2 ,2307.23, 2 , 0 , 0 , 0 ,,
     1.2     1.2
      -7
     1.2     1.2
      -7
Pier Skew, UpSta & Num, DnSta & Num=  ,2317.21, 2 ,2317.21, 2 , 0 , 0 , 0 ,,
     1.2     1.2
      -7
     1.2     1.2
      -7
BR Coef=-1 , 1 , 1 ,1.25, 0 ,,,.8,-1,2,0,
WSPro=,,,, 1 ,,,, 0 ,,,, 0 ,,,,-1 ,-1 ,-1 , 0 , 0 , 0 , 0 , 0
BC Design=,, 0 ,, 0 ,,,,,,
BC HTab HWMax=21.04

Type RM Length L Ch R = 1 ,8873.815,486.99,452.7,448.59
BEGIN DESCRIPTION:
Copy of 451s4u - xs 2/4 of UP rail road
Bank Station offset =      2952
END DESCRIPTION:
XS GIS Cut Line= 5
     3243119.043    13834700.226     3242026.052    13834675.199
     3241368.616    13834817.623     3240728.533    13834967.699
     3239511.023    13835218.469
#Sta/Elev= 30
       0    21.5  938.89      20 1015.33   23.67 1053.68   20.47    1324   18.98
 1488.17   21.93 1630.74    4.18 1765.96    2.03 1769.78    8.63 1789.24    7.87
  1795.1    1.78 1810.21   -3.71 2047.73      -7 2114.18   -1.47 2130.08    9.29
 2151.95    10.7 2228.93    1.36 2361.05    1.14 2397.26    7.31 2545.49    8.86
 2753.36   17.86 3034.77   19.13    3084    22.7 3404.76   21.73  3424.8   23.39
    3465   48.91 3515.41   51.64 3530.72    48.6 3580.72    22.5 3666.47   20.33
#Mann= 3 , 0 , 0
       0     .12       0 1789.24    .035       0 2130.08     .12       0
#XS Ineff= 2 , 0
       0 1624.68   15.03    2143       0   15.03
Permanent Ineff=
       F       F
Bank Sta=1789.24,2130.08
XS Rating Curve= 0
Exp/Cntr=.5,.3