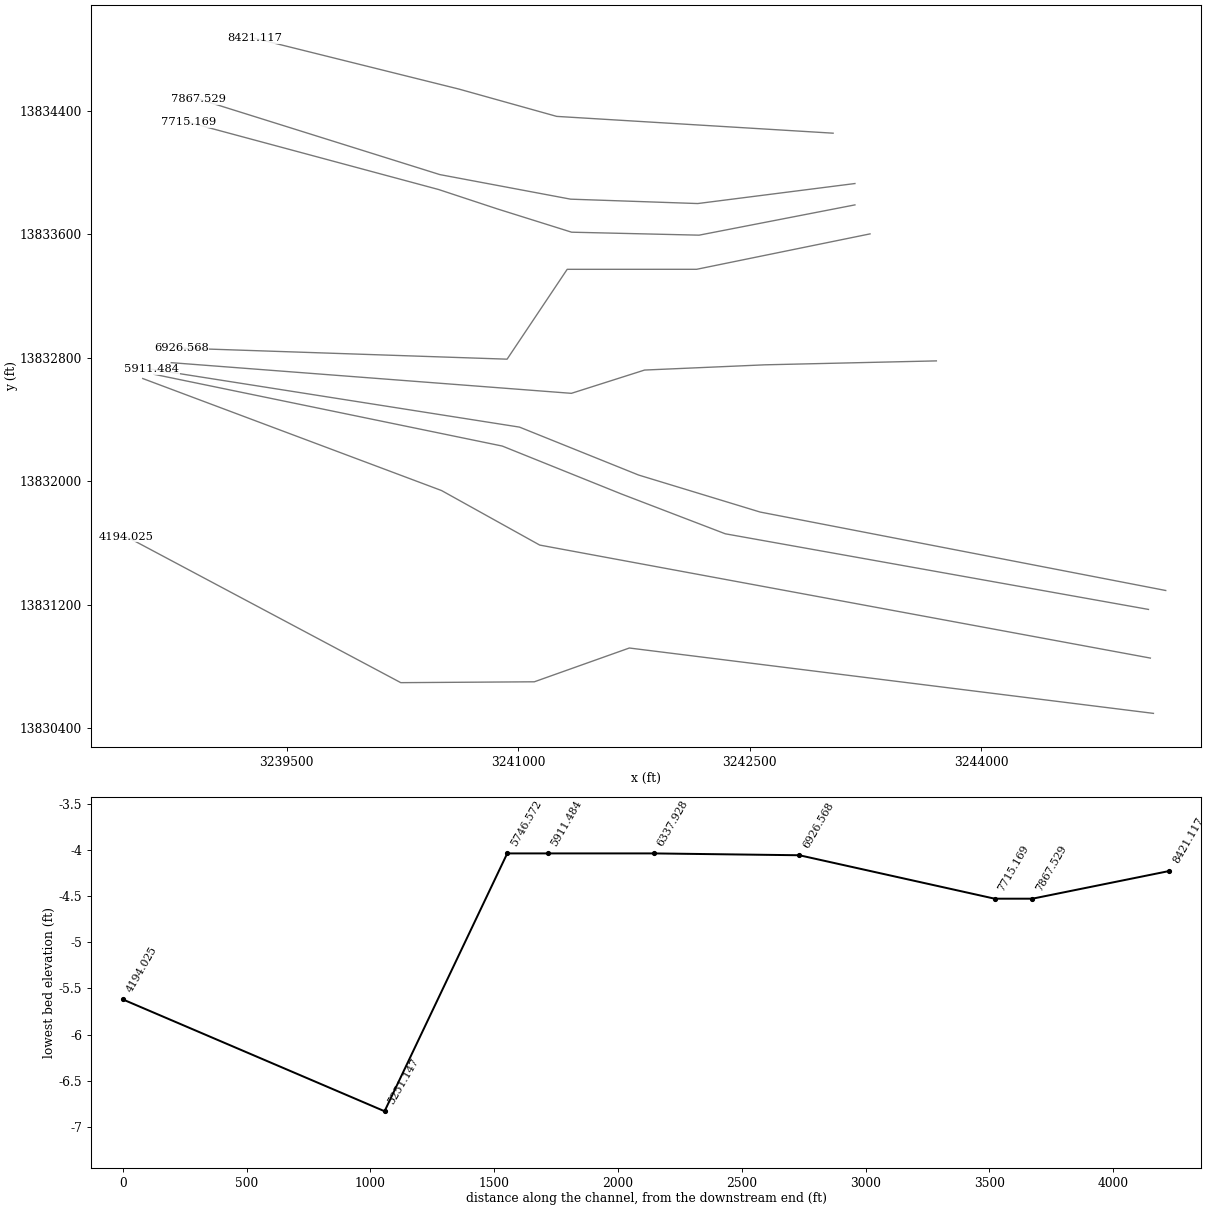
HEC-RAS study O100-00-00.prj: O100-00-00

--- O100-00-00.g01 (geometry) --- (continued)

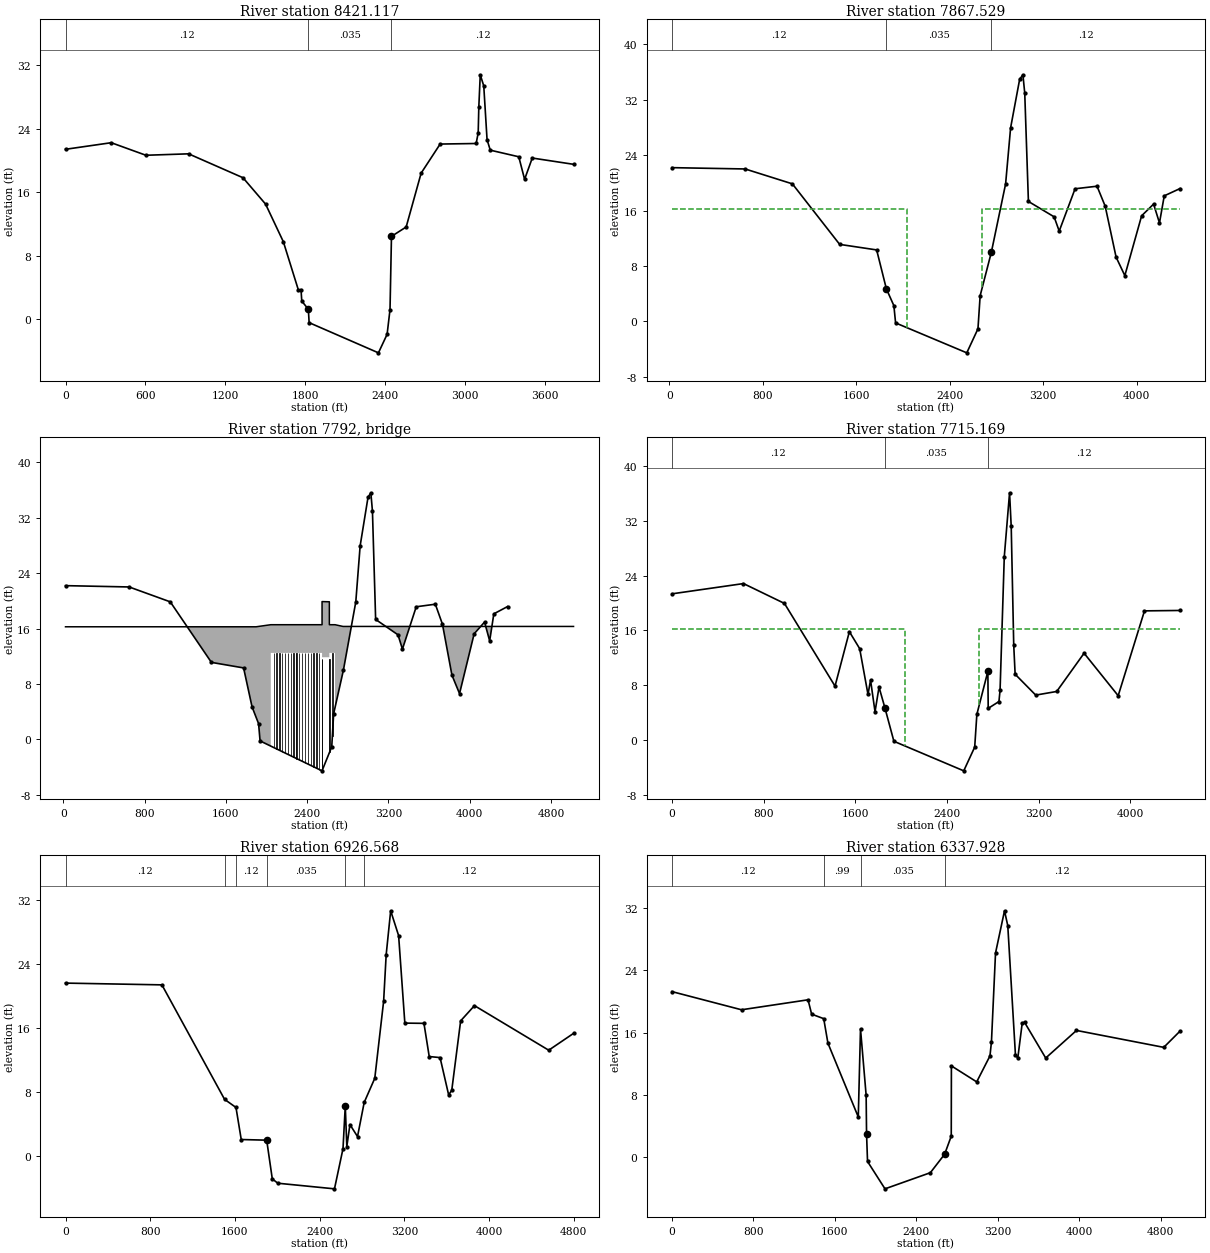
Type RM Length L Ch R = 1 ,8421.117,511.16,553.59,596.52
BEGIN DESCRIPTION:
451v7 -
xs 4/4 of RR bridge #1
xs 1/4 of UP rail road
Bank Station offset =      2651
END DESCRIPTION:
XS GIS Cut Line= 4
     3243040.796    13834254.793     3241249.721    13834363.611
     3240615.029    13834540.904     3239294.271    13834869.378
#Sta/Elev= 30
       0   21.39  343.37   22.22  603.66   20.64  924.19   20.82 1332.56   17.81
 1502.19   14.49 1635.65    9.75 1748.81    3.66 1768.21    3.74 1773.85    2.29
 1823.26    1.25 1829.16    -.43 2349.47   -4.23 2414.54    -1.9 2436.43    1.22
 2447.32   10.43 2557.64   11.61 2670.07   18.39 2812.76   22.05 3083.03   22.12
 3098.48   23.46  3103.1   26.71 3113.94   30.77 3140.24   29.37 3164.99    22.6
 3189.21   21.28  3403.1   20.45 3446.83   17.61 3504.42   20.29 3814.36    19.5
#Mann= 3 , 0 , 0
       0     .12       0 1823.26    .035       0 2447.32     .12       0
Bank Sta=1823.26,2447.32
XS Rating Curve= 0
Exp/Cntr=.5,.3

Type RM Length L Ch R = 1 ,7867.529,180.44,152.36,125.6
BEGIN DESCRIPTION:
451s3u - xs 3/4 of RR bridge #1
Bank Station offset =      2476
high bank in ROB is elevated highway
END DESCRIPTION:
XS GIS Cut Line= 5
     3243182.176    13833928.531     3242163.437    13833798.854
     3241339.815    13833827.255     3240492.575     13833986.45
     3238930.156    13834475.794
#Sta/Elev= 30
   22.05   22.21  648.58   22.02 1053.14   19.87 1457.96   11.13 1774.73   10.33
 1857.92    4.71 1922.24    2.28  1936.9    -.21 2546.55   -4.53 2642.24   -1.06
 2660.99    3.72 2756.97      10 2878.96   19.86 2921.71   27.95 2999.26   34.97
 3027.12   35.62 3042.84   32.98 3074.28   17.33 3294.34   15.11 3338.01   13.05
 3473.77   19.16 3661.82   19.53 3731.89   16.64 3825.08    9.29 3899.92    6.62
 4043.77   15.26 4146.28   16.95 4196.54   14.23 4237.45   18.14 4372.44   19.19
#Mann= 3 , 0 , 0
   22.05     .12       0 1857.92    .035       0 2756.97     .12       0
#XS Ineff= 2 , 0
   22.05 2037.05   16.27 2680.05   22.05   16.27
Permanent Ineff=
       F       F
Bank Sta=1857.92,2756.97
XS Rating Curve= 0
Exp/Cntr=.5,.3

Type RM Length L Ch R = 3 ,7792    ,,,
BEGIN DESCRIPTION:
451s3:  RR Bridge # 1
END DESCRIPTION:
Bridge Culvert--1,0,-1,-1, 0
Deck Dist Width WeirC Skew NumUp NumDn MinLoCord MaxHiCord MaxSubmerge Is_Ogee
70,11.8,2.6,0, 12, 12, , , .95, 0, 0,0,,
   22.05  1897.4 2042.31 2042.32  2546.9  2546.9 2618.84 2618.84 2674.69  2674.7
 2753.39 5022.05
   16.27   16.27   16.57   16.57   16.57   19.91   19.88   16.57   16.57   16.57
   16.32   16.32
                            12.5    12.5   11.87   11.87    12.5    12.5
                
       0 1898.35 2043.26 2043.27 2547.85 2547.85 2619.79 2619.79 2675.64 2675.65
 2754.34    5000
   16.27   16.27   16.57   16.57   16.57   19.91   19.88   16.57   16.57   16.57
   16.32   16.32
                            12.5    12.5   11.87   11.87    12.5    12.5
                
Pier Skew, UpSta & Num, DnSta & Num=  ,2070.75, 4 ,2070.75, 4 , 3 , 3 , 0 ,,
       2       2       3       3
   -4.75    9.52    9.52   12.52
       2       2       3       3
   -4.75    9.52    9.52   12.52
Pier Skew, UpSta & Num, DnSta & Num=  ,2098.7, 4 ,2098.7, 4 , 3 , 3 , 0 ,,
       2       2       3       3
   -4.75     9.5     9.5    12.5
       2       2       3       3
   -4.75     9.5     9.5    12.5
Pier Skew, UpSta & Num, DnSta & Num=  ,2126.74, 4 ,2126.74, 4 , 3 , 3 , 0 ,,
       2       2       3       3
   -4.75    9.51    9.51   12.51
       2       2       3       3
   -4.75    9.51    9.51   12.51
Pier Skew, UpSta & Num, DnSta & Num=  ,2154.88, 4 ,2154.88, 4 , 3 , 3 , 0 ,,
       2       2       3       3
   -4.75    9.56    9.56   12.56
       2       2       3       3
   -4.75    9.56    9.56   12.56
Pier Skew, UpSta & Num, DnSta & Num=  ,2182.89, 4 ,2182.89, 4 , 3 , 3 , 0 ,,
       2       2       3       3
   -4.75    9.52    9.52   12.52
       2       2       3       3
   -4.75    9.52    9.52   12.52
Pier Skew, UpSta & Num, DnSta & Num=  ,2210.93, 4 ,2210.93, 4 , 3 , 3 , 0 ,,
       2       2       3       3
   -4.75    9.49    9.49   12.49
       2       2       3       3
   -4.75    9.49    9.49   12.49
Pier Skew, UpSta & Num, DnSta & Num=  ,2238.95, 4 ,2238.95, 4 , 3 , 3 , 0 ,,
       2       2       3       3
   -4.75     9.5     9.5    12.5
       2       2       3       3
   -4.75     9.5     9.5    12.5
Pier Skew, UpSta & Num, DnSta & Num=  ,2267, 4 ,2267, 4 , 3 , 3 , 0 ,,
       2       2       3       3
   -4.75     9.5     9.5    12.5
       2       2       3       3
   -4.75     9.5     9.5    12.5
Pier Skew, UpSta & Num, DnSta & Num=  ,2293.99, 4 ,2293.99, 4 , 3 , 3 , 0 ,,
       2       2    2.75    2.75
   -4.75    9.51    9.51   12.51
       2       2    2.75    2.75
   -4.75    9.51    9.51   12.51
Pier Skew, UpSta & Num, DnSta & Num=  ,2296.74, 4 ,2296.74, 4 , 3 , 3 , 0 ,,
       2       2    2.75    2.75
   -4.75    9.51    9.51   12.51
       2       2    2.75    2.75
   -4.75    9.51    9.51   12.51
Pier Skew, UpSta & Num, DnSta & Num=  ,2323.27, 4 ,2323.27, 4 , 3 , 3 , 0 ,,
       2       2       3       3
   -4.75    9.51    9.51   12.51
       2       2       3       3
   -4.75    9.51    9.51   12.51
Pier Skew, UpSta & Num, DnSta & Num=  ,2351.24, 4 ,2351.24, 4 , 3 , 3 , 0 ,,
       2       2       3       3
   -4.75    9.52    9.52   12.52
       2       2       3       3
   -4.75    9.52    9.52   12.52
Pier Skew, UpSta & Num, DnSta & Num=  ,2379.34, 4 ,2379.34, 4 , 3 , 3 , 0 ,,
       2       2       3       3
   -4.75    9.51    9.51   12.51
       2       2       3       3
   -4.75    9.51    9.51   12.51
Pier Skew, UpSta & Num, DnSta & Num=  ,2407.24, 4 ,2407.24, 4 , 3 , 3 , 0 ,,
       2       2       3       3
   -4.75    9.49    9.49   12.49
       2       2       3       3
   -4.75    9.49    9.49   12.49
Pier Skew, UpSta & Num, DnSta & Num=  ,2435.37, 4 ,2435.37, 4 , 3 , 3 , 0 ,,
       2       2       3       3
   -4.75    9.52    9.52   12.52
       2       2       3       3
   -4.75    9.52    9.52   12.52
Pier Skew, UpSta & Num, DnSta & Num=  ,2463.21, 4 ,2463.21, 4 , 3 , 3 , 0 ,,
       2       2       3       3
   -4.75    9.46    9.46   12.46
       2       2       3       3
   -4.75    9.46    9.46   12.46
Pier Skew, UpSta & Num, DnSta & Num=  ,2491.37, 4 ,2491.37, 4 , 3 , 3 , 0 ,,
       2       2       3       3
   -4.75     9.5     9.5    12.5
       2       2       3       3
   -4.75     9.5     9.5    12.5
Pier Skew, UpSta & Num, DnSta & Num=  ,2519.41, 4 ,2519.41, 4 , 3 , 3 , 0 ,,
       2       2       3       3
   -4.75    9.44    9.44   12.44
       2       2       3       3
   -4.75    9.44    9.44   12.44
Pier Skew, UpSta & Num, DnSta & Num=  ,2547, 4 ,2547, 4 , 3 , 3 , 0 ,,
       2       2    2.75    2.75
   -4.75    8.58    8.58   11.58
       2       2    2.75    2.75
   -4.75    8.58    8.58   11.58
Pier Skew, UpSta & Num, DnSta & Num=  ,2549.75, 4 ,2549.75, 4 , 3 , 3 , 0 ,,
       2       2    2.75    2.75
   -4.75     8.6     8.6    11.6
       2       2    2.75    2.75
   -4.75     8.6     8.6    11.6
Pier Skew, UpSta & Num, DnSta & Num=  ,2617.42, 4 ,2617.42, 4 , 3 , 3 , 0 ,,
       2       2    2.75    2.75
   -4.75    8.57    8.57   11.57
       2       2    2.75    2.75
   -4.75    8.57    8.57   11.57
Pier Skew, UpSta & Num, DnSta & Num=  ,2620.17, 4 ,2620.17, 4 , 3 , 3 , 0 ,,
       2       2    2.75    2.75
   -4.75    8.58    8.58   11.58
       2       2    2.75    2.75
   -4.75    8.58    8.58   11.58
Pier Skew, UpSta & Num, DnSta & Num=  ,2648.25, 4 ,2648.25, 4 , 3 , 3 , 0 ,,
       2       2       3       3
   -4.75    9.43    9.43   12.43
       2       2       3       3
   -4.75    9.43    9.43   12.43
BR Coef=-1 , 1 , 1 ,.9, 0 ,,,.8,-1,1.2,0,
WSPro=,,,, 1 ,,,, 0 ,,,, 0 ,,,,-1 ,-1 ,-1 , 0 , 0 , 0 , 0 , 0
BC Design=,, 0 ,, 0 ,,,,,,
BC HTab HWMax=35.62

Type RM Length L Ch R = 1 ,7715.169,553.46,788.6,1121.28
BEGIN DESCRIPTION:
Copy of 451s3u - xs 2/4 of RR bridge #1
Bank Station offset =      2453
high bank in ROB is elevated highway
END DESCRIPTION:
XS GIS Cut Line= 6
     3243182.176    13833790.168     3242172.344     13833593.99
      3241346.47    13833613.231      3240864.44     13833764.35
     3240484.404    13833889.799     3238867.807    13834324.373
#Sta/Elev= 30
       0   21.34  624.12   22.84   981.6   19.94 1423.16    7.85 1548.32   15.81
 1638.22   13.33 1710.92    6.64 1733.16    8.74 1772.27    4.11 1807.21    7.71
 1857.92    4.71  1936.9    -.21 2546.55   -4.53 2642.24   -1.06 2660.99    3.72
 2756.97      10 2760.18     4.6 2853.81     5.6 2863.59    7.25 2900.41   26.77
  2946.5   36.11 2960.91   31.19 2982.83   13.87 2995.07    9.59 3174.74    6.54
 3357.88    7.07 3596.88   12.66 3894.49    6.45 4124.02   18.85 4434.17   18.91
#Mann= 3 , 0 , 0
       0     .12       0 1857.92    .035       0 2756.97     .12       0
#XS Ineff= 2 , 0
       0    2038   16.27    2681       0   16.27
Permanent Ineff=
       F       F
Bank Sta=1857.92,2756.97
XS Rating Curve= 0
Exp/Cntr=.5,.3

Type RM Length L Ch R = 1 ,6926.568,754.03,588.64,419.5
BEGIN DESCRIPTION:
451v6 - xs 1/4 of RR bridge #1
Bank Station offset =      2498
high bank in ROB is elevated highway
END DESCRIPTION:
XS GIS Cut Line= 5
     3243280.055    13833602.268     3242156.334    13833372.809
     3241317.672    13833372.648     3240928.315    13832790.451
      3238818.13    13832861.819
#Sta/Elev= 30
       0    21.6  910.35   21.38 1502.03     7.1 1609.78    6.09 1659.41    2.09
 1899.75    2.01 1952.64   -2.82 2004.87   -3.36 2539.87   -4.06  2620.4     .95
 2641.78    6.27 2656.41    1.22 2685.97    3.95 2757.47    2.46 2820.49    6.72
 2920.43    9.73 3003.98   19.34 3028.04   25.14 3070.52   30.62 3145.56   27.52
 3204.28   16.61 3384.76   16.58 3434.54   12.44 3536.92   12.31 3617.73    7.67
 3647.26    8.22 3731.25   16.89 3861.77   18.79 4562.97   13.23 4797.36   15.33
#Mann= 6 ,-1 , 0
       0     .12       0 1502.03     .99       0 1609.78     .12       0
 1899.75    .035       0 2641.78     .99       0 2820.49     .12       0
Bank Sta=1899.75,2641.78
XS Rating Curve= 0
Exp/Cntr=.3,.1

Type RM Length L Ch R = 1 ,6337.928,678.56,426.44,316.25
BEGIN DESCRIPTION:
Copy of 451s2u -  xs 4/4 of Main street
Bank Station offset =      2908
high bank in ROB is elevated highway
END DESCRIPTION:
XS GIS Cut Line= 5
     3243709.866    13832779.309     3242599.155    13832753.872
     3241819.114    13832719.958     3241344.818    13832569.116
     3238752.348    13832767.845
#Sta/Elev= 30
       0   21.26  683.03   18.93 1336.39   20.21 1371.62   18.37 1490.33   17.79
 1531.57   14.65 1829.77    5.18 1851.57   16.48 1906.96    7.96    1911    3.02
 1920.62    -.53 2092.06   -4.04 2537.61   -1.97 2677.87      .4 2742.88    2.72
 2744.26   11.73 2992.84    9.68 3122.97   13.01 3137.73   14.82 3177.63   26.21
 3265.93   31.63 3297.98   29.72  3373.2   13.17 3396.33   12.73 3439.79   17.22
 3462.34   17.33 3670.51   12.74 3972.89   16.28 4829.91   14.11 4989.56   16.19
#Mann= 4 ,-1 , 0
       0     .12       0 1490.33     .99       0 1851.57    .035       0
 2677.87     .12       0
Bank Sta=1911,2677.87
XS Rating Curve= 0
Exp/Cntr=.5,.3

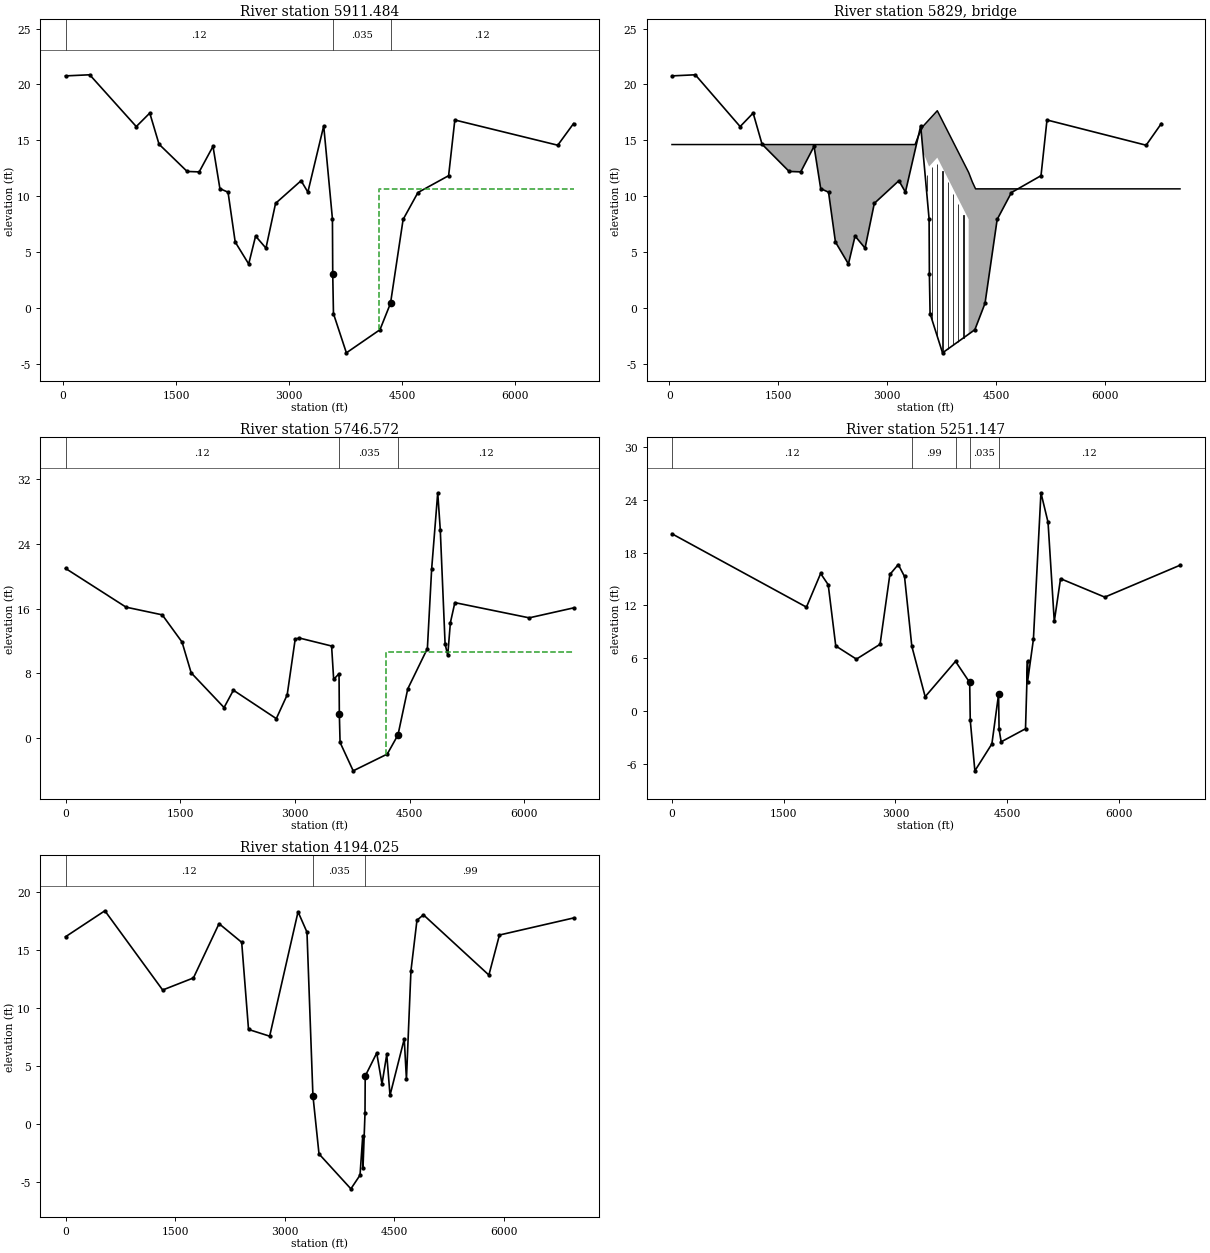
Type RM Length L Ch R = 1 ,5911.484,157.25,164.91,197.31
BEGIN DESCRIPTION:
451s2u -  xs 3/4 of Main street
Bank Station offset =      1272
deleted station 3487.27 @16.48 to open bridge for piers
END DESCRIPTION:
XS GIS Cut Line= 5
     3245195.969    13831291.576     3242567.704     13831799.91
     3241780.551    13832039.638     3241008.736    13832350.188
     3238627.021    13832724.801
#Sta/Elev= 30
    34.1   20.77  355.47   20.87  973.39   16.23 1152.52   17.44 1275.39   14.65
 1648.34   12.21 1808.37   12.17  1991.7   14.46 2083.37   10.67 2191.32   10.35
 2286.31    5.89 2465.32    3.92 2556.99    6.42 2694.49    5.34 2822.08    9.35
 3160.61   11.38 3250.81   10.36  3461.1   16.29 3576.76    7.96  3580.8    3.02
 3590.42    -.53 3761.86   -4.04 4207.41   -1.97 4347.67      .4 4514.86    7.91
 4711.52   10.32 5118.76   11.83 5201.21   16.82 6567.31   14.56 6776.87    16.5
#Mann= 3 , 0 , 0
    34.1     .12       0  3580.8    .035       0 4347.67     .12       0
#XS Ineff= 2 , 0
    34.1  3514.1   10.65 4193.79    34.1   10.65
Permanent Ineff=
       F       F
Bank Sta=3580.8,4347.67
XS Rating Curve= 0
Exp/Cntr=.5,.3

Type RM Length L Ch R = 3 ,5829    ,,,
BEGIN DESCRIPTION:
451s2:  Main st.
END DESCRIPTION:
Bridge Culvert--1,0,-1,-1, 0
Deck Dist Width WeirC Skew NumUp NumDn MinLoCord MaxHiCord MaxSubmerge Is_Ogee
56,53.6,2.6,0, 9, 9, , , .95, 0, 0,0,,
    34.1 3383.38 3431.34 3493.49 3689.96 4121.99 4172.71 4217.01  7034.1
   14.62   14.62   15.42   16.26   17.65   12.12   11.27   10.65   10.65
                           12.06   13.45    7.92
       0 3383.28 3431.24 3493.39 3689.86 4121.89 4172.61 4216.91    7000
   14.62   14.62   15.42   16.26   17.65   12.12   11.27   10.65   10.65
                           12.06   13.45    7.92
Pier Skew, UpSta & Num, DnSta & Num=  ,3542.16, 4 ,3542.16, 4 , 3 , 3 , 0 ,,
     1.5     1.5       2       2
    -4.5     8.7     8.7    11.9
     1.5     1.5       2       2
    -4.5     8.7     8.7    11.9
Pier Skew, UpSta & Num, DnSta & Num=  ,3617.87, 4 ,3617.87, 4 , 3 , 3 , 0 ,,
     1.5     1.5       2       2
    -4.5     9.4     9.4    12.6
     1.5     1.5       2       2
    -4.5     9.4     9.4    12.6
Pier Skew, UpSta & Num, DnSta & Num=  ,3690.2, 4 ,3690.2, 4 , 3 , 3 , 0 ,,
     1.5     1.5       2       2
    -4.5    9.64    9.64   12.84
     1.5     1.5       2       2
    -4.5    9.64    9.64   12.84
Pier Skew, UpSta & Num, DnSta & Num=  ,3762, 4 ,3762, 4 , 3 , 3 , 0 ,,
     1.5     1.5       2       2
    -4.5    9.03    9.03   12.23
     1.5     1.5       2       2
    -4.5    9.03    9.03   12.23
Pier Skew, UpSta & Num, DnSta & Num=  ,3834.11, 4 ,3834.11, 4 , 3 , 3 , 0 ,,
     1.5     1.5       2       2
    -4.5    8.04    8.04   11.24
     1.5     1.5       2       2
    -4.5    8.04    8.04   11.24
Pier Skew, UpSta & Num, DnSta & Num=  ,3906.06, 4 ,3906.06, 4 , 3 , 3 , 0 ,,
     1.5     1.5       2       2
    -4.5    7.02    7.02   10.22
     1.5     1.5       2       2
    -4.5    7.02    7.02   10.22
Pier Skew, UpSta & Num, DnSta & Num=  ,3978.44, 4 ,3978.44, 4 , 3 , 3 , 0 ,,
     1.5     1.5       2       2
    -4.5    6.08    6.08    9.28
     1.5     1.5       2       2
    -4.5    6.08    6.08    9.28
Pier Skew, UpSta & Num, DnSta & Num=  ,4050.2, 4 ,4050.2, 4 , 3 , 3 , 0 ,,
     1.5     1.5       2       2
    -4.5    5.07    5.07    8.27
     1.5     1.5       2       2
    -4.5    5.07    5.07    8.27
BR Coef=-1 , 1 , 1 ,1.25, 0 ,,,.8,-1,2,0,
WSPro=,,,, 1 ,,,, 0 ,,,, 0 ,,,,-1 ,-1 ,-1 , 0 , 0 , 0 , 0 , 0
BC Design=,, 0 ,, 0 ,,,,,,
BC HTab HWMax=20.87

Type RM Length L Ch R = 1 ,5746.572,553.27,495.42,560.92
BEGIN DESCRIPTION:
Copy of 451s2u -  xs 2/4 of Main street
Bank Station offset =      1238
deleted station 3521.37 @16.48ft and 3514.9 @5.22ft
LOB and ROB reach lengths > channel reach length due to shape of d/s xs cut line
END DESCRIPTION:
XS GIS Cut Line= 5
     3245084.241    13831168.894     3242342.166    13831658.949
     3241668.823    13831916.956     3240897.008    13832227.506
     3238639.579    13832692.666
#Sta/Elev= 30
       0   20.97  791.98   16.18 1265.06   15.23  1523.8   11.87 1643.06    8.07
 2073.32    3.78 2195.48    5.92 2756.59    2.41 2898.64    5.34 3003.41   12.22
 3056.65   12.37 3479.57   11.38  3506.6    7.26 3576.76    7.96  3580.8    3.02
 3590.42    -.53 3761.86   -4.04 4207.41   -1.97 4347.67      .4 4475.67    6.09
 4732.03   11.07 4787.86   20.89 4867.46   30.31 4900.63   25.74  4963.7   11.63
 4998.41   10.23 5032.63   14.25 5091.32   16.74 6063.83   14.86 6643.41   16.09
#Mann= 3 ,-1 , 0
       0     .12       0 3576.76    .035       0 4347.67     .12       0
#XS Ineff= 2 , 0
       0 3479.57   10.65 4193.69       0   10.65
Permanent Ineff=
       F       F
Bank Sta=3580.8,4347.67
XS Rating Curve= 0
Exp/Cntr=.5,.3

Type RM Length L Ch R = 1 ,5251.147,934.9,1057.12,2001.86
BEGIN DESCRIPTION:
451v5 - xs 1/4 of Main street
Bank Station offset =       934
END DESCRIPTION:
XS GIS Cut Line= 4
     3245096.439    13830853.646     3241139.639    13831585.875
     3240503.882    13831939.075     3238567.303    13832665.083
#Sta/Elev= 30
       0   20.16 1805.13   11.81 1995.56   15.64 2097.19   14.36 2198.46    7.39
 2475.84    5.89 2793.25    7.58 2924.82   15.53 3037.65   16.66 3121.35    15.3
  3219.4    7.36 3398.63    1.61    3806    5.64  3996.2    3.23 4003.85   -1.07
 4065.89   -6.83 4294.31   -3.76 4384.08    1.89  4390.7   -2.09 4418.66   -3.53
 4745.61   -2.04 4772.32    5.63 4772.51    3.28 4851.64    8.15 4952.69   24.83
 5048.01   21.47 5131.73   10.18 5215.75   15.05 5809.52   12.95 6819.46   16.58
#Mann= 5 ,-1 , 0
       0     .12       0  3219.4     .99       0    3806     .12       0
  3996.2    .035       0 4384.08     .12       0
Bank Sta=3996.2,4384.08
XS Rating Curve= 0
Exp/Cntr=.3,.1

Type RM Length L Ch R = 1 ,4194.025,1531.39,1187.88,1123.39
BEGIN DESCRIPTION:
451v4
Bank Station offset =      1094
END DESCRIPTION:
XS GIS Cut Line= 5
     3245116.345    13830495.339     3241720.431    13830918.897
      3241104.76    13830699.957     3240239.399    13830694.399
     3238462.593    13831639.802
#Sta/Elev= 30
       0   16.11  538.91   18.35 1329.72   11.52 1750.86   12.56 2101.53   17.24
  2411.5   15.63 2505.03    8.12 2794.27    7.54 3182.81   18.26 3304.96   16.51
 3386.46    2.42  3469.7   -2.61 3906.11   -5.62 4031.28   -4.44 4067.99   -1.08
 4071.93    -3.8 4099.26     .88 4102.16     4.1 4259.87    6.09 4331.82    3.42
 4397.14    5.97 4441.55    2.44 4636.46     7.3 4666.46    3.82 4727.89   13.16
 4810.57   17.54 4899.28      18  5794.9   12.81 5939.43   16.26 6953.71   17.73
#Mann= 3 ,-1 , 0
       0     .12       0 3386.46    .035       0 4102.16     .99       0
Bank Sta=3386.46,4102.16
XS Rating Curve= 0
Exp/Cntr=.3,.1