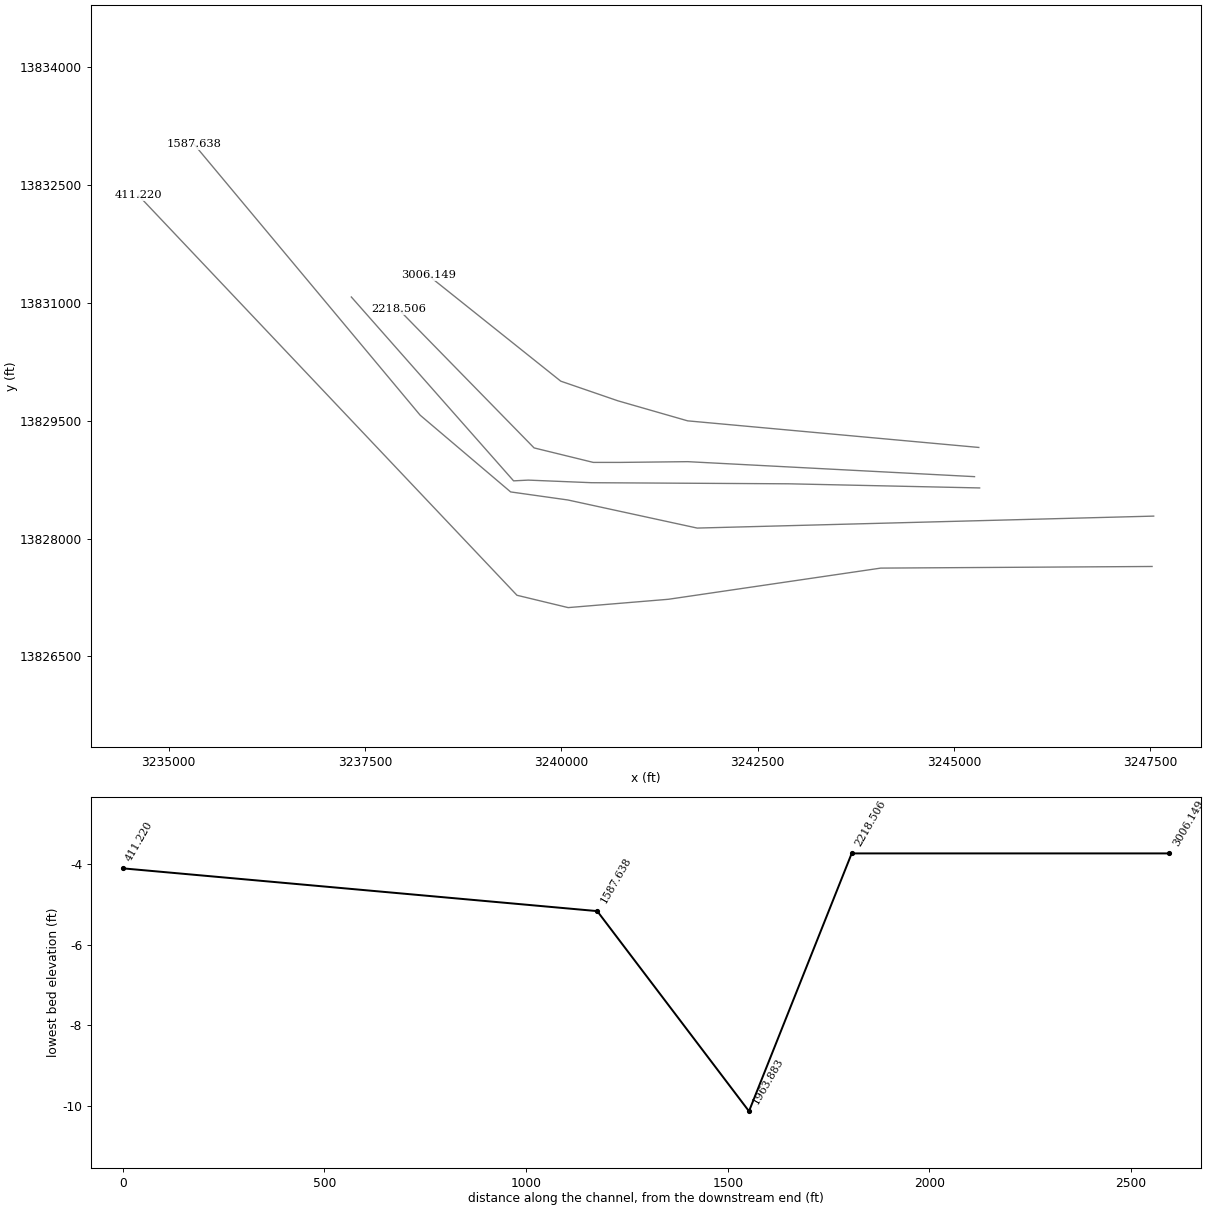
HEC-RAS study O100-00-00.prj: O100-00-00

--- O100-00-00.g01 (geometry) --- (continued)

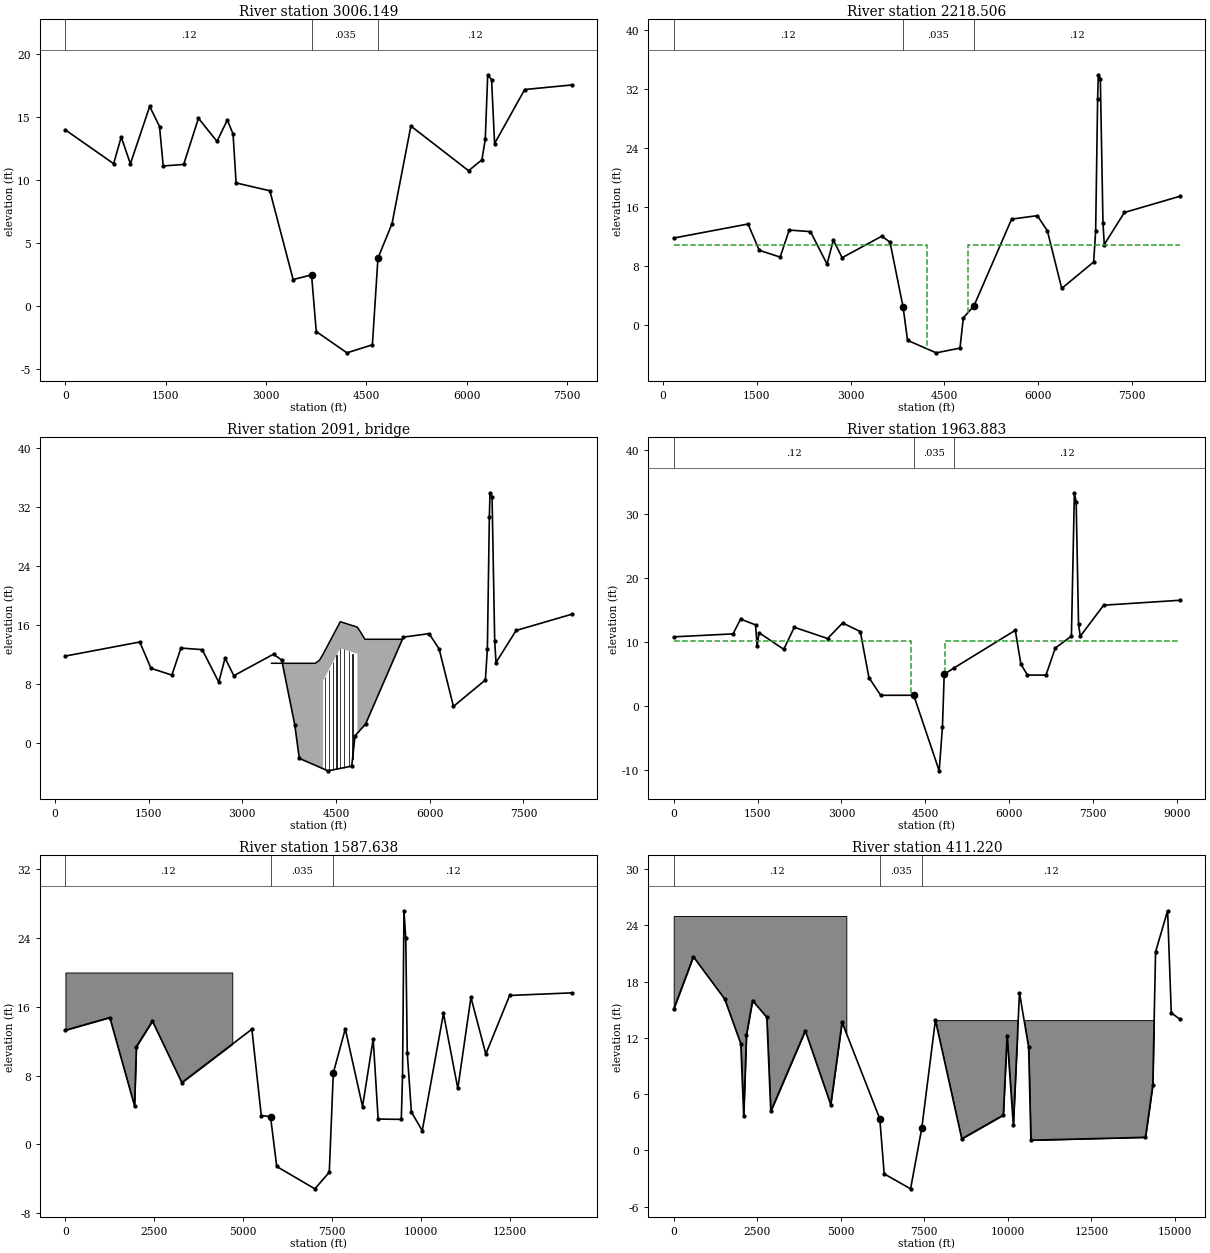
Type RM Length L Ch R = 1 ,3006.149,509.02,787.64,887.11
BEGIN DESCRIPTION:
451v3 -  xs 4/4 HWY 146
Bank Station offset =       789
END DESCRIPTION:
XS GIS Cut Line= 5
     3245315.404    13829161.644     3241607.547    13829500.498
     3240718.708     13829755.85     3239992.152    13830005.658
     3238305.715    13831352.193
#Sta/Elev= 30
       0   13.96  721.27   11.28  834.49    13.4  971.79   11.27 1260.49   15.83
 1407.68   14.23 1462.41    11.1 1768.68   11.22  1990.1   14.89 2266.86   13.05
 2421.63   14.75 2507.61   13.63 2552.93    9.75 3057.74    9.13 3405.99    2.08
 3681.19    2.45 3752.17   -2.05 4210.88   -3.74 4591.63    -3.1 4674.64    3.78
 4885.32    6.52  5167.2   14.27 6030.46   10.72 6229.97   11.59 6280.08   13.23
 6316.28   18.34  6374.3   17.94 6419.22   12.88 6869.53   17.17 7574.46   17.53
#Mann= 3 ,-1 , 0
       0     .12       0 3681.19    .035       0 4674.64     .12       0
Bank Sta=3681.19,4674.64
XS Rating Curve= 0
Exp/Cntr=.5,.3

Type RM Length L Ch R = 1 ,2218.506,254.62,254.62,341.92
BEGIN DESCRIPTION:
Copy of 451s1d -  xs 3/4 HWY 146
Bank Station offset =       501
LOB and ROB reach lengths > channel reach length - Due to shape of cross section cut lines on the ROB. LOB flow line drawn somewhat parallel to the banks.  The survey section 451v3 from u/s section 4/4 was copied to this section and adjusted for model.
END DESCRIPTION:
XS GIS Cut Line= 6
     3245260.633    13828789.854     3241609.166    13828980.681
        3240754.    13828971.284     3240406.296    13828971.284
      3239652.25    13829155.903     3237926.594    13830920.778
#Sta/Elev= 30
     170    11.8  1359.6    13.7 1538.96   10.14 1873.71    9.22 2018.65   12.88
 2358.69   12.67 2624.12    8.27 2724.64   11.52 2865.32    9.14 3500.06   12.05
 3631.37   11.25 3841.12    2.45  3912.1   -2.05 4370.81   -3.74 4751.56    -3.1
 4804.89       1 4973.95     2.6 5577.67   14.36 5989.32   14.83 6150.11   12.77
 6379.61    4.98 6890.86    8.56 6922.68   12.78 6954.34   30.64 6965.11    33.9
 6997.57   33.39 7039.73    13.9 7060.57   10.92 7382.52   15.26 8274.02   17.46
#Mann= 3 ,-1 , 0
     170     .12       0 3841.12    .035       0 4973.95     .12       0
#XS Ineff= 2 , 0
       0    4230   10.82    4880       0   10.82
Permanent Ineff=
       F       F
Bank Sta=3841.12,4973.95
XS Rating Curve= 0
Exp/Cntr=.5,.3

Type RM Length L Ch R = 3 ,2091    ,,,
BEGIN DESCRIPTION:
451s1:  Highway 146
divided highway modeled as 1 structure
EBnd Lns=31.2', WBnd Lns=43.8, gap=26.2 for total bridge width of 101.2'
extended roadway pts taken from TIN
END DESCRIPTION:
Bridge Culvert--1,0,0,-1, 0
Deck Dist Width WeirC Skew NumUp NumDn MinLoCord MaxHiCord MaxSubmerge Is_Ogee
76.7,101.2,2.6,0, 11, 11, , , .95, 0, 0,0,,
 3469.41 4168.11 4234.51  4293.9 4293.91 4568.41 4842.91 4842.92 4906.81 4963.31
    5560
   10.82   10.82   11.22   12.06   12.06   16.45   15.71   15.71   14.85   14.07
   14.07
                                    8.46   12.85   12.11
        
 1284.41 4168.11 4234.51  4293.9 4293.91 4568.41 4842.91 4842.92 4906.81 4963.31
    6080
    10.2   13.41   14.01   14.87   14.87   17.21   16.08   16.08   15.67      15
    11.2
                                   11.27   13.61   12.48
        
Pier Skew, UpSta & Num, DnSta & Num=  ,4328.51, 4 ,4328.51, 4 , 3 , 3 , 0 ,,
     1.5     1.5     2.8     2.8
   -10.5     8.3     8.3    11.1
     1.5     1.5     2.8     2.8
   -10.5     8.3     8.3    11.1
Pier Skew, UpSta & Num, DnSta & Num=  ,4388.43, 4 ,4388.43, 4 , 3 , 3 , 0 ,,
     1.5     1.5     2.8     2.8
   -10.5    8.95    8.95   11.75
     1.5     1.5     2.8     2.8
   -10.5    8.95    8.95   11.75
Pier Skew, UpSta & Num, DnSta & Num=  ,4448.5, 4 ,4448.5, 4 , 3 , 3 , 0 ,,
     1.5     1.5     2.8     2.8
   -10.5    9.45    9.45   12.25
     1.5     1.5     2.8     2.8
   -10.5    9.45    9.45   12.25
Pier Skew, UpSta & Num, DnSta & Num=  ,4508.51, 4 ,4508.51, 4 , 3 , 3 , 0 ,,
     1.5     1.5     2.8     2.8
   -10.5    9.73    9.73   12.53
     1.5     1.5     2.8     2.8
   -10.5    9.73    9.73   12.53
Pier Skew, UpSta & Num, DnSta & Num=  ,4568.37, 4 ,4568.37, 4 , 3 , 3 , 0 ,,
     1.5     1.5     2.8     2.8
   -10.5    10.2    10.2      13
     1.5     1.5     2.8     2.8
   -10.5    10.2    10.2      13
Pier Skew, UpSta & Num, DnSta & Num=  ,4628.61, 4 ,4628.61, 4 , 3 , 3 , 0 ,,
     1.5     1.5     2.8     2.8
   -10.5    9.89    9.89   12.69
     1.5     1.5     2.8     2.8
   -10.5    9.89    9.89   12.69
Pier Skew, UpSta & Num, DnSta & Num=  ,4703.72, 4 ,4703.72, 4 , 3 , 3 , 0 ,,
     1.5     1.5     2.8     2.8
   -10.5     9.7     9.7    12.5
     1.5     1.5     2.8     2.8
   -10.5     9.7     9.7    12.5
Pier Skew, UpSta & Num, DnSta & Num=  ,4763.6, 4 ,4763.6, 4 , 3 , 3 , 0 ,,
     1.5     1.5     2.8     2.8
   -10.5    9.29    9.29   12.09
     1.5     1.5     2.8     2.8
   -10.5    9.29    9.29   12.09
BR Coef= 1 , 0 , 0 ,, 0 ,,,.8,0,,0,
WSPro=,,,, 1 ,,,, 0 ,,,, 0 ,,,,-1 ,-1 ,-1 , 0 , 0 , 0 , 0 , 0
BC Design=,, 0 ,, 0 ,,,,,,
BC HTab HWMax=33.9

Type RM Length L Ch R = 1 ,1963.883,564.76,376.24,327.64
BEGIN DESCRIPTION:
451s1d -  xs 2/4 HWY 146
Bank Station offset =       251
END DESCRIPTION:
XS GIS Cut Line= 6
     3245325.999     13828646.05     3242896.614    13828698.759
      3240384.36    13828712.753     3239579.322    13828745.746
     3239391.373    13828736.348     3237325.229    13831077.656
#Sta/Elev= 30
       0   10.79 1061.74   11.25 1195.22   13.55 1464.55   12.66 1491.88    9.41
 1527.58   11.43 1968.81    8.84 2157.04   12.28 2752.98   10.53 3021.75   12.95
 3338.41   11.61 3492.65    4.41 3703.73    1.66  4293.9    1.67  4749.2  -10.13
 4807.76   -3.24 4839.11    4.95 5006.58    5.89 6110.77   11.81 6210.34    6.53
 6328.22    4.82 6660.13    4.82 6825.94    9.04 7114.63    10.9 7167.77   33.28
 7199.65   31.84 7242.16   12.75 7273.02   10.88 7691.21   15.73 9058.86    16.5
#Mann= 3 ,-1 , 0
       0     .12       0  4293.9    .035       0 5006.58     .12       0
#XS Ineff= 2 , 0
       0    4252    10.2    4860       0    10.2
Permanent Ineff=
       F       F
Bank Sta=4293.9,4839.11
XS Rating Curve= 0
Exp/Cntr=.5,.3

Type RM Length L Ch R = 1 ,1587.638,1002.87,1176.42,1284.37
BEGIN DESCRIPTION:
451v2 -  xs 1/4 HWY 146
Bank Station offset =     -2015
cross section blocked on LOB at watershed edge, ROB block due to pond/bay area not directly connected to Goose Creek
END DESCRIPTION:
XS GIS Cut Line= 6
     3247542.439    13828287.395     3241729.489    13828134.995
     3240082.386    13828492.859     3239353.784    13828595.387
     3238201.957    13829572.317     3235320.639    13833024.462
#Sta/Elev= 30
       0   13.29 1247.45   14.76 1944.12    4.47 1995.59   11.37 2446.25   14.35
 3273.31    7.19 5244.22    13.4 5508.95    3.35 5768.49    3.24  5943.2   -2.57
 7014.87   -5.17 7421.77   -3.24 7534.33    8.31 7871.87   13.44 8356.61     4.4
 8656.48   12.26 8795.62    2.95 9447.08    2.91 9482.25       8 9521.58   27.18
 9572.19   24.01 9615.47   10.61 9730.86    3.7710036.21     1.610632.97   15.23
11036.59    6.5111405.86    17.111824.16   10.51 12494.7   17.3314243.18   17.63
#Mann= 3 , 0 , 0
       0     .12       0 5768.49    .035       0 7534.33     .12       0
#Block Obstruct= 2 , 0
       0    4693      20 7871.87       0   13.44
Bank Sta=5768.49,7534.33
XS Rating Curve= 0
Exp/Cntr=.3,.1

Type RM Length L Ch R = 1 ,411.220 ,548.81,411.22,424.48
BEGIN DESCRIPTION:
451v1
Bank Station offset =     -2088
cross section blocked on LOB at watershed edge, ROB block due to pond/bay area not directly connected to Goose Creek
LOB and ROB reach lengths > channel reach length - This the downstream most cross section. Flow lines extended beyond the length of channel downstream. No specific reason found. Flow lines can be trimmed to the downstream channel reach length.
END DESCRIPTION:
XS GIS Cut Line= 6
     3247521.747    13827645.959     3244066.266    13827625.267
     3241363.182    13827228.374     3240086.322    13827122.253
     3239434.565    13827279.344     3234613.901    13832372.088
#Sta/Elev= 30
       0   15.07  587.95   20.66  1525.1   16.15 2006.71   11.38 2094.67    3.66
  2177.8   12.34 2358.73   15.98 2785.73    14.2 2904.19    4.16 3936.54   12.76
 4698.51    4.87 5037.55   13.67 6166.77    3.36 6297.98   -2.51 7087.55   -4.11
 7423.41    2.38 7830.21   13.89 8618.92    1.23 9862.62    3.76  9974.2   12.24
10162.17    2.6810345.97   16.8210620.16   10.9810687.25    1.0814116.07    1.39
14334.77    6.9614418.11   21.1814778.13   25.5614887.81   14.6615151.77   13.98
#Mann= 3 , 0 , 0
       0     .12       0 6166.77    .035       0 7423.41     .12       0
#Block Obstruct= 3 ,-1
 7830.21   10282   13.89   10344   14473   13.89       0    5165      25
Bank Sta=6166.77,7423.41
XS Rating Curve= 0
Exp/Cntr=.3,.1

Chan Stop Cuts=-1